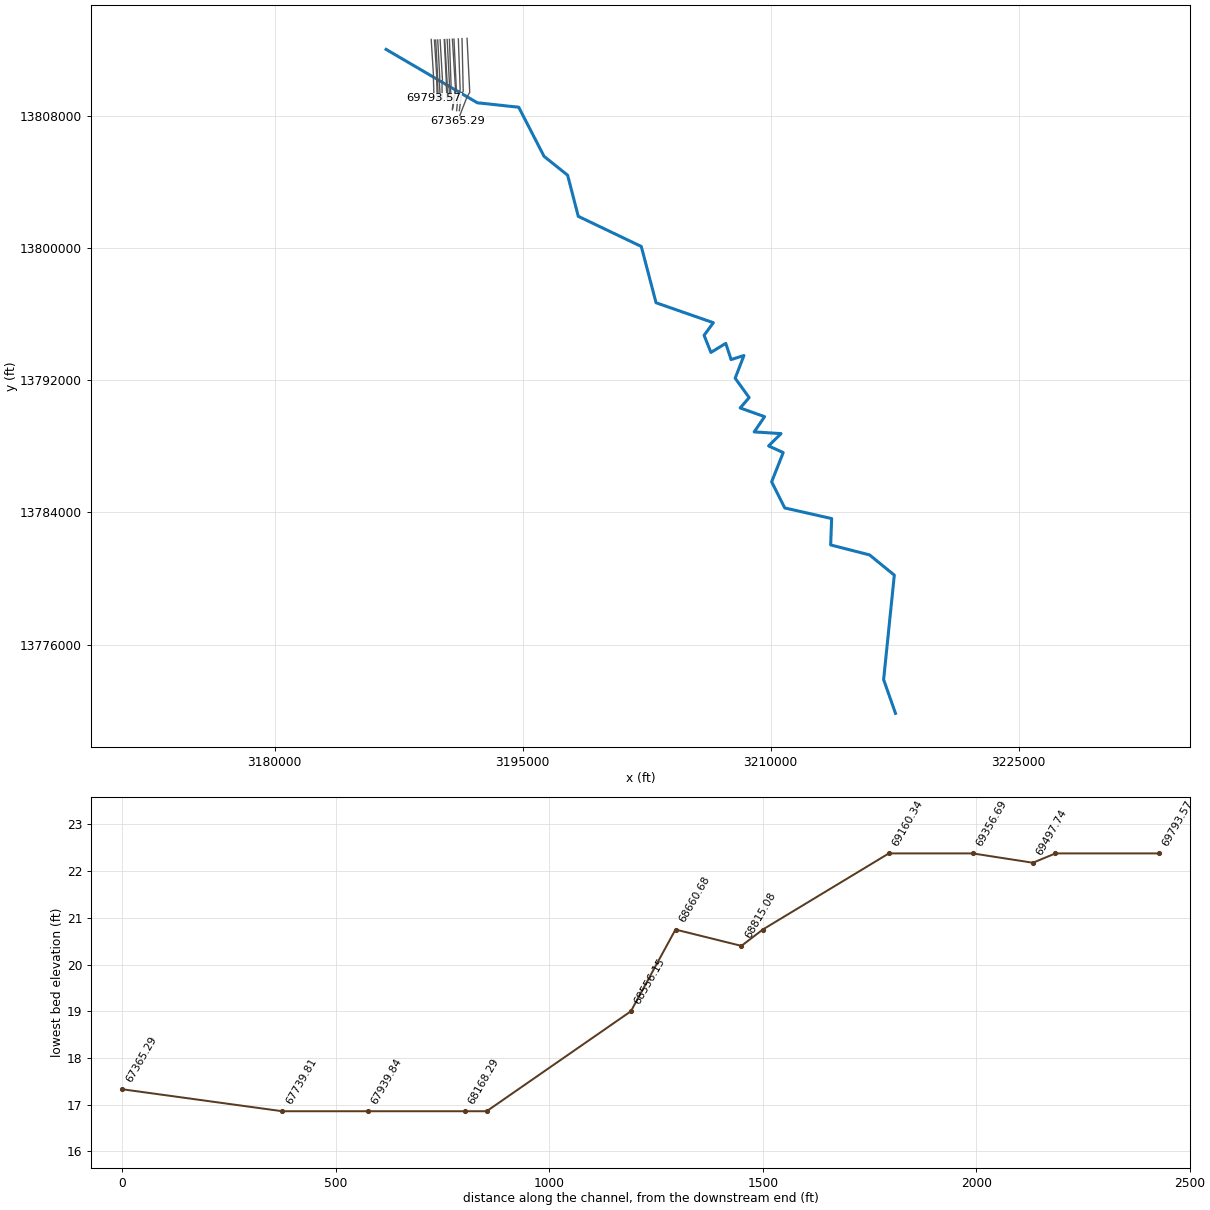
--- B100-00-00.prj (project) ---

Proj Title=B100-00-00
Current Plan=p02
Default Exp/Contr=.3,.1
English Units
Geom File=g01
Flow File=f01
Flow File=f02
Plan File=p01
Plan File=p02
Y Axis Title=Elevation
X Axis Title(PF)=Main Channel Distance
X Axis Title(XS)=Station
BEGIN DESCRIPTION:
HCFCD MODEL SUMMARY METADATA
The purpose of this summary is to document the high points of hydrologic and hydraulic models filed within the HCFCD Model and Map Management (M3) system.  The document includes references to the project that prompted the creation or update of the model.
DESCRIPTION OF PROJECT:
The following model was the hydraulic model which represented the effective condition of Harris County's watersheds.
PURPOSE OF PROJECT:
Development of effective models to support the National Flood Insurance Program.
HCFCD Watershed Unit ID: B
M3 Study Identifier: 2007_Effective_B
Engineer: HCFCD
Project Name: EffectiveFEMA Study for watershed Armand Bayou (B)
Study Completion Date: 6/18/2007
FEMA Case Number: [No Data]
FEMA Approval Date: [No Date in Database]
Vertical Datum: NAVD 1988
Datum Note: 2001 ADJ
HYDRAULICS
HCFCD Unit No.:  B100-00-00
Hydraulic Program Name: HEC-RAS
Hydraulic Program Version: 3.0.1
Steady Hydraulic Model: Yes
Unsteady Hydraulic Model: No
Update1:
The effective FEMA hydraulic model for unit number B100-00-00 has been updated by FEMA LOMR 09-06-2867P with an effective date of 11/30/2009.
Update 2:
The effective FEMA hydraulic model for unit number B100-00-00 has been updated by FEMA LOMR 14-06-4559P with an effective date of 10/16/2015.
END DESCRIPTION:
DSS Export Rating Curves= 0
DSS Export Rating Curve Sorted= 0
DSS Export Volume Flow Curves= 0
DXF OffsetX= 0
DXF OffsetY= 0
DXF ScaleX= 1
DXF ScaleY= 10

--- B100-00-00.p02 (plan) ---

Plan Title=Effective Floodway 2015
Version=Version 3.0.1  May 2012
Short Identifier=FW+LOMR FW
Geom File=g01
Flow File=f02
Subcritical Flow
K Sum by GR= 0
Std Step Tol= 0.01
Critical Tol= 0.01
Num of Std Step Trials= 20
Max Error Tol= 0.3
Flow Tol Ratio= 0.001
Split Flow NTrial= 30
Split Flow Tol= 0.02
Split Flow Ratio= 0.02
Log Output Level= 0
Friction Slope Method= 1
Unsteady Friction Slope Method= 2
Parabolic Critical Depth
Global Vel Dist= 0 , 0 , 0
Global Log Level= 0
CheckData=True
Encroach Param=-1 ,0,0, 2
Encroach River=B100-00-00
Encroach Reach=B100-00-00_0022
Encroach Node=69793.57
       1 2117.72  2186.8
Encroach Node=69550.45
       1 4964.07    5100
Encroach Node=69497.74
       1    4950    5200
Encroach Node=69427
       1    4950    5460
Encroach Node=69356.69
       1    4950    5413
Encroach Node=69160.34
       1 4964.07    5400
Encroach Node=68865.08
       1 4947.01 5399.84
Encroach Node=68815.08
       1    4916    5370
Encroach Node=68738
       1    4916    5500
Encroach Node=68660.68
       1    4850    5300
Encroach Node=68556.15
       1    4800    5250
Encroach Node=68387.3
       1    4700    5300
Encroach Node=68218.39
       1    4750    5200
Encroach Node=68168.29
       1  4744.4    5200
Encroach Node=68054.1
       1  4744.4    5200
Encroach Node=67939.84
       1  4744.4    5200
Encroach Node=67739.81
       1 4779.64 5165.89
Encroach Node=67365.29
       1 4732.39 5145.92
Encroach Node=67350.22
       1 4748.86 5169.19
Encroach Node=67315.05
       1 4724.41  5110.2
Encroach Node=67284.87
       1 4779.51 5160.97
Encroach Node=66525.1
       1    4820    5100
Encroach Node=66474.97
       1 4862.73    5070
Encroach Node=66409
       1 4862.73    5070
Encroach Node=66343.05
       1    4900    5070
Encroach Node=66142.97
       1 4920.75 5075.06
Encroach Node=66054.98
       1  4952.2 5087.59
Encroach Node=66002.63
       1 4945.36 5100.68
Encroach Node=65912.83
       1 4945.36 5097.73
Encroach Node=65706.84
       1 4927.35 5070.75
Encroach Node=65138.53
       1 4889.66 5026.34
Encroach Node=65088.44
       1 4891.66 5026.34
Encroach Node=65006
       1    4903    5025
Encroach Node=64924.23
       1 4904.11  5027.1
Encroach Node=64819.77
       1 3973.57  4081.1
Encroach Node=63842.05
       1 4875.71 5060.08
Encroach Node=62832.56
       1 4886.38    5200
Encroach Node=62041.88
       1 4933.61 5122.56
Encroach Node=61225.3
       1 4919.66 5169.65
Encroach Node=60536.27
       1 4842.37 5045.98
Encroach Node=59178.74
       1 4944.92 5074.72
Encroach Node=58659.35
       1 4899.44 5093.64
Encroach Node=58560.23
       1 4877.18 5091.52
Encroach Node=58383.8
       1 4877.18 5091.52
Encroach Node=58206.36
       1 4877.18 5091.52
Encroach Node=58023.52
       1 4724.47 5046.51
Encroach Node=57354.84
       1    4840    5262
Encroach Node=56229.95
       1 4798.98 5287.52
Encroach Node=55180.78
       1    4840    5270
Encroach Node=53558.74
       1    4820    5594
Encroach Node=52312.42
       1    4321    5636
Encroach Node=51320.59
       1 4753.26    5959
Encroach Node=50230.66
       1 4107.54    5744
Encroach Node=49430.51
       1 4025.82    5531
Encroach Node=49376.99
       1 3712.16    5531
Encroach Node=49319.8
       1 3712.16    5514
Encroach Node=49262.58
       1 3712.16    5496
Encroach Node=49053.31
       1 3749.51    5522
Encroach Node=48377.63
       1  3484.3    5330
Encroach Node=47629
       1 3613.65 5230.15
Encroach Node=47029.41
       1    3824 5109.29
Encroach Node=46118.78
       1    4260 5211.69
Encroach Node=45071
       1 4682.81  5095.2
Encroach Node=44971.5
       1    4350  5154.9
Encroach Node=43905.84
       1 4329.91  5195.1
Encroach Node=42907.14
       1 4335.78 5309.92
Encroach Node=42218.84
       1    4700 5201.92
Encroach Node=40786.98
       1  4259.9    4970
Encroach Node=39912.8
       1    4875 5127.76
Encroach Node=39369.61
       1 4637.17 5198.39
Encroach Node=37500.83
       1 4896.07 5167.19
Encroach Node=36405.95
       1 4873.15 5211.64
Encroach Node=34186.11
       1 4670.32 5223.11
Encroach Node=32938.54
       1 4610.29 5193.71
Encroach Node=31668.25
       1 4688.04 5419.54
Encroach Node=31618.22
       1 4688.04 5419.54
Encroach Node=31568.19
       1  4758.3  5289.3
Encroach Node=30883.22
       1 4536.65 5350.44
Encroach Node=30033.6
       1 4661.11 5368.42
Encroach Node=28982
       1 4775.82 5357.99
Encroach Node=28745.12
       1 4222.94 5548.32
Encroach Node=26559.78
       1 4649.41 5364.47
Encroach Node=25539.14
       1    4534 5542.28
Encroach Node=23904.22
       1 4862.83 5497.29
Encroach Node=23422.08
       1 4778.19 5448.53
Encroach Node=22280.19
       1  4512.3 5291.87
Encroach Node=21228.02
       1 4153.97 5353.78
Encroach Node=20376.82
       1 4481.43  5337.5
Encroach Node=20263.27
       1 4796.52 5216.15
Encroach Node=20088.4
       1 4683.35 5305.28
Encroach Node=19913.61
       1 4683.35 5305.28
Encroach Node=19510.59
       1 4604.39 5460.28
Encroach Node=18656.75
       1 4253.53 5771.19
Encroach Node=17405.65
       1 3815.06 6703.16
Encroach Node=16423.13
       1 3967.12 5672.89
Encroach Node=14933.72
       1 4277.91 5748.67
Encroach Node=13996.76
       1 4340.87 5630.07
Encroach Node=12866.58
       1 4327.96 5642.71
Encroach Node=11525.78
       1 4132.43 5699.18
Encroach Node=10503.88
       1 3993.34 5921.95
Encroach Node=9564.122
       1 4264.93    5910
Encroach Node=8322.608
       1 4344.87 5590.84
Encroach Node=6952.755
       1 4136.05 5636.46
Encroach Node=6043.869
       1 4156.12 5824.46
Encroach Node=4712.607
       1 4155.18 6032.01
Encroach Node=3785.66
       1 4039.56 5674.86
Encroach Node=2904.979
       1 3782.21 6378.65
Encroach Node=2765.845
       1 2604.81    5300
Encroach Node=2572.18
       1 1715.63 4785.21
Encroach Node=2378.514
       1 1715.63 4785.21
Encroach Node=2194.604
       1 2535.73 7081.77
BEGIN DESCRIPTION:
FEMA Effective 2007 + LOMR 09-06-2867P + LOMR 14-06-4559P
END DESCRIPTION:
Computation Interval=1HOUR
Output Interval=1HOUR
Run HTab= 0
Run UNet= 0
Run PostProcess= 0
UNET Theta= 1
UNET ZTol= 0.02
UNET ZSATol= 0.1
UNET MxIter= 20
UNET MaxInSteps= 20
UNET DtIC= 0
UNET DtMin= 0
UNET MaxCRTS= 20
UNET WFStab= 2
UNET SFStab= 1
UNET WFX= 1
UNET SFX= 1
UNET Convert EG Bridges=-1
UNET Use Existing IB Tables=-1
Instantaneous Interval=1HOUR
Write IC File= 0
IC Time=0
Write Velocity= 0
Write Detailed= 0

--- B100-00-00.p01 (plan) ---

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Plan Title=Effective Multi-Profile 2015
Short Identifier=Eff+LOMR MP
Geom File=g01
Flow File=f01
Friction Slope Method= 0
Secant Critical Depth
Encroach Param=-1 ,0,0, 0

--- B100-00-00.f02 (steady flow) ---

Flow Title=Effective Floodway 2015
Version=Version 3.0.1  May 2012
Number of Profiles= 2
Profile Names=1PCT_100yr,1PCTFloodway_100yr
River Rch & RM=B100-00-00,B100-00-00_0022 ,69793.57
     511     511
River Rch & RM=B100-00-00,B100-00-00_0022 ,69550.45
     511     511
River Rch & RM=B100-00-00,B100-00-00_0022 ,69497.74
     529     529
River Rch & RM=B100-00-00,B100-00-00_0022 ,69356.69
     554     554
River Rch & RM=B100-00-00,B100-00-00_0022 ,69160.34
     594     594
River Rch & RM=B100-00-00,B100-00-00_0022 ,68865.08
     601     601
River Rch & RM=B100-00-00,B100-00-00_0022 ,68815.08
     623     623
River Rch & RM=B100-00-00,B100-00-00_0022 ,68660.68
     639     639
River Rch & RM=B100-00-00,B100-00-00_0022 ,68556.15
     692     692
River Rch & RM=B100-00-00,B100-00-00_0022 ,68218.39
     700     700
River Rch & RM=B100-00-00,B100-00-00_0022 ,68168.29
     739     739
River Rch & RM=B100-00-00,B100-00-00_0022 ,67939.84
     775     775
River Rch & RM=B100-00-00,B100-00-00_0022 ,67739.81
     846     846
River Rch & RM=B100-00-00,B100-00-00_0022 ,67365.29
     863     863
River Rch & RM=B100-00-00,B100-00-00_0022 ,67284.87
    1032    1032
River Rch & RM=B100-00-00,B100-00-00_0022 ,66525.1
    1045    1045
River Rch & RM=B100-00-00,B100-00-00_0022 ,66474.97
    1078    1078
River Rch & RM=B100-00-00,B100-00-00_0022 ,66343.05
    1130    1130
River Rch & RM=B100-00-00,B100-00-00_0022 ,66142.97
    1168    1168
River Rch & RM=B100-00-00,B100-00-00_0022 ,66002.63
    1193    1193
River Rch & RM=B100-00-00,B100-00-00_0022 ,65912.83
    1253    1253
River Rch & RM=B100-00-00,B100-00-00_0022 ,65706.84
    1433    1433
River Rch & RM=B100-00-00,B100-00-00_0022 ,65138.53
    1450    1450
River Rch & RM=B100-00-00,B100-00-00_0022 ,65088.44
    1507    1507
River Rch & RM=B100-00-00,B100-00-00_0022 ,64924.23
    1545    1545
River Rch & RM=B100-00-00,B100-00-00_0022 ,64819.77
    1946    1946
River Rch & RM=B100-00-00,B100-00-00_0022 ,63842.05
    1935    1935
River Rch & RM=B100-00-00,B100-00-00_0022 ,62832.56
    1926    1926
River Rch & RM=B100-00-00,B100-00-00_0022 ,62041.88
    4333    4333
River Rch & RM=B100-00-00,B100-00-00_0022 ,59178.74
    4655    4655
River Rch & RM=B100-00-00,B100-00-00_0022 ,56229.95
    4812    4812
River Rch & RM=B100-00-00,B100-00-00_0022 ,53558.74
    5029    5029
River Rch & RM=B100-00-00,B100-00-00_0022 ,51320.59
   10326   10326
River Rch & RM=B100-00-00,B100-00-00_0022 ,47029.41
   11278   11278
River Rch & RM=B100-00-00,B100-00-00_0022 ,39369.61
   11434   11434
River Rch & RM=B100-00-00,B100-00-00_0022 ,36405.95
   13843   13843
River Rch & RM=B100-00-00,B100-00-00_0022 ,26559.78
   14152   14152
River Rch & RM=B100-00-00,B100-00-00_0022 ,21228.02
   17841   17841
River Rch & RM=B100-00-00,B100-00-00_0022 ,14933.72
   29102   29102
Boundary for River Rch & Prof#=B100-00-00,B100-00-00_0022 , 1
Up Type= 0
Dn Type= 3
Dn Slope=.0002
DSS Import GetInterval= 0
DSS Import GetPeak= 0
DSS Import FillOption= 0

--- B100-00-00.f01 (steady flow) ---

Flow Title=Effective Multi-Profile 2015
Version=Version 3.0.1  May 2012
Number of Profiles= 4
Profile Names=10PCT_10yr, 2PCT_50yr, 1PCT_100yr, 0.2PCT_500yr
River Rch & RM=B100-00-00,B100-00-00_0022 ,69793.57
     293     437     511     733
River Rch & RM=B100-00-00,B100-00-00_0022 ,69550.45
     293     437     511     733
River Rch & RM=B100-00-00,B100-00-00_0022 ,69497.74
     303     452     529     758
River Rch & RM=B100-00-00,B100-00-00_0022 ,69356.69
     318     473     554     793
River Rch & RM=B100-00-00,B100-00-00_0022 ,69160.34
     341     507     594     850
River Rch & RM=B100-00-00,B100-00-00_0022 ,68865.08
     345     513     601     860
River Rch & RM=B100-00-00,B100-00-00_0022 ,68815.08
     358     533     623     892
River Rch & RM=B100-00-00,B100-00-00_0022 ,68660.68
     367     546     639     914
River Rch & RM=B100-00-00,B100-00-00_0022 ,68556.15
     398     591     692     989
River Rch & RM=B100-00-00,B100-00-00_0022 ,68218.39
     403     599     700    1001
River Rch & RM=B100-00-00,B100-00-00_0022 ,68168.29
     426     632     739    1056
River Rch & RM=B100-00-00,B100-00-00_0022 ,67939.84
     447     663     775    1107
River Rch & RM=B100-00-00,B100-00-00_0022 ,67739.81
     489     724     846    1208
River Rch & RM=B100-00-00,B100-00-00_0022 ,67365.29
     498     738     863    1231
River Rch & RM=B100-00-00,B100-00-00_0022 ,67284.87
     598     884    1032    1471
River Rch & RM=B100-00-00,B100-00-00_0022 ,66525.1
     605     894    1045    1489
River Rch & RM=B100-00-00,B100-00-00_0022 ,66474.97
     625     923    1078    1535
River Rch & RM=B100-00-00,B100-00-00_0022 ,66343.05
     655     968    1130    1609
River Rch & RM=B100-00-00,B100-00-00_0022 ,66142.97
     678    1000    1168    1663
River Rch & RM=B100-00-00,B100-00-00_0022 ,66002.63
     692    1022    1193    1698
River Rch & RM=B100-00-00,B100-00-00_0022 ,65912.83
     728    1073    1253    1782
River Rch & RM=B100-00-00,B100-00-00_0022 ,65706.84
     834    1228    1433    2036
River Rch & RM=B100-00-00,B100-00-00_0022 ,65138.53
     844    1242    1450    2060
River Rch & RM=B100-00-00,B100-00-00_0022 ,65088.44
     878    1292    1507    2141
River Rch & RM=B100-00-00,B100-00-00_0022 ,64924.23
     900    1324    1545    2194
River Rch & RM=B100-00-00,B100-00-00_0022 ,64819.77
    1138    1670    1946    2759
River Rch & RM=B100-00-00,B100-00-00_0022 ,63842.05
    1102    1658    1935    2746
River Rch & RM=B100-00-00,B100-00-00_0022 ,62832.56
    1075    1649    1926    2737
River Rch & RM=B100-00-00,B100-00-00_0022 ,62041.88
    2397    3720    4333    5864
River Rch & RM=B100-00-00,B100-00-00_0022 ,59178.74
    2550    4087    4655    6426
River Rch & RM=B100-00-00,B100-00-00_0022 ,56229.95
    2625    4269    4812    6704
River Rch & RM=B100-00-00,B100-00-00_0022 ,53558.74
    2727    4410    5029    6920
River Rch & RM=B100-00-00,B100-00-00_0022 ,51320.59
    5952    8841   10326   14854
River Rch & RM=B100-00-00,B100-00-00_0022 ,47029.41
    6614    9488   11278   16377
River Rch & RM=B100-00-00,B100-00-00_0022 ,39369.61
    6716    9618   11434   16653
River Rch & RM=B100-00-00,B100-00-00_0022 ,36405.95
    8194   11889   13843   20056
River Rch & RM=B100-00-00,B100-00-00_0022 ,26559.78
    8370   12207   14152   20334
River Rch & RM=B100-00-00,B100-00-00_0022 ,21228.02
   10312   15372   17841   24709
River Rch & RM=B100-00-00,B100-00-00_0022 ,14933.72
   15433   24076   29102   40693
Boundary for River Rch & Prof#=B100-00-00,B100-00-00_0022 , 1
Up Type= 0
Dn Type= 3
Dn Slope=.0002
DSS Import GetInterval= 0
DSS Import GetPeak= 0
DSS Import FillOption= 0

--- B100-00-00.g01 (geometry) ---

Geom Title=B100-00-00
Version=Version 3.0.1  May 2012

River Reach=B100-00-00      ,B100-00-00_0022
Reach XY= 30
       3186744.5       13812007.       3192263.5       13808778.
       3194767.5       13808509.      3196297.25       13805540.
       3197724.5       13804397.       3198368.5       13801910.
      3202179.75       13800087.      3203075.25       13796681.
      3206539.25       13795474.       3205978.5       13794711.
        3206394.       13793676.        3207290.       13794225.
      3207612.25       13793244.      3208389.25       13793489.
      3207858.75       13792118.      3208705.25       13790945.
        3208164.       13790317.      3209639.25       13789790.
       3209010.5       13788869.        3210637.       13788766.
      3209880.25       13788022.        3210767.       13787617.
      3210064.75       13785850.      3210859.25       13784269.
      3213696.25       13783625.        3213636.       13782031.
       3215987.5       13781429.       3217486.5       13780204.
       3216839.5       13773886.     3217558.434     13771842.26

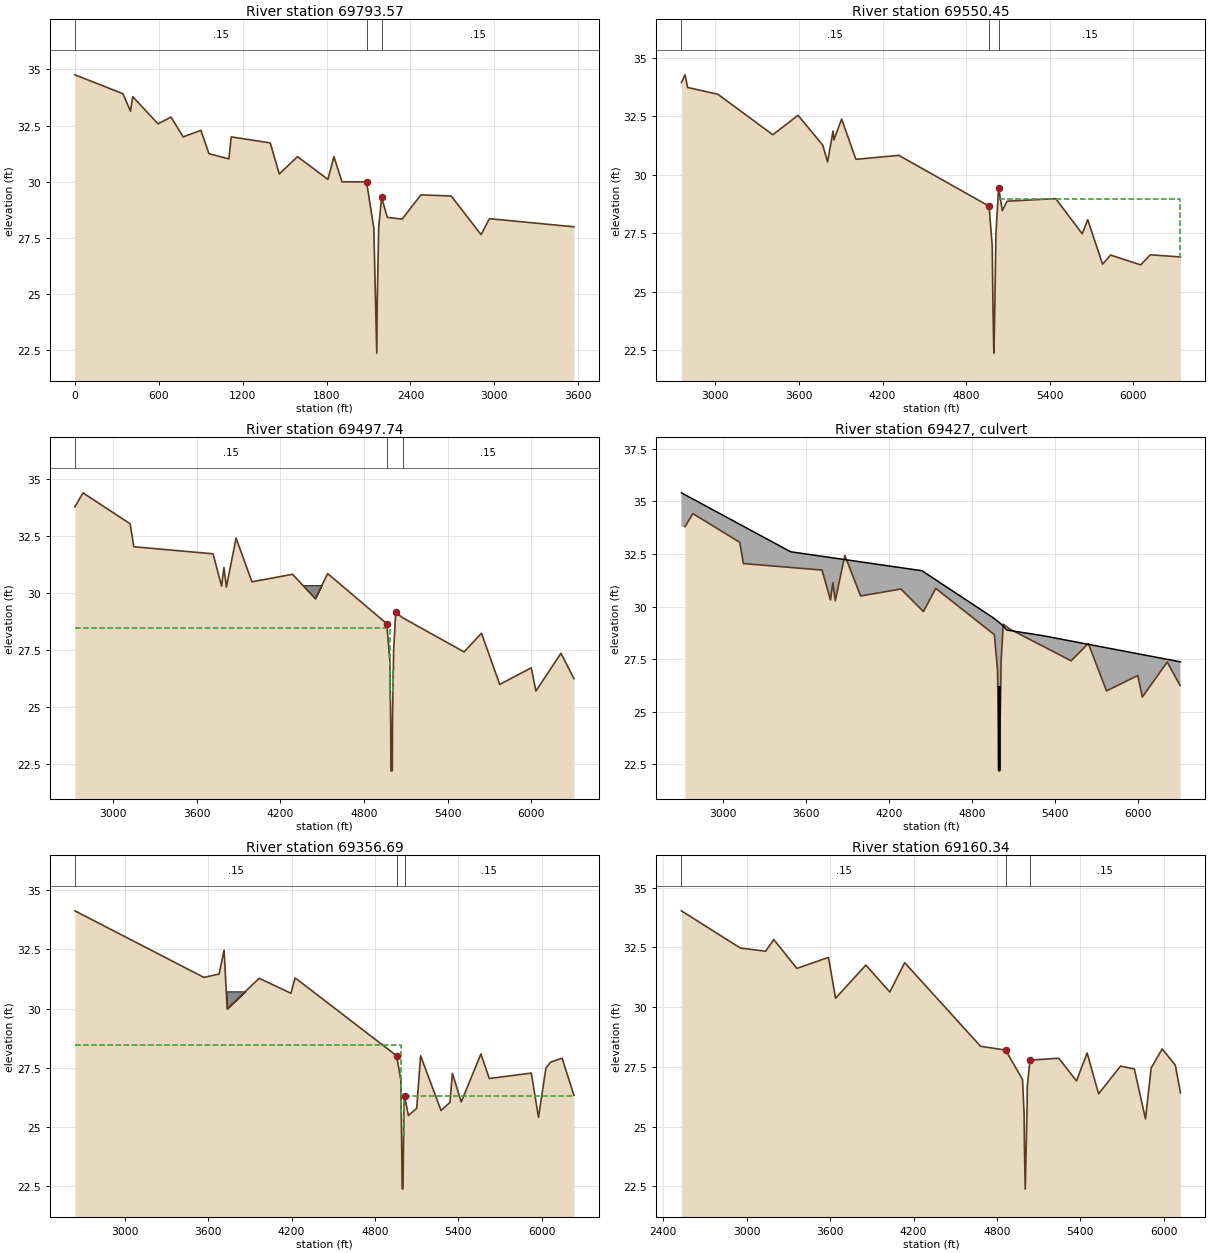
Type RM Length L Ch R = 1 ,69793.57,237.68,243.11,231.59
BEGIN DESCRIPTION:
CROSS SECTION ADDED TO EXTEND FLOODWAY TO EXISTING STUDY
END DESCRIPTION:
XS GIS Cut Line= 5
     3189471.472    13812611.675       3189528.3    13811717.363
     3189607.719    13810467.542     3189600.201    13810455.969
     3189641.695    13809050.046
#Sta/Elev= 30
       0   34.76  344.25   33.92  397.51   33.14  413.53   33.79  594.98   32.58
  687.76   32.88  774.45      32  900.94   32.29  959.12   31.25 1101.39   31.02
 1118.06      32 1397.13   31.73 1461.64   30.35 1592.33   31.12 1809.39   30.11
 1852.56   31.12 1910.04      30 2085.98      30 2137.73   27.94 2158.83   22.38
 2162.26   24.69 2172.86      28 2193.62   29.31 2233.79   28.42 2339.92   28.34
 2474.63   29.42 2691.51   29.37 2904.81   27.65 2964.67   28.36 3568.79      28
#Mann= 3 , 0 , 0
       0     .15       0 2085.98    .032       0 2193.62     .15       0
Bank Sta=2085.98,2193.62
XS Rating Curve= 0
Exp/Cntr=.3,.1

Type RM Length L Ch R = 1 ,69550.45,70.24,52.71,64.12
BEGIN DESCRIPTION:
xsec extended to basin boundaries (left and right)
END DESCRIPTION:
XS GIS Cut Line= 5
     3189667.658    13812568.439     3189724.486    13811674.127
     3189810.037    13810327.804     3189799.539    13810311.644
     3189838.342    13808996.907
#Sta/Elev= 30
  2757.3   33.94 2783.53   34.27 2801.95   33.73  3019.1   33.44 3413.21   31.71
 3593.75   32.54 3770.85   31.27 3806.06   30.55 3845.14   31.87 3851.15   31.49
 3906.54   32.38 4009.12   30.66 4317.15   30.83 4964.07   28.66  4986.7   26.97
 4992.46   24.24 4998.53   22.38 5004.06   23.82  5013.3   27.47 5032.66   29.44
 5059.35   28.47 5093.04   28.87 5442.31   28.98 5632.37   27.48 5671.86   28.08
 5778.46   26.18 5835.79   26.57 6051.72   26.15  6120.6   26.58 6337.03   26.49
#Mann= 3 ,-1 , 0
  2757.3     .15       0 4964.07    .032       0 5032.66     .15       0
#XS Ineff= 1 ,-1
 5034.95 6412.23   28.96
Permanent Ineff=
       F
Bank Sta=4964.07,5032.66
XS Rating Curve= 0
Exp/Cntr=.5,.3

Type RM Length L Ch R = 1 ,69497.74,154.91,141.05,139.31
BEGIN DESCRIPTION:
xsec extended to basin boundaries (left and right)
END DESCRIPTION:
XS GIS Cut Line= 5
     3189744.786    13812572.351     3189790.499    13811682.929
     3189860.845    13810314.234     3189846.358    13810291.933
      3189899.27    13808998.647
#Sta/Elev= 30
 2725.39   33.79 2783.58   34.41 3121.98   33.05 3148.58   32.04 3717.26   31.73
 3778.44   30.31 3795.43   31.13 3812.91   30.27  3882.5   32.42  3996.3    30.5
 4288.01   30.83 4450.77   29.76 4539.98   30.86 4964.07   28.66  4986.7   26.97
 4992.46   24.24 4993.75   22.22 4998.58   22.18 5003.96    22.2 5005.02   24.37
  5013.3   27.47 5028.24   29.16 5078.11   28.92 5519.03   27.42 5643.75   28.24
 5774.96   25.99 6001.01   26.72 6034.57    25.7 6214.23   27.36 6307.45   26.25
#Mann= 3 ,-1 , 0
 2725.39     .15       0 4964.07    .032       0 5078.11     .15       0
#XS Ineff= 2 ,-1
  2725.4 4990.33   28.47 5008.41 5020.33   26.72
Permanent Ineff=
       F       F
#Block Obstruct= 1 ,-1
 4041.46 4529.27   30.35
Bank Sta=4964.07,5028.24
XS Rating Curve= 0
Exp/Cntr=.5,.3

Type RM Length L Ch R = 2 ,69427   ,,,
BEGIN DESCRIPTION:
Dupont Street
END DESCRIPTION:
Bridge Culvert--1,0,-1,-1, 0
Deck Dist Width WeirC Skew NumUp NumDn MinLoCord MaxHiCord MaxSubmerge Is_Ogee
78,22,2.6,0, 8, 8, , , .95, 0, 0,0,,
    2700    3490    4440 4956.55 5012.42 5055.34    5310    6310
    35.4    32.6    31.7   29.46   29.17   28.88   28.62   27.37
                                                                
    2700    3490    4440 4956.55 5012.42 5055.34    5310    6310
    35.4    32.6    31.7   29.46   29.17   28.88   28.62   27.37
                                                                
Multiple Barrel Culv=1,4,,22,.012,.5,1,1,1,22.22,22.62, 2,Culvert #1  , 0 ,78
 4995.75 4996.26 5002.35 5000.82
Culvert Bottom n=.012
BC Design=,, 0 ,, 0 ,,,,,,
BC HTab HWMax=34.41

Type RM Length L Ch R = 1 ,69356.69,187.35,196.35,168.51
BEGIN DESCRIPTION:
xsec extended to basin boundaries (left and right)
END DESCRIPTION:
XS GIS Cut Line= 5
     3189867.835    13812578.591     3189911.086    13811770.443
     3189991.516    13810267.641     3189956.007    13810190.705
     3190022.974    13809002.179
#Sta/Elev= 30
 2641.77   34.13 3569.64   31.32 3678.95   31.46 3715.11   32.47 3737.19   29.99
 3967.28   31.28 4195.79   30.65 4225.84    31.3 4956.03   28.01  4986.7   26.97
 4995.65   22.48 4998.53   22.38  5001.9   22.48 5008.41   25.88  5013.3    26.3
 5040.76   25.49 5100.18   25.79 5128.38   28.01 5275.46    25.7 5339.57   26.04
 5356.96   27.27 5420.56   26.06 5562.28   28.09 5622.39   27.05 5924.99   27.28
 5976.16   25.41 6029.75   27.49 6063.05   27.74 6146.05   27.91 6231.17   26.34
#Mann= 3 ,-1 , 0
 2641.77     .15       0 4956.03    .032       0  5013.3     .15       0
#XS Ineff= 2 , 0
       0 4989.74   28.48    5006       0    26.3
Permanent Ineff=
       F       F
#Block Obstruct= 1 ,-1
 3644.72  3937.4   30.73
Bank Sta=4956.03,5013.3
XS Rating Curve= 0
Exp/Cntr=.5,.3

Type RM Length L Ch R = 1 ,69160.34,282.96,295.26,327.22
BEGIN DESCRIPTION:
xsec extended to basin boundaries (left and right)
END DESCRIPTION:
XS GIS Cut Line= 5
      3190013.38    13812585.972     3190063.353    13811718.136
     3190153.489    13810152.848     3190128.549    13810101.581
     3190130.767    13809005.257
#Sta/Elev= 30
 2529.74   34.03 2954.58   32.47 3135.99   32.34 3194.39   32.83 3360.61   31.62
 3588.26   32.08 3638.57   30.37 3857.18   31.76  4029.2   30.63 4136.03   31.86
 4682.09   28.36 4862.07    28.2    4984   26.97 4995.31   25.53 4997.46   24.24
 5003.53   22.38    5017   25.88  5018.3    26.7    5038   27.78 5244.37   27.86
  5372.4   26.91  5448.7   28.08 5531.25   26.37 5688.91   27.53 5788.45   27.41
  5868.7   25.32 5909.49   27.45  5988.7   28.25 6083.32   27.57 6120.23   26.41
#Mann= 3 ,-1 , 0
 2529.74     .15       0 4862.07    .032       0    5038     .15       0
Bank Sta=4862.07,5038
XS Rating Curve= 0
Exp/Cntr=.3,.1

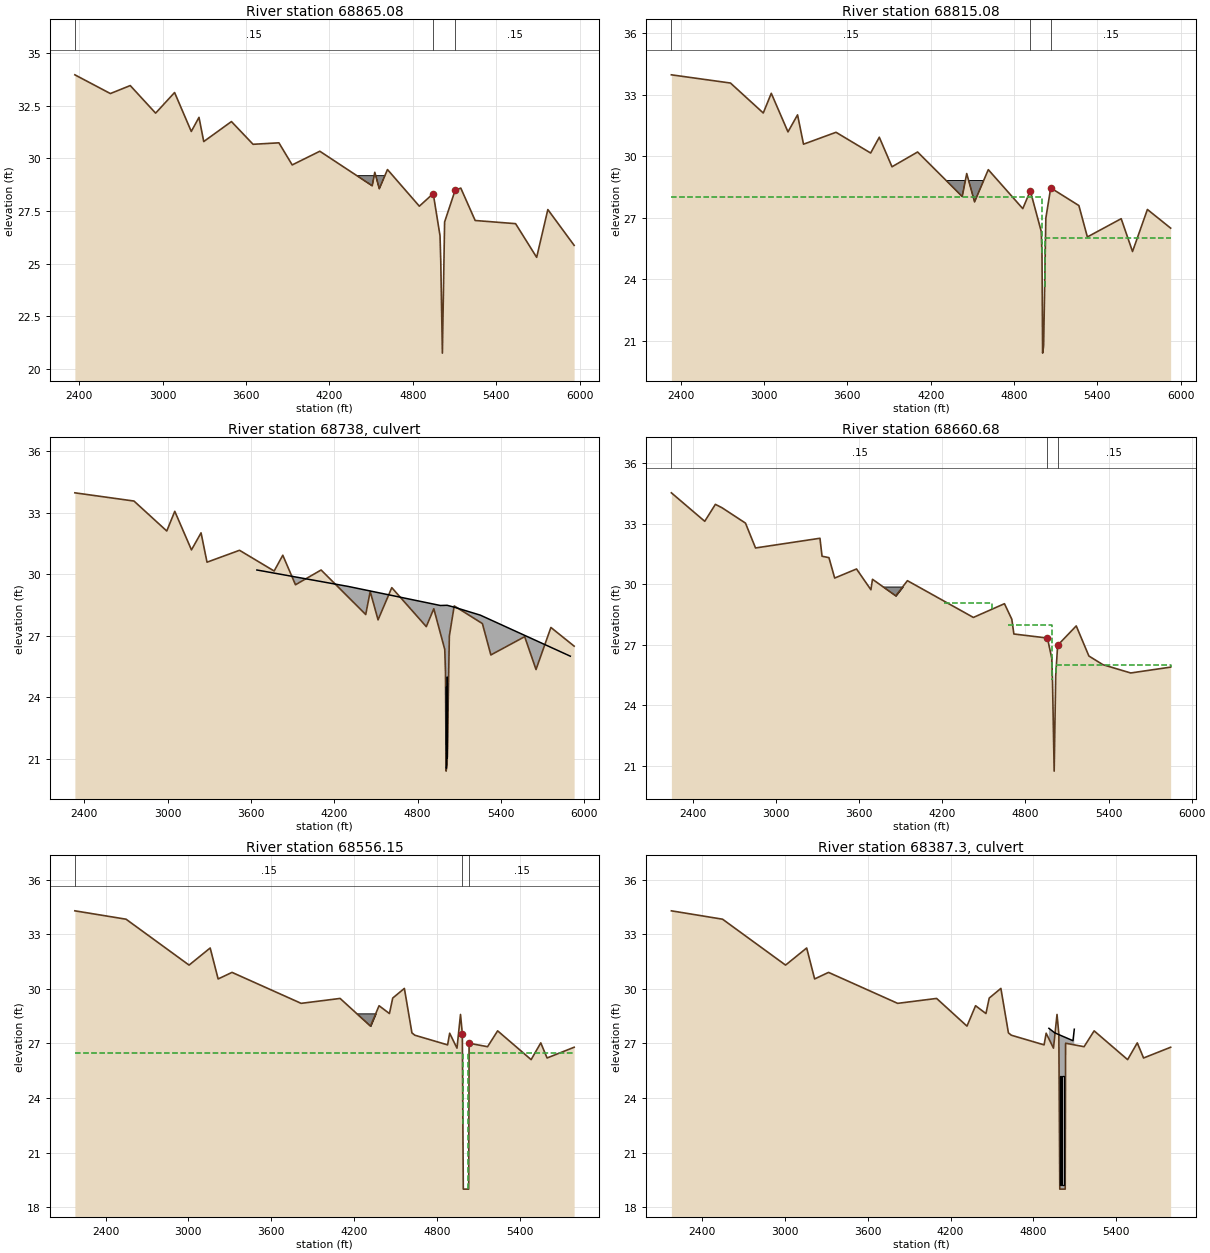
Type RM Length L Ch R = 1 ,68865.08,55.22,50,58.99
BEGIN DESCRIPTION:
xsec extended to basin boundaries (left and right)
END DESCRIPTION:
XS GIS Cut Line= 5
     3190261.054    13812598.533     3190302.059    13811753.444
       3190388.8    13809965.716     3190376.013    13809945.313
     3190426.426    13809013.698
#Sta/Elev= 30
 2368.15   33.97 2623.64   33.08 2766.59   33.46 2949.19   32.15 3085.74   33.13
 3205.88   31.28 3261.33   31.95  3295.6    30.8 3494.84   31.75 3650.42   30.67
 3836.53   30.74 3932.14   29.69 4130.87   30.34 4507.85    28.7 4526.53   29.34
 4559.01   28.56 4617.85   29.47 4847.13   27.73 4947.01   28.33 4995.85   26.33
 5001.16   25.15 5012.95   20.75 5028.92   26.98  5104.4   28.48 5145.43   28.59
 5248.84   27.05  5539.7    26.9 5691.36    25.3 5771.84   27.57 5961.12   25.87
#Mann= 3 ,-1 , 0
 2368.15     .15       0 4947.01    .032       0  5104.4     .15       0
#Block Obstruct= 2 ,-1
 4308.94 4608.13   28.96    4400 4621.14   29.18
Bank Sta=4947.01,5104.4
XS Rating Curve= 0
Exp/Cntr=.5,.3

Type RM Length L Ch R = 1 ,68815.08,170.2,154.4,142.41
BEGIN DESCRIPTION:
xsec extended to basin boundaries (left and right)
END DESCRIPTION:
XS GIS Cut Line= 5
     3190288.877    13812599.944     3190336.056    13811770.443
      3190439.46    13809952.395     3190424.428     13809928.41
     3190475.697    13809015.105
#Sta/Elev= 30
  2332.6   33.96 2758.08   33.56 2994.23    32.1 3051.92   33.06 3172.11   31.18
 3241.16   32.01 3284.05   30.58 3518.03   31.16 3767.43   30.15  3829.6   30.92
 3921.08   29.48 4105.45    30.2 4426.75   28.03 4459.09   29.15 4515.68   27.77
 4614.44   29.34 4862.87   27.44 4916.93   28.31 4995.85   26.33 5001.16    25.2
 5005.56    20.4 5012.95   20.75 5028.92   26.98    5064   28.45 5266.74   27.59
 5327.87   26.06 5571.37   26.95 5653.03   25.35 5760.14    27.4 5927.48   26.49
#Mann= 3 ,-1 , 0
  2332.6     .15       0 4916.93    .032       0    5064     .15       0
#XS Ineff= 2 , 0
       0 5001.16      28 5020.36       0      26
Permanent Ineff=
       F       F
#Block Obstruct= 1 ,-1
 4289.43 4634.15   28.81
Bank Sta=4916.93,5064
XS Rating Curve= 0
Exp/Cntr=.5,.3

Type RM Length L Ch R = 2 ,68738   ,,,
BEGIN DESCRIPTION:
Sinclair
END DESCRIPTION:
Bridge Culvert--1,0,-1,-1, 0
Deck Dist Width WeirC Skew NumUp NumDn MinLoCord MaxHiCord MaxSubmerge Is_Ogee
70,25,2.6,0, 7, 7, , , .95, 0, 0,0,,
    3643    4300 4964.81 5012.86  5057.9    5252    5900
    30.2    29.4   28.47   28.48    28.4      28      26
                                                        
    3643    4300 4964.81 5012.86  5057.9    5252    5900
    30.2    29.4   28.47   28.48    28.4      28      26
                                                        
Culvert=1,4,,40,.012,.5,1,1,1,20.53,5008,21.18,5004,Culvert #1  , 0 ,63
Culvert Bottom n=.012
Culvert=1,4,,40,.012,.5,1,1,1,21,5014,21.18,5010,Culvert #2  , 0 ,63
Culvert Bottom n=.012
BC Design=,, 0 ,, 0 ,,,,,,
BC HTab HWMax=33.96

Type RM Length L Ch R = 1 ,68660.68,124.15,104.53,108
BEGIN DESCRIPTION:
xsec extended to basin boundaries (left and right)
END DESCRIPTION:
XS GIS Cut Line= 5
     3190437.238    13812607.468     3190510.435    13811197.181
     3190578.302    13809889.586     3190543.427    13809821.387
     3190593.895     13809018.48
#Sta/Elev= 30
 2245.79   34.53 2486.58   33.12 2563.39   33.96 2611.51   33.79 2780.52   33.03
 2853.02    31.8 3317.91   32.28 3332.93   31.39 3382.76   31.32 3424.17   30.31
 3581.73   30.76 3685.52   29.73 3696.87   30.25 3864.84   29.43 3949.07   30.18
 4424.98   28.36 4649.25   29.04 4702.34   28.27 4717.16   27.54 4959.35   27.34
 4990.85   26.33 4996.16   25.15 5007.95   20.75 5019.15   25.48    5033   26.98
 5167.27   27.94 5258.47   26.45 5359.86   26.02 5560.29   25.61 5848.42    25.9
#Mann= 3 ,-1 , 0
 2245.79     .15       0 4959.35    .032       0    5033     .15       0
#XS Ineff= 3 ,-1
  4211.6    4562   29.07 4675.76 4995.76   28.01 5020.36 5848.42      26
Permanent Ineff=
       F       F       F
#Block Obstruct= 1 ,-1
  3756.1  3925.2   29.89
Bank Sta=4959.35,5033
XS Rating Curve= 0
Exp/Cntr=.5,.3

Type RM Length L Ch R = 1 ,68556.15,294.52,337.75,208.14
BEGIN DESCRIPTION:
xsec extended to basin boundaries (left and right)
END DESCRIPTION:
XS GIS Cut Line= 5
     3190573.834    13812614.396     3190624.542    13811197.181
     3190673.848    13809819.147     3190634.541    13809788.613
     3190681.103     13809020.97
#Sta/Elev= 30
 2177.82   34.28 2548.57   33.82 3004.88    31.3 3157.73   32.24 3215.38   30.54
 3315.99    30.9 3816.57    29.2 4098.69   29.47 4318.64   27.95 4380.87   29.07
 4456.03   28.64 4479.73   29.49 4564.21   30.02 4618.83   27.58  4639.9   27.45
 4877.17   26.92 4892.16   27.56 4945.15   26.74 4970.74   28.59 4983.98   27.52
    4984   27.34 4990.85      19    5030      19 5032.85   27.01 5166.72   26.82
 5239.58   27.69 5482.12   26.11 5552.03   27.03 5597.66    26.2 5793.68   26.79
#Mann= 3 ,-1 , 0
 2177.82     .15       0    4984    .032       0 5032.85     .15       0
#XS Ineff= 2 , 0
       0    4988    26.5    5024       0    26.5
Permanent Ineff=
       F       F
#Block Obstruct= 1 ,-1
 4139.84 4380.49   28.65
Bank Sta=4983.98,5032.85
XS Rating Curve= 0
Exp/Cntr=.5,.3

Type RM Length L Ch R = 2 ,68387.3 ,,,
BEGIN DESCRIPTION:
Spencer Highway
END DESCRIPTION:
Bridge Culvert--1,0,-1,-1, 0
Deck Dist Width WeirC Skew NumUp NumDn MinLoCord MaxHiCord MaxSubmerge Is_Ogee
80,167,2.6,0, 4, 4, , , .95, 0, 0,0,,
4912.0414954.298 5086.35 5095.82
   27.83   27.58   27.15   27.78
                                
4912.0414954.298 5086.35 5095.82
   27.83   27.58   27.15   27.78
                                
Multiple Barrel Culv=2,6,10,167,.012,.5,1,58,2,19.21,19.21, 2,Culvert #1  , 0 ,80
    4998    4992    5015    5009
Culvert Bottom n=.012
BC Design=,, 0 ,, 0 ,,,,,,
BC HTab HWMax=34.28

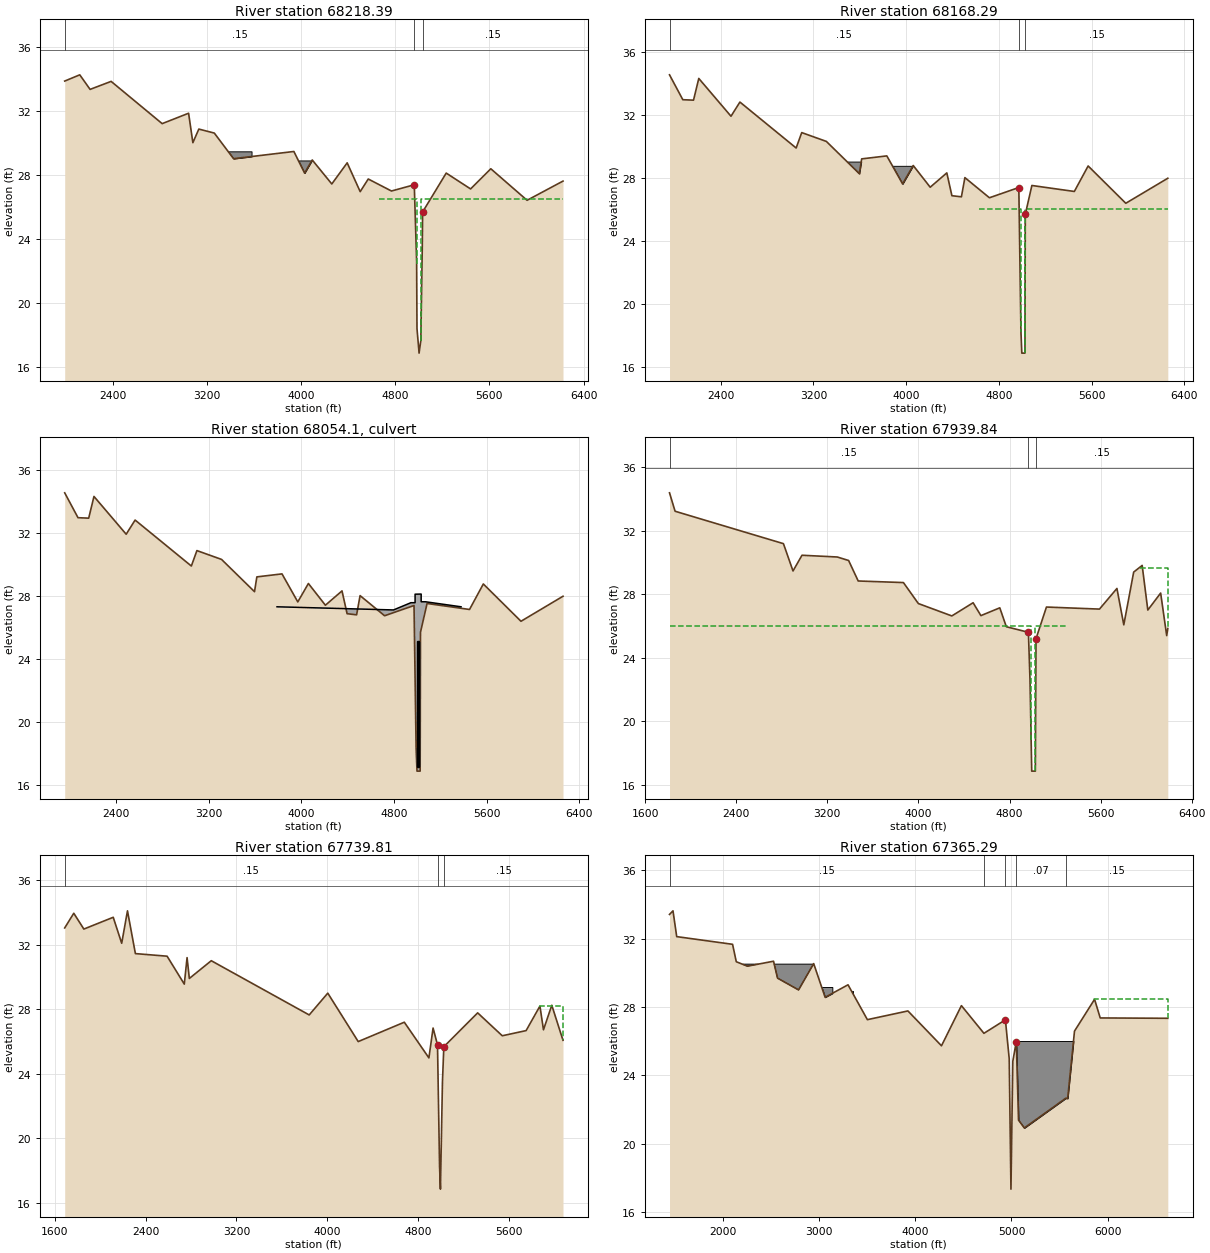
Type RM Length L Ch R = 1 ,68218.39,71.36,50.11,38.97
BEGIN DESCRIPTION:
xsec extended to basin boundaries (left and right)
END DESCRIPTION:
XS GIS Cut Line= 5
     3190754.424    13812623.554     3190840.077    13811247.895
     3190940.822    13809629.851     3190915.619    13809583.306
     3190751.724    13808413.887
#Sta/Elev= 30
 1992.26   33.86 2120.28   34.25 2207.85   33.34 2386.58   33.84 2820.21    31.2
  3044.7   31.85 3081.13   30.01 3131.74   30.86 3263.25   30.61  3426.8   29.01
 3939.15   29.46 4030.29   28.11 4095.17   28.93 4261.37   27.43 4391.97   28.75
 4502.58   26.95 4570.99   27.74 4768.28   26.99    4962   27.38    4982    22.6
 4985.06    18.4 5002.88   16.86 5017.61   17.65    5030    23.5 5032.91   25.68
 5233.32   28.11 5440.53   27.12 5612.17   28.38 5920.43   26.41 6225.54   27.61
#Mann= 3 ,-1 , 0
 1992.26     .15       0    4962    .032       0 5032.91     .15       0
#XS Ineff= 3 ,-1
 4153.58 4378.84   28.26  4658.8 4982.23    26.5    5017 6225.54    26.5
Permanent Ineff=
       F       F       F
#Block Obstruct= 2 ,-1
 3162.54 3579.51   29.47 3968.17 4093.73    28.9
Bank Sta=4962,5032.91
XS Rating Curve= 0
Exp/Cntr=.5,.3

Type RM Length L Ch R = 1 ,68168.29,284.88,228.44,230.95
BEGIN DESCRIPTION:
xsec extended to basin boundaries (left and right)
END DESCRIPTION:
XS GIS Cut Line= 5
      3190850.33    13812628.418     3190916.148    13811222.538
     3190991.266    13809618.005     3190964.692    13809568.926
     3190757.723    13808356.166
#Sta/Elev= 30
 1957.88   34.54 2072.65   32.96 2164.97   32.93 2210.45   34.31 2488.35   31.91
 2565.41   32.81 3050.71   29.89 3098.72   30.87 3311.22   30.31 3595.72   28.26
 3615.95    29.2 3832.92   29.39 3969.24   27.61 4060.71   28.78 4207.39    27.4
 4350.73   28.31 4394.59   26.86 4476.77   26.79 4506.72   28.01 4718.27   26.73
 4972.09   27.38 4990.18   18.28 4997.88   16.86    5025   16.86 5027.91   25.68
 5084.79   27.51 5451.08   27.13 5570.21   28.75 5895.12   26.38  6257.7   27.97
#Mann= 3 ,-1 , 0
 1957.88     .15       0 4972.09    .032       0 5027.91     .15       0
#XS Ineff= 3 ,-1
 4106.09 4348.89   28.29 4625.26 4990.44      26    5023  6257.7      26
Permanent Ineff=
       F       F       F
#Block Obstruct= 2 ,-1
 3413.01 3808.65   29.03 3828.82 4059.63   28.76
Bank Sta=4972.09,5027.91
XS Rating Curve= 0
Exp/Cntr=.5,.3

Type RM Length L Ch R = 2 ,68054.1 ,,,
BEGIN DESCRIPTION:
Dedman Street
END DESCRIPTION:
Bridge Culvert--1,0,-1,-1, 0
Deck Dist Width WeirC Skew NumUp NumDn MinLoCord MaxHiCord MaxSubmerge Is_Ogee
55,98,2.6,0, 9, 9, , , .95, 0, 0,0,,
    3790    4795 4945.36 4981.24 4981.24 5033.74 5033.74 5070.61    5378
    27.3    27.1   27.56   27.56    28.1   28.11   27.62   27.62    27.3
                                                                        
    3790    4795 4945.36 4981.24 4981.24 5033.74 5033.74 5070.61    5378
    27.3    27.1   27.56   27.56    28.1   28.11   27.62   27.62    27.3
                                                                        
BR Coef=-1 , 0 , 0 ,, 0 ,,,.8,-1,,0,
WSPro=,,,, 1 ,,,, 0 ,,,, 0 ,,,,-1 ,-1 ,-1 , 0 , 0 , 0 , 0 , 0
Multiple Barrel Culv=2,8,10,98,.012,.2,1,8,1,17.12,17.12, 2,Culvert #1  , 0 ,55
 5000.19 5000.195012.9185012.918
Culvert Bottom n=.012
BC Design=,, 0 ,, 0 ,,,,,,
BC HTab HWMax=34.54

Type RM Length L Ch R = 1 ,67939.84,228.4,200.03,203.65
BEGIN DESCRIPTION:
xsec extended to basin boundaries (left and right)
END DESCRIPTION:
XS GIS Cut Line= 5
     3191114.185    13812641.799     3191169.719    13811070.395
     3191223.223     13809556.41     3191118.012    13809385.443
     3191009.265    13808302.033
#Sta/Elev= 30
 1813.61   34.38 1862.58   33.22 2814.25   31.18 2898.34   29.46 2977.26   30.45
  3287.1   30.34 3386.82   30.12 3470.96   28.83 3868.22   28.73 3999.28   27.41
 4293.42   26.63 4480.29   27.46 4548.72   26.65  4714.6   27.14 4772.06   25.95
    4966    25.6    4980    22.6 4995.18   16.86    5027   16.86 5032.91    25.2
 5124.53   27.19  5590.3   27.06 5743.54   28.36 5803.84   26.07 5890.68   29.39
 5965.21   29.81 6014.89      27 6127.63   28.07 6180.72   25.39 6190.53   25.84
#Mann= 3 ,-1 , 0
 1813.61     .15       0    4966    .032       0 5032.91     .15       0
#XS Ineff= 3 ,-1
 1813.61    4990      26    5023 5316.79      26 5948.81  6474.4   29.64
Permanent Ineff=
       F       F       F
Bank Sta=4966,5032.91
XS Rating Curve= 0
Exp/Cntr=.5,.3

Type RM Length L Ch R = 1 ,67739.81,464.61,374.52,263.87
BEGIN DESCRIPTION:
xsec extended to basin boundaries (left and right)
END DESCRIPTION:
XS GIS Cut Line= 5
     3191336.062    13812659.893     3191372.576    13811070.395
     3191409.179     13809476.98     3191310.534    13809316.682
     3191173.886    13808306.238
#Sta/Elev= 30
 1686.53   33.04 1766.45   33.95 1855.38   32.97  2114.1    33.7 2188.82   32.09
 2239.78    34.1 2309.57   31.45 2588.86   31.29 2740.55   29.56 2764.92    31.2
 2784.97   29.91 2978.22   31.01 3841.32   27.65 4005.08      29 4273.36      26
  4679.5    27.2 4896.31   24.99 4933.07   26.84 4972.09    25.8 4990.18   18.28
 4997.88   16.86 5015.69    23.5 5027.91   25.68 5325.88   27.78 5542.76   26.36
    5753   26.68 5874.84    28.2 5906.04   26.73 5979.31   28.25 6078.14   26.08
#Mann= 3 ,-1 , 0
 1686.53     .15       0 4972.09    .032       0 5027.91     .15       0
#XS Ineff= 2 ,-1
 3546.08 3989.76    28.3 5872.24 6319.04   28.22
Permanent Ineff=
       F       F
Bank Sta=4972.09,5027.91
XS Rating Curve= 0
Exp/Cntr=.3,.1

Type RM Length L Ch R = 1 ,67365.29,18.42,15.07,15.19
BEGIN DESCRIPTION:
xsec extended to basin boundaries (left and right)
END DESCRIPTION:
XS GIS Cut Line= 6
     3191641.302    13812676.474     3191711.066     13811269.29
     3191803.288    13809409.111     3191672.158    13809183.985
     3191645.009    13809149.632 3191066.845274613807654.7557794
#Sta/Elev= 30
 1446.09   33.41 1482.19   33.62 1520.87   32.11 2101.41   31.66 2139.96   30.64
 2255.62   30.38  2527.1   30.67 2568.74   29.68 2787.21   28.99 2944.47   30.53
 3063.24   28.56 3301.19   29.29 3502.42   27.25 3923.68   27.76 4272.48   25.72
 4479.63   28.07 4713.54   26.45 4936.68   27.24 4976.31   24.96 4994.44   17.33
 5013.69   24.81 5049.81   25.97    5073   21.37 5133.35   20.91 5563.97   22.65
 5584.08   22.64 5654.86   26.58 5863.48   28.44 5922.05   27.35 6624.57   27.33
#Mann= 5 ,-1 , 0
 1446.09     .15       0 4713.54     .07       0 4936.68    .032       0
 5049.81     .07       0 5563.97     .15       0
#XS Ineff= 1 ,-1
 5860.07 6747.44   28.43
Permanent Ineff=
       F
#Block Obstruct= 4 ,-1
 2208.51 2944.67    30.5    3000 3138.21   29.16 3300.34 3354.95   28.92
 5049.28 5672.54      26
Bank Sta=4936.68,5049.81
XS Rating Curve= 0
Exp/Cntr=.3,.1