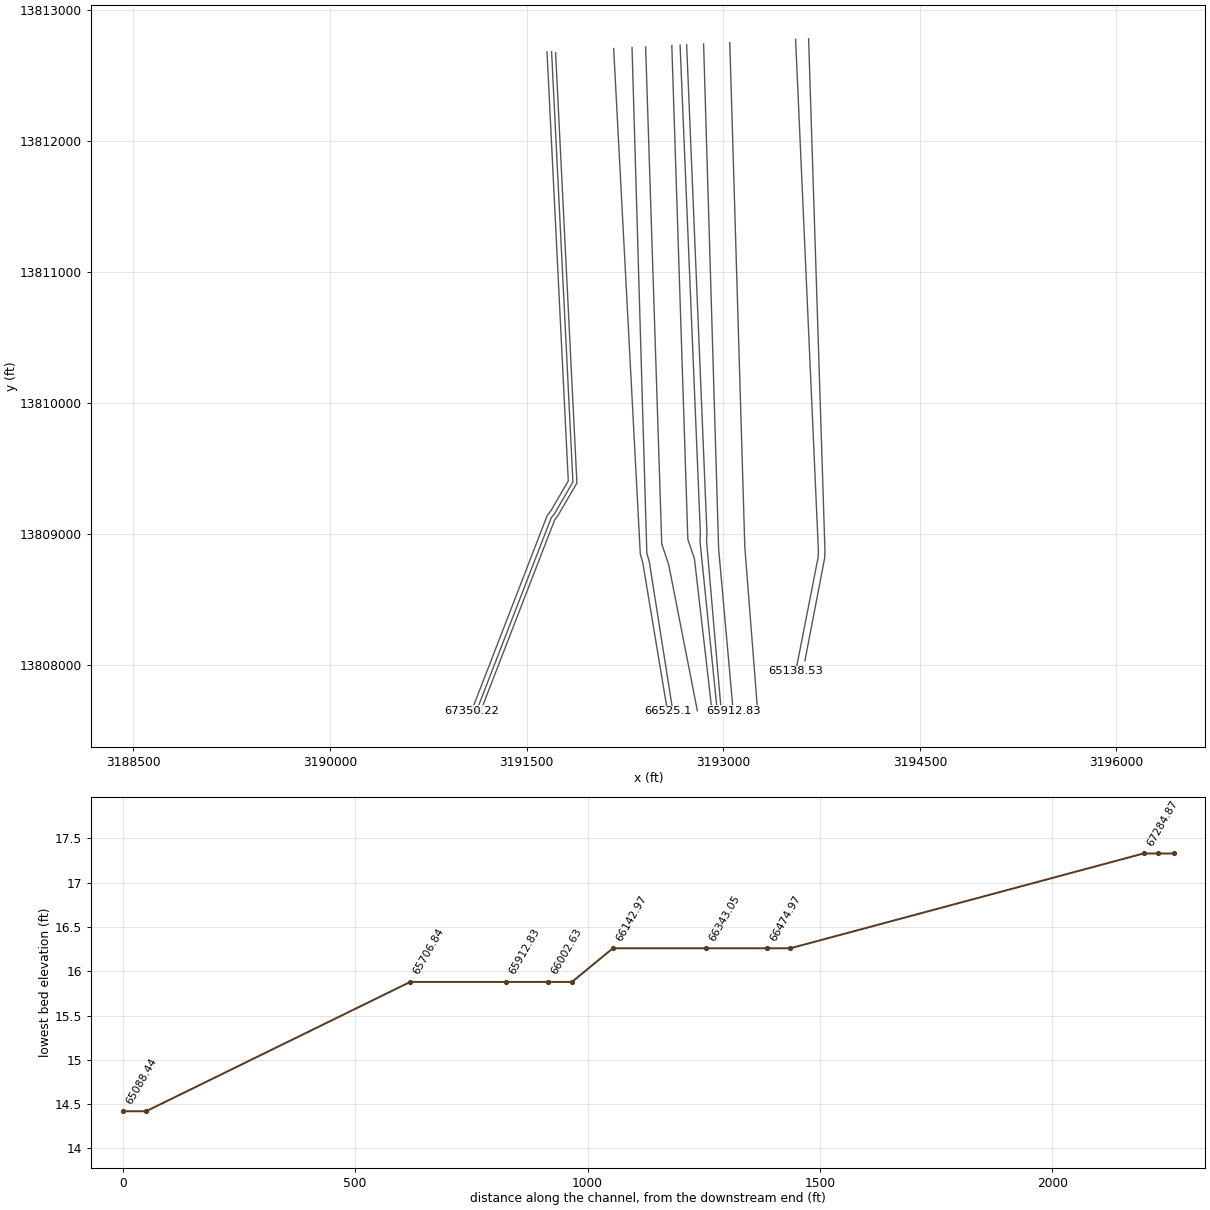
HEC-RAS study B100-00-00.prj: B100-00-00

--- B100-00-00.g01 (geometry) --- (continued)

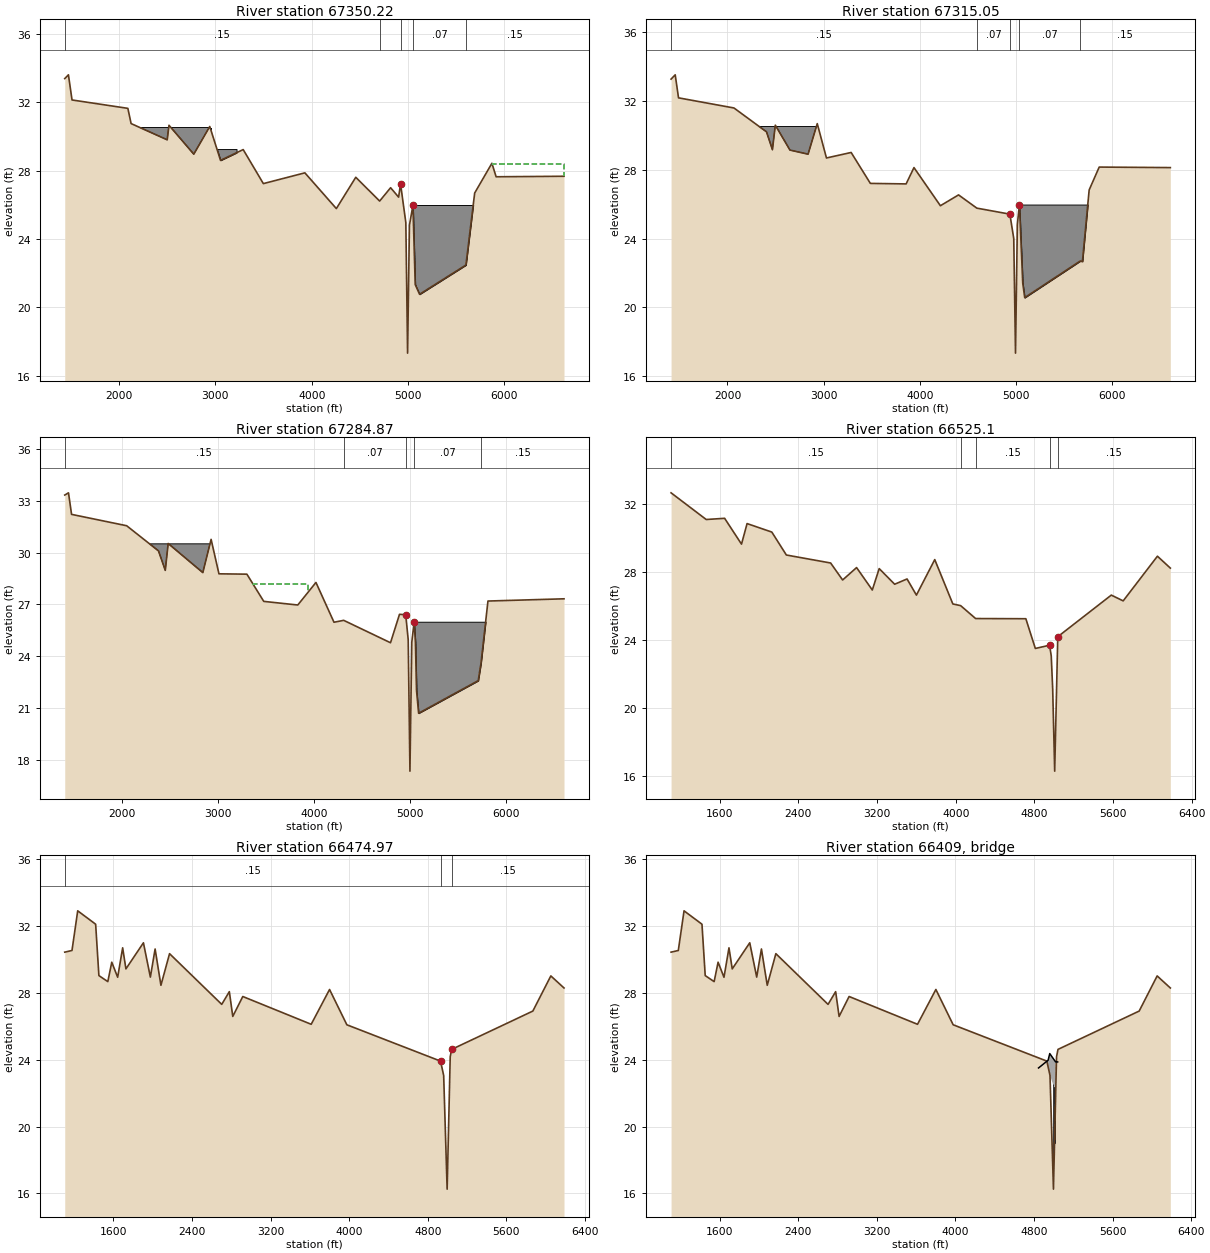
Type RM Length L Ch R = 1 ,67350.22,42.97,35.17,35.65
BEGIN DESCRIPTION:
xsec extended to basin boundaries (left and right)
END DESCRIPTION:
XS GIS Cut Line= 6
      3191656.28    13812677.288     3191726.047    13811270.033
      3191818.49    13809405.408     3191684.585    13809175.518
     3191658.181    13809142.107 3191082.068492213807653.2978408
#Sta/Elev= 30
 1436.83   33.38    1475    33.6 1512.42   32.13 2091.71   31.64 2125.37   30.75
    2500    29.8 2518.66   30.65 2775.79   28.96 2941.59   30.58 3053.43    28.6
 3288.51   29.23 3497.78   27.24 3928.69   27.87 4255.27   25.78 4456.86   27.61
 4704.56   26.22 4818.16      27 4901.25   26.45  4921.6   27.22 4976.31   24.96
 4994.44   17.33 5013.69   24.81 5049.81   25.97 5073.65   21.34 5118.74   20.77
 5599.83   22.48 5690.65   26.69 5869.43   28.43 5913.18   27.64 6617.75   27.67
#Mann= 5 ,-1 , 0
 1436.83     .15       0 4704.56     .07       0  4921.6    .032       0
 5049.81     .07       0 5599.83     .15       0
#XS Ineff= 1 ,-1
 5873.72 6863.48   28.39
Permanent Ineff=
       F
#Block Obstruct= 3 ,-1
 2166.08 2949.35   30.52 2951.22 3219.51   29.26 5048.61 5702.04   25.99
Bank Sta=4921.6,5049.81
XS Rating Curve= 0
Exp/Cntr=.3,.1

Type RM Length L Ch R = 1 ,67315.05,36.83,30.17,30.56
BEGIN DESCRIPTION:
xsec extended to basin boundaries (left and right)
END DESCRIPTION:
XS GIS Cut Line= 6
     3191691.229    13812679.186     3191761.004    13811271.766
     3191853.961    13809396.767     3191713.581    13809155.761
     3191688.916     13809124.55 3191116.876449613807646.2638247
#Sta/Elev= 30
 1413.85   33.28 1456.86   33.53 1491.34   32.19 2067.72    31.6 2405.94   30.21
 2467.54   29.17 2497.58    30.6 2649.65   29.15 2838.07   28.91 2933.51   30.69
 3029.18   28.69 3285.82   29.01 3485.58   27.21 3857.39   27.18 3939.02   28.13
 4213.75   25.91 4402.35   26.54 4592.59   25.77    4936   25.42 4976.31      24
 4994.44   17.33 5013.69   24.81    5035   25.97 5069.66   21.41  5090.2   20.56
 5667.09   22.69 5690.32   22.67 5760.26   26.83 5864.69   28.16  6604.1   28.13
#Mann= 5 ,-1 , 0
 1413.85     .15       0 4592.59     .07       0    4936    .032       0
    5035     .07       0 5667.09     .15       0
#Block Obstruct= 2 ,-1
 1883.39 2931.68   30.52 5034.84 5768.07   25.98
Bank Sta=4936,5035
XS Rating Curve= 0
Exp/Cntr=.3,.1

Type RM Length L Ch R = 1 ,67284.87,555.3,759.78,1040.97
BEGIN DESCRIPTION:
xsec extended to basin boundaries (left and right)
END DESCRIPTION:
XS GIS Cut Line= 6
     3191721.592    13812672.604     3191790.967    13811273.252
     3191884.365    13809389.361     3191738.435    13809138.826
     3191715.261    13809109.501 3191143.175729113807631.0993488
#Sta/Elev= 30
 1404.28   33.35 1443.22   33.48 1475.18   32.23 2049.06   31.57 2380.67   30.11
 2451.38   28.98 2481.42   30.54 2842.24   28.85 2928.48   30.78  3010.3   28.78
  3301.3   28.76 3477.04   27.18 3831.36   26.97 4020.55   28.28 4208.41   25.97
 4309.47   26.08 4796.98   24.78 4890.78   26.43 4955.41   26.41 4981.31   24.96
 4999.44   17.33 5018.69   24.81    5043   25.97  5056.6    24.8 5067.85   22.02
 5089.72   20.69 5710.52   22.58 5739.71    23.6 5811.99    27.2  6604.1   27.33
#Mann= 5 ,-1 , 0
 1404.28     .15       0 4309.47     .07       0 4955.41    .032       0
    5043     .07       0 5739.71     .15       0
#XS Ineff= 1 ,-1
  3368.6 3941.98    28.2
Permanent Ineff=
       F
#Block Obstruct= 2 ,-1
 1954.06 2919.91   30.52 5043.45 5799.51      26
Bank Sta=4955.41,5043
XS Rating Curve= 0
Exp/Cntr=.3,.1

Type RM Length L Ch R = 1 ,66525.1 ,64.31,50.13,46.53
BEGIN DESCRIPTION:
xsec extended to basin boundaries (left and right)
END DESCRIPTION:
XS GIS Cut Line= 5
     3192164.699    13812703.573     3192255.098    13810987.137
     3192367.833    13808846.632     3192386.875    13808780.767
     3192575.076    13807649.267
#Sta/Elev= 30
 1105.26   32.64 1462.54   31.07 1650.01   31.14 1821.61   29.62 1878.28   30.83
 2130.05   30.33 2277.73   28.98 2728.03   28.51  2850.1   27.51 2992.03   28.24
 3151.86   26.92    3222   28.18 3379.18   27.26 3505.37   27.57 3600.55   26.62
 3787.13   28.71 3971.01    26.1 4050.44      26 4202.78   25.24 4713.56   25.23
 4810.04   23.48 4954.95   23.67 4971.71   23.05 4986.47   21.12 5006.93   16.26
 5038.29   24.17 5582.68   26.62 5703.55   26.28  6051.9   28.91 6183.15   28.21
#Mann= 5 ,-1 , 0
 1105.26     .15       0 4050.44     .07       0 4202.78     .15       0
 4954.95    .032       0 5038.29     .15       0
#XS Ineff= 1 ,-1
 2686.01 3798.63   28.31
Permanent Ineff=
       F
#Block Obstruct= 2 , 0
                         6060.73           28.96
Bank Sta=4954.95,5038.29
XS Rating Curve= 0
Exp/Cntr=.5,.3

Type RM Length L Ch R = 1 ,66474.97,120.29,131.92,160.97
BEGIN DESCRIPTION:
xsec extended to basin boundaries (left and right)
END DESCRIPTION:
XS GIS Cut Line= 5
     3192304.792    13812710.675     3192336.369    13811631.507
     3192417.626     13808854.43     3192436.117     13808790.47
     3192615.941    13807649.616
#Sta/Elev= 30
 1106.63   30.42 1180.25   30.52 1238.57   32.89    1421   32.09 1453.97   29.02
 1544.74   28.66 1585.01   29.82 1644.91   28.92 1695.77   30.68 1728.96   29.42
 1907.03   30.98 1977.68   28.93 2025.88   30.61 2085.05   28.44 2172.77   30.33
 2703.74    27.3 2781.07   28.06 2816.11   26.58 2917.95   27.77 3613.95   26.11
  3800.7   28.19 3976.75   26.08 4929.71   23.91 4961.71   23.05 4996.93   16.26
 5028.29   24.17 5043.06   24.61 5868.98    26.9 6051.96      29 6186.04   28.28
#Mann= 3 ,-1 , 0
 1106.63     .15       0 4929.71    .032       0 5043.06     .15       0
#XS Ineff= 1 ,-1
 2453.92 3798.63   28.16
Permanent Ineff=
       F
#Block Obstruct= 2 , 0
         2182.19      30 6052.02              29
Bank Sta=4929.71,5043.06
XS Rating Curve= 0
Exp/Cntr=.5,.3

Type RM Length L Ch R = 3 ,66409   ,,,
BEGIN DESCRIPTION:
Vista
END DESCRIPTION:
Bridge Culvert--1,0,-1,-1, 0
Deck Dist Width WeirC Skew NumUp NumDn MinLoCord MaxHiCord MaxSubmerge Is_Ogee
47,26,2.6,0, 5, 5, , , .95, 0, 0,0,,
    4845 4942.31 4959.21 5017.77  5039.7
    23.5   23.96   24.36   23.87   23.86
                   22.76   22.27
    4845 4942.31 4959.21 5017.77  5039.7
    23.5   23.96   24.36   23.87   23.86
                   22.76   22.27
Pier Skew, UpSta & Num, DnSta & Num=  ,4988.741, 4 ,4988.741, 4 , 3 , 3 , 0 ,,
       1       1     1.3     1.3
       0   21.39   21.39 22.6869
       1       1     1.3     1.3
       0   21.39   21.39 22.6869
Pier Skew, UpSta & Num, DnSta & Num=  ,5007.881, 4 ,5007.881, 4 , 3 , 3 , 0 ,,
       1       1     1.3     1.3
       0   21.39   21.39   22.69
       1       1     1.3     1.3
       0   21.39   21.39   22.69
BR Coef=-1 , 1 , 0 ,, 0 ,,,.8,0,1.2,0,
WSPro=,,,, 1 ,,,, 0 ,,,, 0 ,,,,-1 ,-1 ,-1 , 0 , 0 , 0 , 0 , 0
BC Design=,, 0 ,, 0 ,,,,,,
BC HTab HWMax=32.89

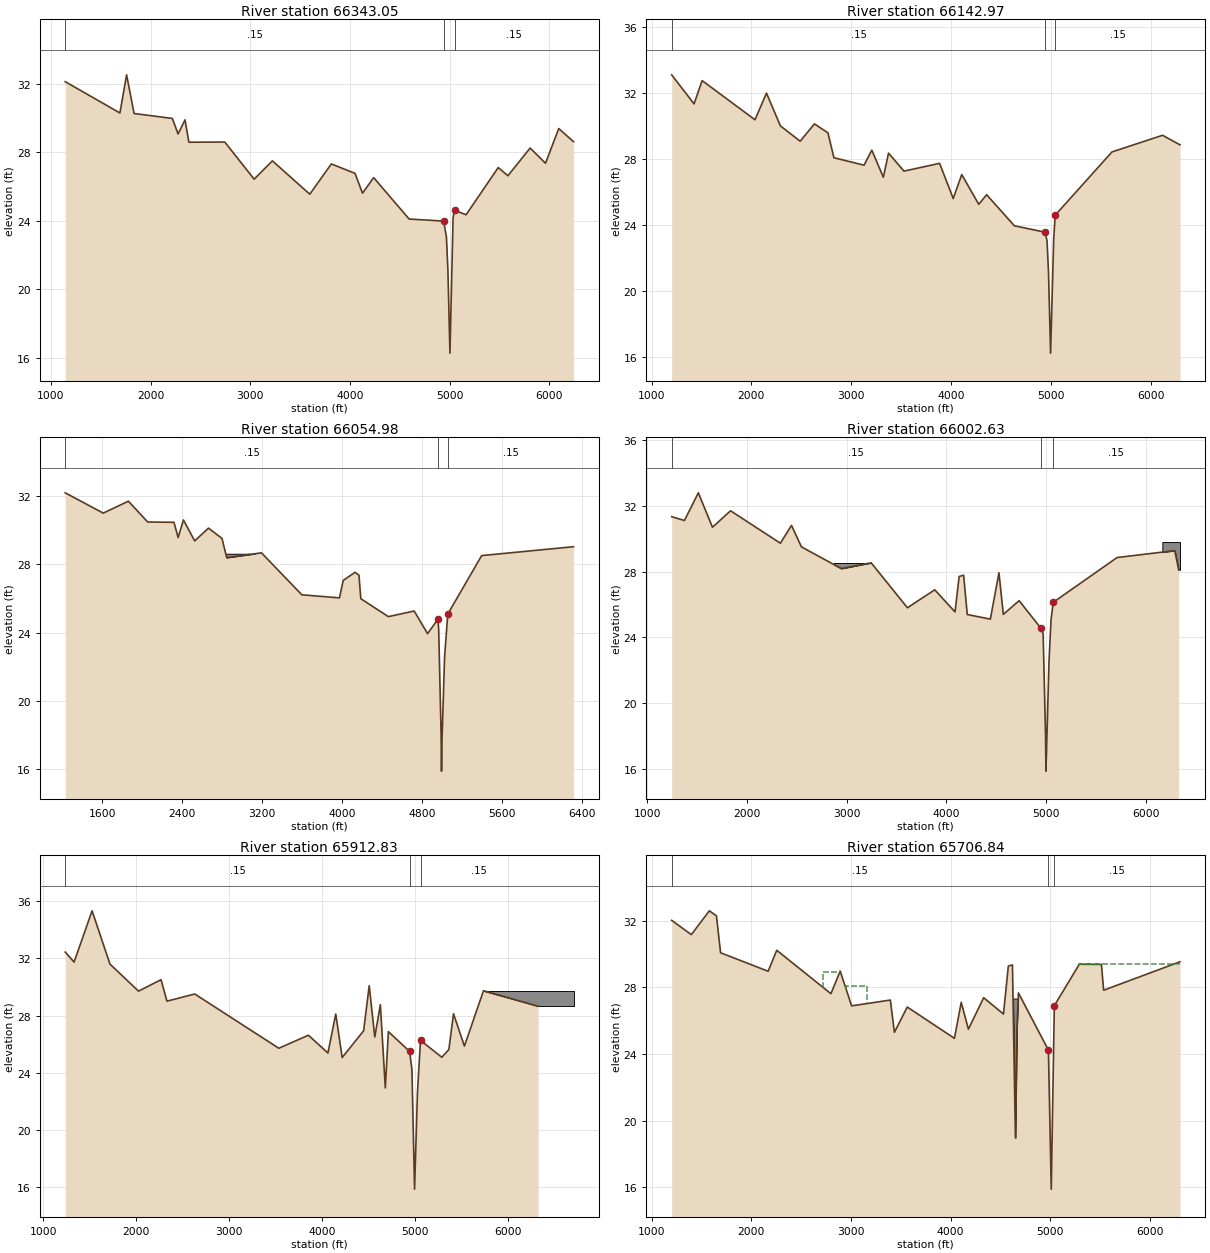
Type RM Length L Ch R = 1 ,66343.05,209.82,200.08,172.46
BEGIN DESCRIPTION:
xsec extended to basin boundaries (left and right)
END DESCRIPTION:
XS GIS Cut Line= 5
     3192408.534    13812715.933     3192443.317     13811643.39
     3192531.525    13808923.501     3192584.366    13808767.329
     3192803.213    13807651.213
#Sta/Elev= 30
 1144.37   32.13 1693.03    30.3 1759.96   32.53 1834.83   30.27 2219.08   29.98
  2275.9   29.07 2345.98    29.9 2384.17   28.59 2744.62    28.6 3038.66   26.43
 3221.54    27.5 3596.75   25.55 3812.53   27.32 4050.04   26.77 4125.08   25.61
 4237.18   26.52 4592.65    24.1  4938.8   23.98 4966.71   23.05 4981.47   21.12
 5001.93   16.26 5033.29   24.17 5048.06   24.61 5163.63   24.35 5486.31   27.11
 5583.18   26.63 5805.93   28.25    5960   27.36 6093.05   29.39 6241.04   28.62
#Mann= 3 ,-1 , 0
 1144.37     .15       0  4938.8    .032       0 5048.06     .15       0
#Block Obstruct= 2 , 0
                         6101.21           29.31
Bank Sta=4938.8,5048.06
XS Rating Curve= 0
Exp/Cntr=.5,.3

Type RM Length L Ch R = 1 ,66142.97,94.44,87.99,52.29
BEGIN DESCRIPTION:
xsec extended to basin boundaries (left and right)
END DESCRIPTION:
XS GIS Cut Line= 5
     3192608.311     13812726.06     3192643.212    13811649.873
     3192730.461    13808959.565     3192781.041    13808810.073
     3192914.382    13807652.162
#Sta/Elev= 30
 1201.48   33.11 1425.63   31.35 1506.81   32.76 2035.78   30.39 2151.25      32
 2290.83   30.02 2488.66   29.09  2631.5   30.14 2766.58    29.6 2826.72   28.09
 3128.85   27.64  3206.5   28.55 3321.87   26.91 3373.62   28.37 3528.59   27.28
 3885.51   27.75 4021.63   25.62 4107.07   27.07 4277.65   25.27 4356.54   25.85
  4634.3   23.97 4942.72   23.58 4961.71   23.05 4976.47   21.12 4996.93   16.26
 5028.29   23.17 5043.06   24.61 5611.71   28.44  6119.1   29.45 6293.34   28.87
#Mann= 3 ,-1 , 0
 1201.48     .15       0 4942.72    .032       0 5043.06     .15       0
#XS Ineff= 1 ,-1
 5778.05 6105.29   28.71
Permanent Ineff=
       F
Bank Sta=4942.72,5043.06
XS Rating Curve= 0
Exp/Cntr=.3,.1

Type RM Length L Ch R = 1 ,66054.98,50.69,52.35,43.96
BEGIN DESCRIPTION:
xsec extended to basin boundaries (left and right)
END DESCRIPTION:
XS GIS Cut Line= 5
     3192671.445     13812729.26     3192714.207    13811700.729
     3192826.181    13809007.453      3192823.05    13808947.167
     3192954.711    13807652.506
#Sta/Elev= 30
 1228.19    32.2 1608.89   31.01 1860.64   31.71 2053.62   30.49  2316.6   30.47
 2358.39   29.58 2411.33   30.61 2524.02   29.38  2661.9   30.13 2797.02   29.53
 2844.24    28.4  3192.2   28.68 3596.21   26.22 3972.68   26.04 4009.85   27.06
 4128.44   27.54 4167.93   27.37 4186.29   25.99 4462.15   24.94 4720.37   25.27
  4854.3   23.94 4957.28   24.78 4965.35   24.23 4989.62   18.05 4993.79   15.88
 4998.13   17.56 5024.65   22.59 5056.59   25.09 5395.92   28.52 6314.92   29.04
#Mann= 3 ,-1 , 0
 1228.19     .15       0 4957.28    .032       0 5056.59     .15       0
#XS Ineff= 1 ,-1
 5395.69 5676.94   28.51
Permanent Ineff=
       F
#Block Obstruct= 1 ,-1
 2793.22 3186.95   28.63
Bank Sta=4957.28,5056.59
XS Rating Curve= 0
Exp/Cntr=.3,.1

Type RM Length L Ch R = 1 ,66002.63,91.2,89.8,91.96
BEGIN DESCRIPTION:
xsec extended to basin boundaries (left and right)
END DESCRIPTION:
XS GIS Cut Line= 5
     3192721.383    13812731.791     3192764.164    13811702.806
     3192876.235    13809007.194     3192873.159    13808947.983
     3192984.951    13807652.764
#Sta/Elev= 30
 1243.15   31.33 1371.37    31.1 1510.62   32.78 1652.58   30.69 1833.91   31.69
  2334.1   29.72 2445.76    30.8 2545.01    29.5 2945.06   28.18 3244.72   28.53
 3608.76    25.8 3882.69   26.89 4086.33   25.55 4127.93    27.7 4172.47   27.78
 4209.38   25.39 4440.86   25.11 4527.14   27.93 4571.03    25.4 4729.57   26.23
 4945.36   24.58 4970.35   24.23 4994.62   18.05 4998.79   15.88 5029.65   22.59
    5050   25.09 5071.68   26.13 5712.52   28.85 6291.15   29.27 6330.29   28.11
#Mann= 3 ,-1 , 0
 1243.15     .15       0 4945.36    .032       0 5071.68     .15       0
#Block Obstruct= 3 ,-1
 2870.87 3244.71   28.52 5716.72 5941.98   28.85 6166.54 6343.73   29.79
Bank Sta=4945.36,5071.68
XS Rating Curve= 0
Exp/Cntr=.3,.1

Type RM Length L Ch R = 1 ,65912.83,204.68,206,200.99
BEGIN DESCRIPTION:
xsec extended to basin boundaries (left and right)
END DESCRIPTION:
XS GIS Cut Line= 4
     3192850.754    13812738.349     3192882.995    13811655.274
     3192965.415     13808886.63      3193076.01    13807653.541
#Sta/Elev= 30
 1237.41   32.44    1333   31.74 1526.82   35.32 1719.19    31.6 2026.63   29.71
 2269.24   30.51 2332.78   29.01 2632.11   29.51 3537.46   25.72 3855.58   26.63
 4066.11   25.39 4150.26   28.11  4219.5   25.07 4450.39   26.94 4510.42   30.09
 4570.45   26.51 4630.47   28.76 4683.84   22.95 4716.83   26.88 4945.36    25.5
 4970.35   24.23 4998.79   15.88 5029.65   22.59 5062.73   26.27 5292.44   25.09
 5368.24   25.63 5417.97   28.13 5535.48   25.87 5741.02   29.74 6328.87   28.65
#Mann= 3 ,-1 , 0
 1237.41     .15       0 4945.36    .032       0 5062.73     .15       0
#Block Obstruct= 1 ,-1
 5742.05 6710.25   29.73
Bank Sta=4945.36,5062.73
XS Rating Curve= 0
Exp/Cntr=.3,.1

Type RM Length L Ch R = 1 ,65706.84,564,568.31,436.19
BEGIN DESCRIPTION:
xsec extended to basin boundaries (left and right)
END DESCRIPTION:
XS GIS Cut Line= 4
     3193050.541    13812748.476     3193082.907    13811661.225
      3193165.17     13808897.81     3193262.422    13807655.131
#Sta/Elev= 30
 1201.36   32.03 1398.61   31.17 1578.95    32.6  1650.7    32.3 1691.92   30.08
 2168.86   28.97 2255.24   30.23 2799.06   27.62 2891.59   28.98 3006.25   26.89
 3395.17   27.24 3435.38    25.3 3564.49   26.82 4037.54   24.94 4105.89    27.1
 4177.82   25.49 4330.78   27.38 4529.52    26.4  4578.3   29.28 4619.56   29.35
 4649.57   18.96 4664.58   25.53 4679.59   27.67 4980.35   24.23 5008.79   15.88
 5039.75    26.9 5290.24   29.39 5512.01   29.38 5534.37   27.83 6300.21   29.54
#Mann= 3 ,-1 , 0
 1201.36     .15       0 4980.35    .032       0 5039.75     .15       0
#XS Ineff= 3 ,-1
 2722.68 2892.58   28.95 2949.61 3164.66    28.1 5286.69 6535.84    29.4
Permanent Ineff=
       F       F       F
#Block Obstruct= 1 ,-1
    4600 4707.32   27.33
Bank Sta=4980.35,5039.75
XS Rating Curve= 0
Exp/Cntr=.3,.1

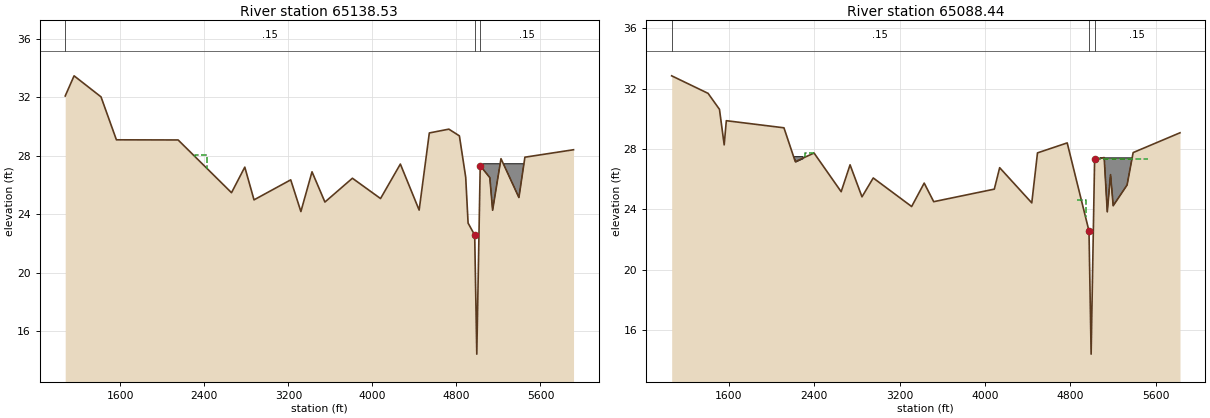
Type RM Length L Ch R = 1 ,65138.53,56.98,50.09,52.01
BEGIN DESCRIPTION:
xsec extended to basin boundaries (left and right)
END DESCRIPTION:
XS GIS Cut Line= 5
     3193552.437    13812773.917     3193642.682     13810748.97
     3193726.471    13808868.885      3193724.35    13808822.404
     3193553.816    13807953.775
#Sta/Elev= 30
 1074.24   32.09 1158.79   33.47  1415.2   32.03 1561.85   29.09 2149.56   29.08
 2657.94   25.47  2784.4   27.22 2872.31   24.98 3221.76   26.35  3318.6   24.18
 3424.61    26.9 3547.46   24.83 3809.13   26.46 4077.06   25.07 4265.85   27.43
 4444.71   24.28 4541.67   29.56 4727.69   29.82 4828.01   29.36 4888.09   26.53
 4910.84   23.39 4973.66   22.57 4993.66   14.42 5026.34   27.32 5117.69    26.5
 5144.32   24.27 5224.06    27.8 5394.76   25.14 5451.82    27.9 5914.89   28.41
#Mann= 3 ,-1 , 0
 1074.24     .15       0 4973.66    .032       0 5026.34     .15       0
#XS Ineff= 1 ,-1
 2314.97  2425.5   28.04
Permanent Ineff=
       F
#Block Obstruct= 1 ,-1
 5055.43 5482.28   27.45
Bank Sta=4973.66,5026.34
XS Rating Curve= 0
Exp/Cntr=.5,.3

Type RM Length L Ch R = 1 ,65088.44,196.84,164.21,149.08
BEGIN DESCRIPTION:
xsec extended to basin boundaries (left and right)
END DESCRIPTION:
XS GIS Cut Line= 5
      3193651.66    13812778.946     3193715.167     13810790.39
     3193776.529    13808869.017     3193774.128    13808816.391
     3193623.398    13808032.792
#Sta/Elev= 30
 1063.74   32.84 1404.88   31.68 1511.64   30.62 1555.79   28.27 1575.71   29.87
 2115.66    29.4 2221.84   27.16 2397.78   27.73 2651.71   25.17 2735.12   26.95
 2846.81   24.83 2952.31   26.08 3312.04   24.19 3429.69   25.74 3518.77   24.51
 4086.57   25.34 4136.75   26.76 4437.62   24.43 4491.11   27.74 4769.49    28.4
 4973.66   22.57 4993.66   14.42 5026.34   27.32 5115.93   27.43 5145.05   23.84
  5175.6    26.3 5200.31   24.24 5330.43   25.61 5387.31   27.76 5826.31   29.07
#Mann= 3 ,-1 , 0
 1063.74     .15       0 4973.66    .032       0 5026.34     .15       0
#XS Ineff= 3 ,-1
 2309.06 2397.12   27.74 4856.66 4941.98   24.64 5028.15 5527.14   27.34
Permanent Ineff=
       F       F       F
#Block Obstruct= 2 ,-1
  2160.2 2290.19   27.52 5080.07 5483.41   27.41
Bank Sta=4973.66,5026.34
XS Rating Curve= 0
Exp/Cntr=.5,.3