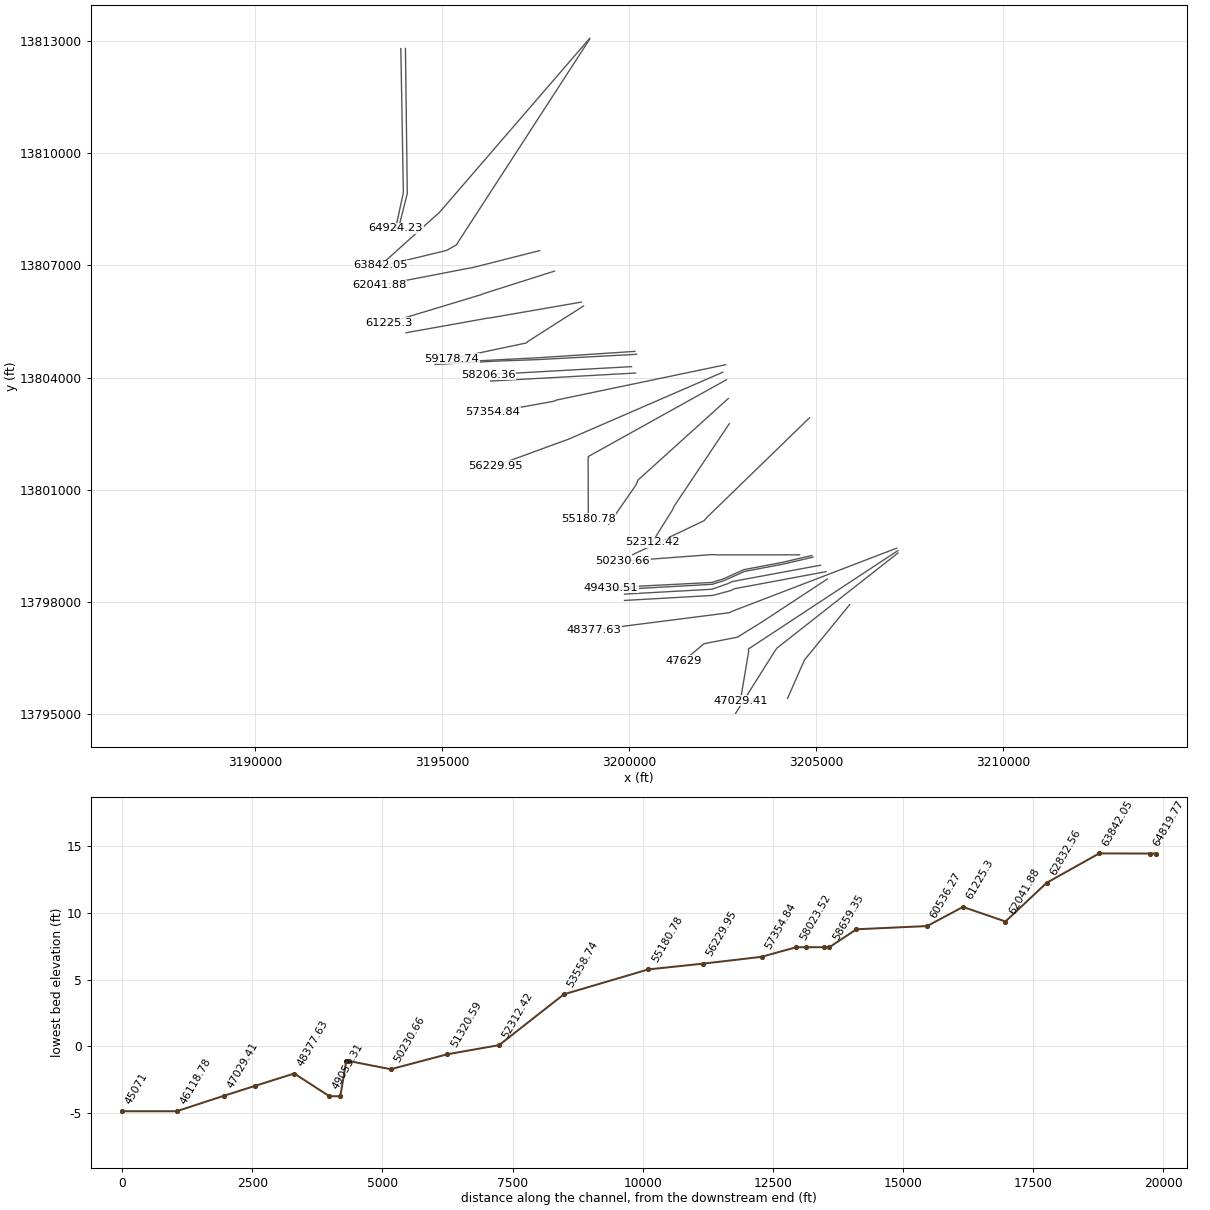
HEC-RAS study B100-00-00.prj: B100-00-00

--- B100-00-00.g01 (geometry) --- (continued)

Type RM Length L Ch R = 3 ,65006   ,,,
BEGIN DESCRIPTION:
Trebor
END DESCRIPTION:
Bridge Culvert--1,0,-1,-1, 0
Deck Dist Width WeirC Skew NumUp NumDn MinLoCord MaxHiCord MaxSubmerge Is_Ogee
58,50,2.6,0, 9, 9, , , .95, 0, 0,0,,
    3213    4394 4907.07    4941 4956.33 5021.49 5040.63 5069.47    5600
    24.4    26.2   25.55      26   25.62   26.26   26.94   27.39    27.5
                                   24.12   24.76
    3169    4350 4863.07    4897 4912.33 4977.49 4996.63 5025.47    5556
    24.4    26.2   25.55      26   25.62   26.26   26.94   27.39    27.5
                                   24.12   24.76
Pier Skew, UpSta & Num, DnSta & Num=  ,4976, 4 ,7036, 4 , 3 , 3 , 0 ,,
       2       2     2.2     2.2
       0    23.3    23.3    24.6
       2       2     2.2     2.2
       0    23.3    23.3    24.6
Pier Skew, UpSta & Num, DnSta & Num=  ,4995, 4 ,7055, 4 , 3 , 3 , 0 ,,
       2       2     2.2     2.2
       0   23.45   23.45    24.8
       2       2     2.2     2.2
       0   23.45   23.45    24.8
BR Coef=-1 , 1 , 0 ,, 0 ,,,.8,0,1.2,0,
WSPro=,,,, 1 ,,,, 0 ,,,, 0 ,,,,-1 ,-1 ,-1 , 0 , 0 , 0 , 0 , 0
BC Design=,, 0 ,, 0 ,,,,,,
BC HTab HWMax=33.06

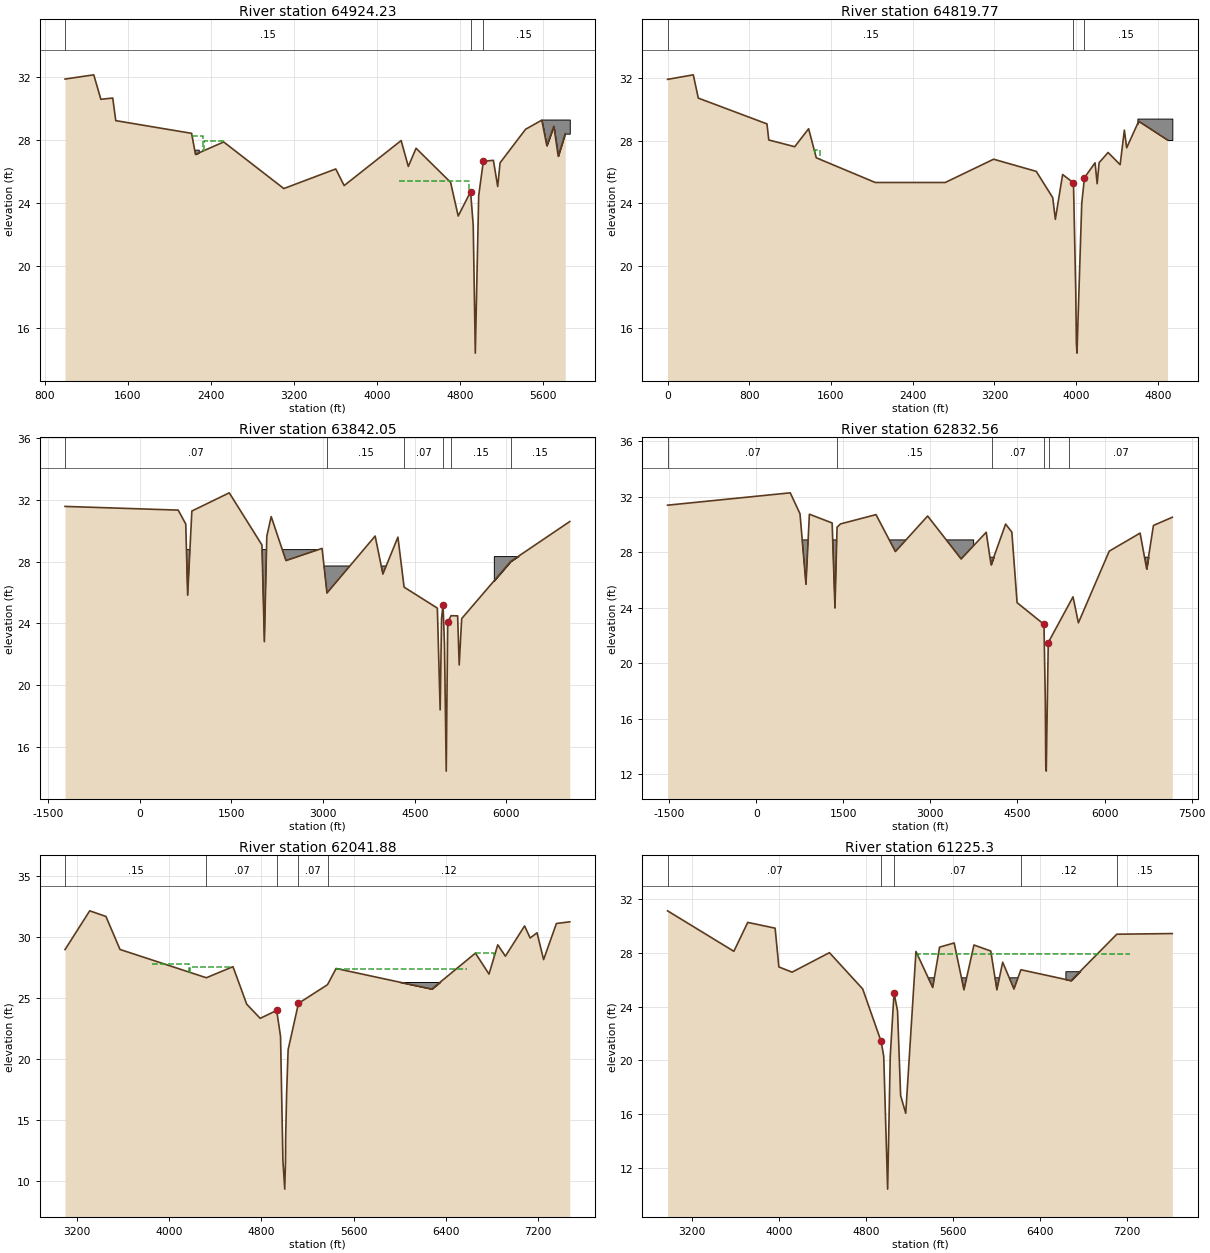
Type RM Length L Ch R = 1 ,64924.23,108.37,104.46,90.39
BEGIN DESCRIPTION:
xsec extended to basin boundaries (left and right)
END DESCRIPTION:
XS GIS Cut Line= 4
     3193896.778    13812791.371     3193922.269    13811328.855
     3193963.819     13808944.99     3193758.652    13807990.478
#Sta/Elev= 30
  993.34   31.89 1270.45   32.16 1339.05    30.6 1453.36   30.68 1482.73   29.24
 2213.91   28.43 2251.06   27.09 2523.44   27.88 3103.24   24.91 3604.08   26.16
  3684.9    25.1 4234.49   27.97 4303.43   26.32 4378.44   27.48 4711.07   25.31
 4784.76   23.16 4904.11   24.71 4929.66   22.57 4949.66   14.42 4982.34   24.46
  5027.1   26.65 5124.03   26.71 5165.77   25.04  5188.3   26.55 5434.29   28.69
 5590.81   29.27 5639.29   27.64 5706.84   28.88 5749.38   26.97 5816.62   28.41
#Mann= 3 , 0 , 0
  993.34     .15       0 4904.11    .032       0  5027.1     .15       0
#XS Ineff= 3 ,-1
  2213.6 2320.19   28.23 2335.91 2522.87   27.96    4216 4889.09    25.4
Permanent Ineff=
       F       F       F
#Block Obstruct= 2 ,-1
 2231.95 2282.62   27.39 5583.87 5860.66   29.31
Bank Sta=4904.11,5027.1
XS Rating Curve= 0
Exp/Cntr=.5,.3

Type RM Length L Ch R = 1 ,64819.77,1315.98,977.72,724.99
BEGIN DESCRIPTION:
xsec extended to basin boundaries (left and right)
END DESCRIPTION:
XS GIS Cut Line= 4
     3194019.254    13812797.579     3194036.175    13811473.827
     3194068.843    13808918.325     3193820.757    13807934.612
#Sta/Elev= 30
       0   31.94  251.97   32.23  300.82   30.74  973.25   29.09  990.87   28.06
 1244.81   27.63  1380.9   28.78 1455.91   26.92 2033.22   25.34 2718.29   25.34
 3191.89   26.83 3609.47   26.05 3770.42   24.37  3796.1   22.98 3867.27   25.85
 3973.57   25.32 3995.97   18.33 4002.06   15.03  4007.7   14.42  4054.5      24
  4081.1   25.65  4184.9    26.6 4205.54   25.26 4224.56   26.61 4312.56   27.26
 4430.31   26.48 4471.68   28.69  4494.3   27.56 4612.36   29.26 4894.08   28.06
#Mann= 3 , 0 , 0
       0     .15       0 3973.57    .032       0  4081.1     .15       0
#XS Ineff= 2 ,-1
  965.69  1348.6   28.46 1442.55  1491.5   27.44
Permanent Ineff=
       F       F
#Block Obstruct= 1 ,-1
 4599.53 4941.11   29.43
Bank Sta=3973.57,4081.1
XS Rating Curve= 0
Exp/Cntr=.3,.1

Type RM Length L Ch R = 1 ,63842.05,916.27,1009.49,775.02
XS GIS Cut Line= 5
     3198943.684    13813066.423     3195744.766    13809361.387
     3194900.587    13808383.645     3194839.787    13808337.005
     3193356.812    13807002.018
#Sta/Elev= 30
 -1222.9   31.58  628.58   31.34  752.53   30.44  783.45   25.83  852.32   31.28
 1464.24   32.46 1999.31   29.08 2038.94   22.82 2078.58   29.65 2150.48   30.92
 2392.17   28.07 2982.84   28.86 3063.25   25.97 3851.21   29.66 3977.73    27.2
 4223.99   29.59 4324.94   26.35 4869.05   24.99 4914.96    18.4 4937.91   24.32
 4961.69    25.2 4985.42   22.68 5014.48   14.43 5038.31   24.07 5092.62    24.5
 5201.01   24.49 5226.51   21.31 5266.86   24.31 6068.14   28.01 7035.77    30.6
#Mann= 6 ,-1 , 0
 -1222.9     .07       0 3063.25     .15       0 4324.94     .07       0
 4961.69    .032       0 5092.62     .15       0 6068.14     .15       0
#Block Obstruct= 3 ,-1
  423.21 2971.56   28.78 2891.92 4177.47   27.72 5792.95 7067.12   28.36
Bank Sta=4961.69,5038.31
XS Rating Curve= 0
Exp/Cntr=.3,.1

Type RM Length L Ch R = 1 ,62832.56,1164.95,790.68,715.49
XS GIS Cut Line= 5
     3198944.739    13813046.972     3195420.325     13807610.27
     3195388.561     13807551.24     3195118.918    13807398.044
     3193332.835    13806966.052
#Sta/Elev= 30
-1527.05   31.38  586.34   32.27   754.2   30.76   856.9   25.68  915.49   30.73
 1307.72    30.1 1356.33   23.98 1392.09   29.79 1450.95   30.03 2063.27    30.7
 2397.49   28.04  2952.7    30.6 3529.59   27.51 3961.39   29.43 4045.12   27.09
 4295.87   30.02 4403.02   29.44 4493.26   24.36 4956.48    22.8 4979.26   17.33
 4987.13    12.6 4995.59   12.23    5030   21.49 5456.63   24.78 5549.28   22.91
 6080.21   28.07 6612.14   29.37 6725.16   26.79 6841.64   29.92 7166.83   30.51
#Mann= 6 ,-1 , 0
-1527.05     .07       0 1398.89     .15       0 4057.89     .07       0
 4949.43    .032       0 5046.81     .07       0 5381.54     .07       0
#Block Obstruct= 3 ,-1
  343.57 3745.17   28.88 3881.68 4177.47   27.67 6168.37 6850.97   27.67
Bank Sta=4956.48,5030
XS Rating Curve= 0
Exp/Cntr=.3,.1

Type RM Length L Ch R = 1 ,62041.88,760.24,816.59,840.99
XS GIS Cut Line= 4
     3197608.684    13807393.918     3195794.684    13806934.515
     3195729.508    13806926.037     3193332.029    13806461.959
#Sta/Elev= 30
 3097.34   28.99  3311.5   32.17 3452.25   31.71 3574.45      29 4323.45   26.68
 4554.53   27.59 4673.68   24.51 4790.39   23.35 4933.61      24 4967.14   21.86
 4987.63   11.69  5003.4    9.34 5010.34   11.74 5011.29   13.51 5019.81   17.19
 5032.86   20.78 5122.56   24.58 5374.41   26.11 5449.22   27.44 6279.41   25.75
 6657.76    28.7 6775.59   26.98 6851.37   29.38 6917.83   28.45 7084.24   30.93
 7132.74   29.94  7192.4   30.37 7249.23   28.17 7360.28   31.13 7476.32   31.27
#Mann= 5 ,-1 , 0
 3097.34     .15       0 4323.45     .07       0 4933.61    .032       0
 5122.56     .07       0 5374.41     .12       0
#XS Ineff= 4 ,-1
 3855.41 4177.11   27.82 4185.76 4553.66   27.59 5445.96 6583.62   27.41
 6656.63 6821.52   28.69
Permanent Ineff=
       F       F       F       F
#Block Obstruct= 2 ,-1
 5679.18 6464.16   26.33 6657.24 7399.29   25.42
Bank Sta=4933.61,5122.56
XS Rating Curve= 0
Exp/Cntr=.3,.1

Type RM Length L Ch R = 1 ,61225.3 ,799.46,689.03,621.37
XS GIS Cut Line= 4
     3198002.178    13806845.098     3196088.278    13806237.675
     3196054.625    13806219.513     3193570.196     13805467.87
#Sta/Elev= 30
 2976.15   31.12  3585.8   28.11 3713.48   30.26  3965.3   29.83 3999.64   26.95
 4121.08   26.56 4464.78   28.01 4770.81   25.31 4940.07   21.41 4963.95   20.32
 5000.08   10.43 5023.93   20.29  5058.9   25.03 5091.11   23.68 5119.51   17.38
 5166.53   16.07 5260.55    28.1 5414.59   25.42 5477.73   28.42 5612.01   28.73
 5701.85   25.25 5793.93   28.58 5948.58   28.13 6004.68   25.25 6058.08    27.3
 6161.91   25.31 6225.45   26.74 6686.66   25.93 7107.41   29.38 7618.01   29.43
#Mann= 5 ,-1 , 0
 2976.15     .07       0 4940.07    .032       0  5058.9     .07       0
 6225.45     .12       0 7107.41     .15       0
#XS Ineff= 2 ,-1
 3931.74 4464.16   27.99 5283.28 7228.67   27.94
Permanent Ineff=
       F       F
#Block Obstruct= 2 ,-1
 5324.23 6402.73   26.14 6634.81 6853.24   26.63
Bank Sta=4940.07,5058.9
XS Rating Curve= 0
Exp/Cntr=.3,.1

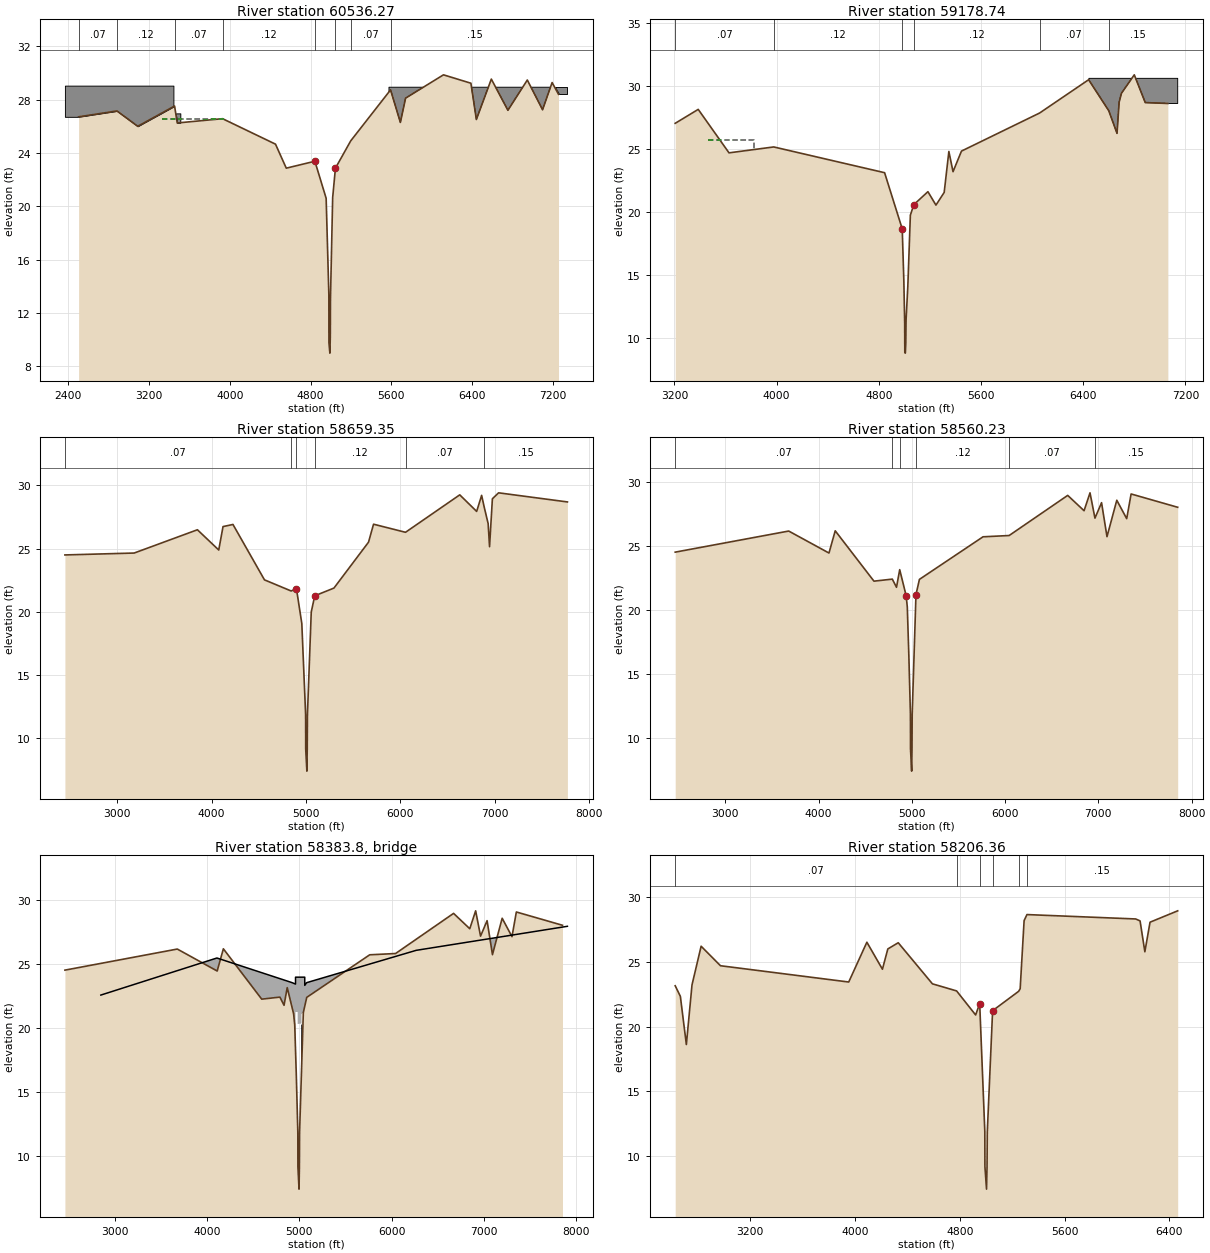
Type RM Length L Ch R = 1 ,60536.27,990.32,1357.53,999.96
XS GIS Cut Line= 4
      3198716.68     13806016.69     3196301.604    13805598.359
     3196210.234    13805587.951     3194036.175    13805198.637
#Sta/Elev= 30
 2503.01   26.72 2883.14   27.16 3088.61   26.01 3453.34   27.53 3479.45   26.26
  3928.5   26.58 4452.67   24.67  4559.2   22.87 4842.37   23.39 4954.02   20.61
 4980.88   13.37 4981.59    9.79  4990.9       9 4995.19   10.21 4996.59      13
 5018.56   20.67 5045.98   22.87 5197.51   24.92 5591.58   28.74 5688.94    26.3
 5740.47   28.12 6115.56   29.87 6387.22   29.24 6441.45   26.52  6589.5   29.55
 6753.58   27.21  6945.7   29.48 7096.71   27.25 7191.27   29.29 7254.65   28.41
#Mann= 8 ,-1 , 0
 2503.01     .07       0 2883.14     .12       0 3453.34     .07       0
  3928.5     .12       0 4842.37    .032       0 5045.98     .12       0
 5197.51     .07       0 5591.58     .15       0
#XS Ineff= 1 ,-1
 3324.23 3938.57   26.57
Permanent Ineff=
       F
#Block Obstruct= 3 ,-1
 2367.49  3441.7   29.06 3458.49 3510.13   26.98 5575.97 7342.76   28.94
Bank Sta=4842.37,5045.98
XS Rating Curve= 0
Exp/Cntr=.3,.1

Type RM Length L Ch R = 1 ,59178.74,838.82,519.39,368.19
XS GIS Cut Line= 4
      3198778.81    13805913.139     3197288.322    13804963.809
      3197249.11    13804925.332     3195258.077    13804504.846
#Sta/Elev= 30
 3206.48   27.05 3386.63   28.16 3627.83    24.7 3977.89   25.17 4845.63   23.12
 4983.71   18.65 4996.32   14.53 5002.88   11.19 5003.89     8.8 5008.07    8.76
 5011.68    9.52 5013.79   11.41 5027.47   14.07 5047.37   19.74 5074.72   20.58
 5184.76   21.61 5247.71   20.54 5312.12   21.55 5348.81   24.81 5381.45    23.2
 5447.49   24.84 6059.17   27.87 6442.92   30.52 6600.66   28.05 6665.18   26.25
  6681.7   28.73 6699.76   29.44  6800.3   30.91 6886.15    28.7 7063.51   28.63
#Mann= 6 ,-1 , 0
 3206.48     .07       0 3977.89     .12       0 4983.71    .032       0
 5074.72     .12       0 6059.17     .07       0 6600.66     .15       0
#XS Ineff= 1 ,-1
 3466.44  3824.8    25.7
Permanent Ineff=
       F
#Block Obstruct= 1 ,-1
 6445.23 7140.17   30.63
Bank Sta=4983.71,5074.72
XS Rating Curve= 0
Exp/Cntr=.3,.1

Type RM Length L Ch R = 1 ,58659.35,56.87,99.12,55.46
XS GIS Cut Line= 6
 3200153.579300313804700.6204854 3199030.030102813804626.3695532
     3198841.631    13804613.919     3197705.476    13804538.835
     3197612.761    13804533.049     3194837.668    13804389.611
#Sta/Elev= 30
    2446   24.51    3180   24.66 3850.13    26.5 4076.18    24.9 4121.58   26.75
 4226.88   26.92 4560.81   22.54  4843.6   21.66 4899.44   21.85  4956.5   19.09
 4996.99   11.88 4997.85    9.16 5010.11    7.42 5013.86    9.11 5015.89   11.84
 5056.51      20 5093.64   21.28 5296.97   21.89 5663.54   25.52 5716.64   26.94
 6055.56    26.3 6630.28   29.26 6809.43   27.95 6862.13   29.22 6888.86   28.31
 6931.04   26.99 6946.06   25.16  6976.1   28.95 7041.81   29.42 7771.14    28.7
#Mann= 6 ,-1 , 0
    2446     .07       0  4843.6     .12       0 4899.44    .032       0
 5093.64     .12       0 6055.56     .07       0 6888.86     .15       0
#Block Obstruct= 2 , 0
         4207.83   26.83 6657.22           29.21
Bank Sta=4899.44,5093.64
XS Rating Curve= 0
Exp/Cntr=.5,.3

Type RM Length L Ch R = 1 ,58560.23,328.1,353.88,699.7
XS GIS Cut Line= 6
 3200195.314082213804622.3436996     3198841.631    13804549.718
     3197708.276    13804488.913     3197615.434    13804483.119
     3196424.945     13804439.33     3194814.653    13804351.254
#Sta/Elev= 30
    2463   24.55    3680    26.2 4111.82   24.48 4178.68   26.22 4593.99   22.28
 4790.86   22.44  4835.7    21.8 4870.13   23.18 4939.18   21.14 4951.49   20.26
 4968.29   16.41 4984.99   11.88 4985.85    9.16 4998.11    7.42 5001.86    9.11
 5003.89   11.84 5044.51   21.23 5081.64   22.42 5763.41   25.75 6043.45   25.85
 6671.36   28.99 6846.74   27.79  6910.4   29.19 6963.59   27.21 7034.32   28.42
 7092.51   25.76 7197.66   28.61 7303.83   27.17 7351.15    29.1 7850.63   28.06
#Mann= 6 ,-1 , 0
    2463     .07       0 4790.86     .12       0 4870.13    .032       0
 5044.51     .12       0 6043.45     .07       0 6963.59     .15       0
#XS Ineff= 2 , 0
       0 4939.18   21.14 5044.51       0   21.23
Permanent Ineff=
       F       F
#Block Obstruct= 2 , 0
         4180.84   26.14 6690.96           28.96
Bank Sta=4939.18,5044.51
XS Rating Curve= 0
Exp/Cntr=.5,.3

Type RM Length L Ch R = 3 ,58383.8 ,,,
BEGIN DESCRIPTION:
Fairmont Parkway
END DESCRIPTION:
Bridge Culvert--1,0,-1,-1, 0
Deck Dist Width WeirC Skew NumUp NumDn MinLoCord MaxHiCord MaxSubmerge Is_Ogee
96,148,2.6,0, 14, 14, , , .95, 0, 0,0,,
    2852    4109    4920    4960 4960.01 4982.99    4983    5025 5025.01    5060
 5060.01    5080    6267    7904
    22.6    25.5   23.58   23.46      24      24      24      24      24      24
   23.36   23.57    26.1   27.98
                                   21.28   21.28   20.34   20.37   21.11   21.11
                                
    2852    4109    4920    4960 4960.01 4982.99    4983    5025 5025.01    5060
 5060.01    5080    6267    7904
    22.6    25.5   23.58   23.46      24      24      24      24      24      24
   23.36   23.57    26.1   27.98
                                   21.28   21.28   20.34   20.37   21.11   21.11
                                
Pier Skew, UpSta & Num, DnSta & Num=  ,4985, 2 ,4985, 2 , 0 , 0 , 0 ,,
       2       2
           20.34
       2       2
           20.34
Pier Skew, UpSta & Num, DnSta & Num=  ,5023, 2 ,5023, 2 , 0 , 0 , 0 ,,
       2       2
       0   20.34
       2       2
       0   20.34
BR Coef=-1 , 1 , 0 ,, 0 ,,,.8,0,1.2,0,
WSPro=,,,, 1 ,,,, 0 ,,,, 0 ,,,,-1 ,-1 ,-1 , 0 , 0 , 0 , 0 , 0
BC Design=,, 0 ,, 0 ,,,,,,
BC HTab HWMax=29.19

Type RM Length L Ch R = 1 ,58206.36,185.2,182.84,176.64
XS GIS Cut Line= 2
     3200061.462    13804292.911     3196230.766    13804078.906
#Sta/Elev= 30
 2627.03   23.16 2666.49   22.34 2712.22   18.61 2755.34   23.23 2824.99   26.22
 2972.87   24.71 3951.98   23.45  4090.5   26.53 4209.31   24.44 4250.48   26.01
 4329.95   26.49 4590.92   23.31 4775.56   22.76 4920.87    20.9 4951.91   21.78
 4990.99   11.88 4991.85    9.16 5004.11    7.42 5007.86    9.11 5009.89   11.84
 5050.51   21.23 5249.31   22.73 5260.95   22.93 5290.99    28.2  5312.7   28.67
 6143.13   28.33 6176.44   28.18 6212.98   25.79 6252.49   28.08  6463.7   28.96
#Mann= 6 ,-1 , 0
 2627.03     .07       0 4775.56     .12       0 4951.91    .042       0
 5050.51     .12       0 5249.31     .07       0  5312.7     .15       0
#XS Ineff= 2 , 0
       0 4951.91   21.78 5050.51       0   21.23
Permanent Ineff=
       F       F
#Block Obstruct= 2 , 0
         4307.69   26.44 6014.84           28.51
Bank Sta=4951.91,5050.51
XS Rating Curve= 0
Exp/Cntr=.5,.3

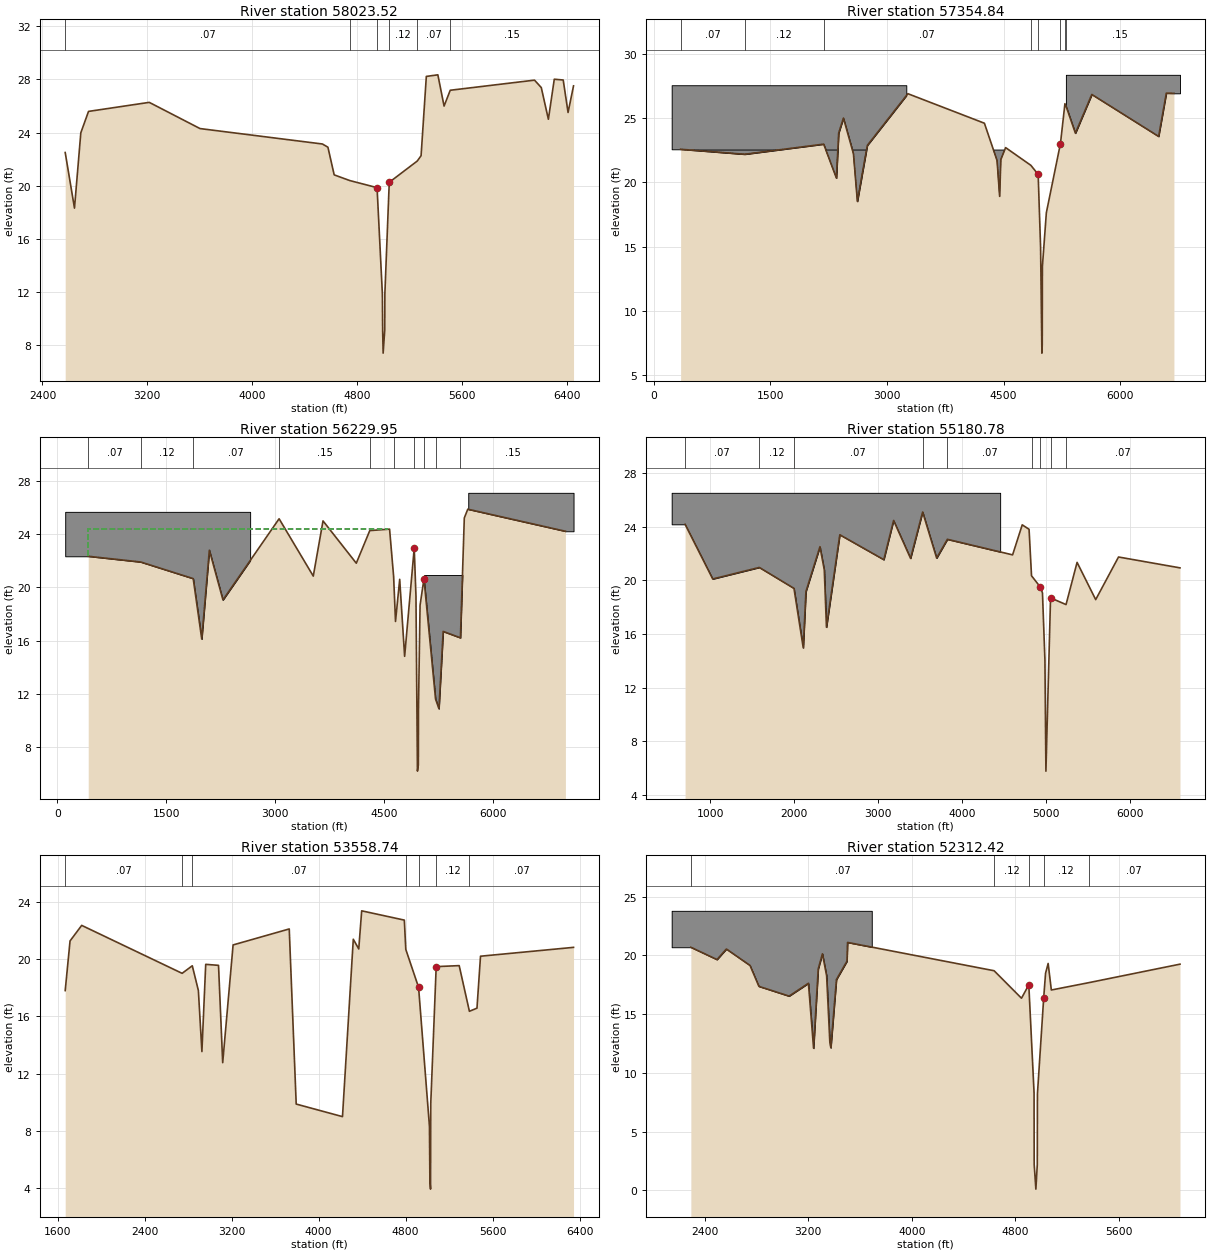
Type RM Length L Ch R = 1 ,58023.52,587.34,668.68,742.37
XS GIS Cut Line= 2
     3200168.464    13804121.707     3196294.967    13803907.702
#Sta/Elev= 30
 2573.44    22.5 2644.29   18.32 2692.58   23.98 2751.37   25.59 3214.81   26.27
 3602.26    24.3 4536.42   23.14 4578.31    22.9 4626.24   20.82 4745.91   20.39
 4953.49   19.86 4994.11   11.84 4996.14    9.11 4999.89    7.42 5012.15    9.16
 5013.01   11.88 5046.51   20.26  5260.2   21.86 5289.41   22.26 5329.46   28.22
 5417.41   28.34 5464.87   25.99 5511.91   27.18 6155.08   27.94 6206.82   27.38
 6260.87      25 6305.94   28.01  6374.1   27.95  6411.1   25.51 6452.84   27.51
#Mann= 6 ,-1 , 0
 2573.44     .07       0 4745.91     .12       0 4953.49    .042       0
 5046.51     .12       0  5260.2     .07       0 5511.91     .15       0
#Block Obstruct= 2 , 0
         3221.32   26.19 5373.82           28.17
Bank Sta=4953.49,5046.51
XS Rating Curve= 0
Exp/Cntr=.3,.1

Type RM Length L Ch R = 1 ,57354.84,1024.83,1124.89,1201.27
XS GIS Cut Line= 4
      3202573.58    13804343.678     3198056.906    13803399.815
     3197979.721    13803366.774     3196359.169    13803073.081
#Sta/Elev= 30
  345.84   22.58 1170.71   22.19 2185.93   22.98 2349.93   20.34  2378.9   23.84
 2440.11   25.01 2569.03   22.23 2619.73   18.52 2747.32   22.88 3268.99   26.91
 4253.35   24.61 4415.97   21.71 4449.55   18.91 4464.87   21.78 4526.17   22.71
  4850.9   21.33  4944.8   20.62 4975.93   14.96 4992.88     6.7  4997.4    7.36
 4999.16   13.44 5050.23   17.64 5231.61   23.03 5289.08   26.13 5308.53   25.85
 5423.98   23.83 5635.04   26.85 6494.47   23.58 6593.34   26.95 6690.99   26.94
#Mann= 8 ,-1 , 0
  345.84     .07       0 1170.71     .12       0 2185.93     .07       0
  4850.9     .12       0  4944.8    .042       0 5231.61     .12       0
 5289.08     .07       0 5308.53     .15       0
#Block Obstruct= 3 ,-1
  230.86 3248.53   27.57  345.84 4543.86   22.52 5301.53 6769.14   28.38
Bank Sta=4944.8,5231.61
XS Rating Curve= 0
Exp/Cntr=.3,.1

Type RM Length L Ch R = 1 ,56229.95,773.22,1049.17,1694.84
XS GIS Cut Line= 4
     3202501.123    13804143.108     3198357.336    13802344.867
     3198253.116    13802309.207     3196423.371    13801639.245
#Sta/Elev= 30
   426.5   22.34 1149.85   21.91  1873.2   20.66 1990.95   16.12 2095.77    22.8
 2283.14   19.06 3056.85   25.16 3527.81   20.85 3662.07      25 4120.63   21.82
 4306.26   24.27 4579.23   24.38 4635.05   20.82 4660.99   17.44 4718.69   20.61
 4786.66   14.82 4918.91   22.95 4942.92   19.34  4963.2    6.19 4975.85    6.65
 4977.35   10.88 4999.43   18.66 5053.08   20.65 5212.74   11.61 5259.51   10.88
 5317.98   16.69 5555.67   16.21 5609.14   25.22 5657.05   25.88 7002.35   24.22
#Mann= 10 ,-1 , 0
   426.5     .07       0 1149.85     .12       0  1873.2     .07       0
 3056.85     .15       0 4306.26     .07       0 4635.05     .12       0
 4918.91    .042       0 5053.08     .12       0 5212.74     .07       0
 5555.67     .15       0
#XS Ineff= 1 ,-1
  236.63 4559.73   24.41
Permanent Ineff=
       F
#Block Obstruct= 3 ,-1
  109.22 2657.57   25.68  5054.5 7002.35   20.93 5663.13 7114.25   27.11
Bank Sta=4918.91,5053.08
XS Rating Curve= 0
Exp/Cntr=.3,.1

Type RM Length L Ch R = 1 ,55180.78,1386.9,1622.04,1119.96
BEGIN DESCRIPTION:
Basin Boundary on Right
END DESCRIPTION:
XS GIS Cut Line= 4
     3202598.606    13803943.264     3198905.709    13801890.291
     3198902.433    13801777.503     3198905.833     13800226.81
#Sta/Elev= 30
  701.24   24.18 1030.12    20.1 1584.55   20.96 1996.76    19.4 2107.37   14.96
 2139.25   19.16 2306.06   22.51 2357.38   20.78 2383.48    16.5 2542.24    23.4
 3065.78   21.54 3181.96   24.47 3383.96   21.64 3527.82    25.1  3694.5   21.66
 3822.26   23.06 4598.21    21.9 4712.76   24.14 4794.05   23.81 4823.34   20.34
 4927.58    19.5 4953.58   19.06 4982.97   14.03 4994.57    5.76 5049.71   18.69
 5234.02   18.19 5365.48   21.34 5586.97   18.56 5858.54   21.74 6589.96   20.93
#Mann= 9 ,-1 , 0
  701.24     .07       0 1584.55     .12       0 1996.76     .07       0
 3527.82     .15       0 3822.26     .07       0 4823.34     .12       0
 4927.58    .042       0 5049.71     .12       0 5234.02     .07       0
#Block Obstruct= 1 ,-1
  541.67    4450   26.53
Bank Sta=4927.58,5049.71
XS Rating Curve= 0
Exp/Cntr=.3,.1

Type RM Length L Ch R = 1 ,53558.74,1146.91,1246.32,1252.95
BEGIN DESCRIPTION:
Basin Boundary on Right
END DESCRIPTION:
XS GIS Cut Line= 4
     3202648.658    13803442.746     3200237.697    13801264.231
     3200170.823    13801116.678      3199451.51    13800079.616
#Sta/Elev= 30
 1670.12   17.81 1714.62   21.29 1821.74   22.38 2745.03   19.02  2838.5   19.55
 2894.42   17.82 2926.91   13.54 2961.96   19.65 3079.71   19.58 3118.07   12.76
 3213.66   21.01 3729.83   22.13 3793.89    9.86 4219.44    8.98 4318.77   21.41
 4369.02   20.73 4395.92    23.4 4788.01   22.75 4801.37    20.7    4919   18.04
    5019     8.3    5023     4.5    5029     3.9    5031     9.9    5081   19.49
 5292.41   19.56 5386.29   16.36 5455.89   16.58 5488.45   20.22 6343.63   20.84
#Mann= 7 ,-1 , 0
 1670.12     .07       0 2745.03     .12       0  2838.5     .07       0
 4801.37     .12       0    4919    .042       0    5081     .12       0
 5386.29     .07       0
#Block Obstruct= 2 , 0
         4465.59   23.56
Bank Sta=4919,5081
XS Rating Curve= 0
Exp/Cntr=.3,.1

Type RM Length L Ch R = 1 ,52312.42,1053.93,991.83,506.06
BEGIN DESCRIPTION:
Basin Boundary on Right
END DESCRIPTION:
XS GIS Cut Line= 4
     3202673.684    13802767.048     3201197.694    13800558.725
     3201157.904    13800466.982     3200616.143    13799602.308
#Sta/Elev= 30
 2294.11   20.69 2496.33   19.64 2568.59   20.54 2751.08   19.14 2819.72   17.36
 3052.75   16.53 3202.08   17.62 3241.93   12.09 3277.78   18.84 3310.22   20.13
 3342.66   18.25 3367.52   12.59  3375.1   12.13 3418.36   17.94 3499.58    19.5
 3504.06    21.1 4635.57   18.69 4846.96   16.35 4903.48   17.49    4944     8.3
    4945     2.2    4958      .1    4969     2.2    4970     8.2  5018.6   16.41
 5032.76   18.47 5052.77   19.31 5077.42   17.05 5364.53   17.67 6070.66   19.25
#Mann= 5 ,-1 , 0
 2294.11     .07       0 4635.57     .12       0 4903.48    .042       0
  5018.6     .12       0 5364.53     .07       0
#Block Obstruct= 1 ,-1
 2146.34 3691.06   23.79
Bank Sta=4903.48,5018.6
XS Rating Curve= 0
Exp/Cntr=.3,.1

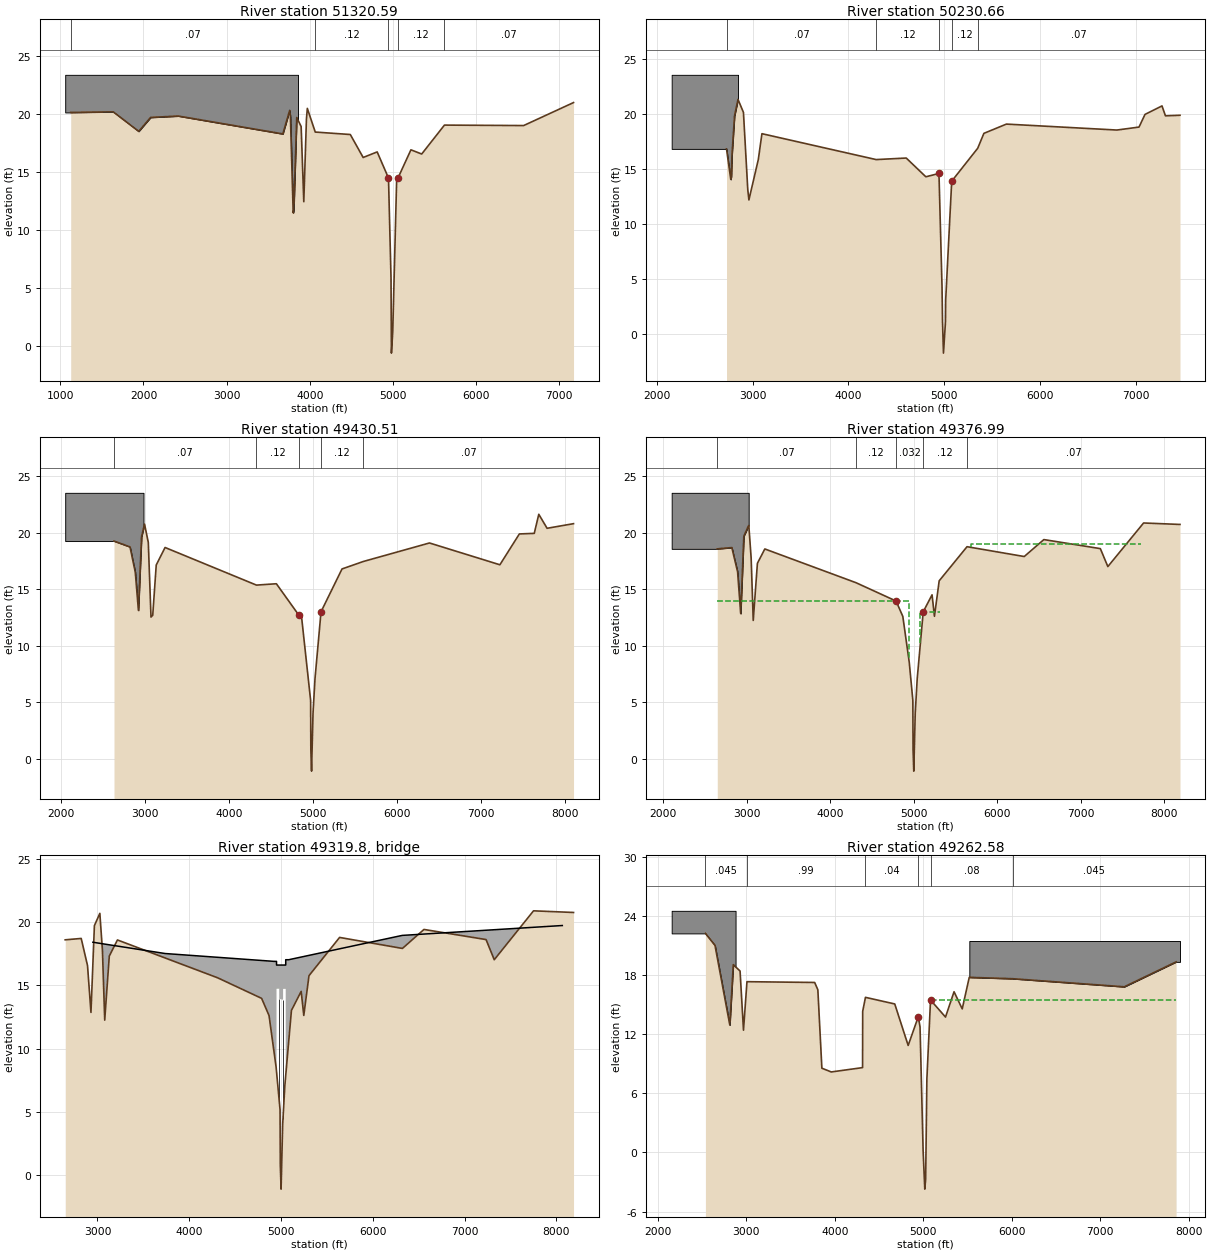
Type RM Length L Ch R = 1 ,51320.59,1451.86,1089.93,922.21
XS GIS Cut Line= 5
     3204816.456    13802924.374      3202076.27    13800263.887
     3202001.311    13800176.388     3200635.235    13799525.939
 3200093.508932813799267.9993402
#Sta/Elev= 30
  1124.1   20.15 1636.67    20.2 1942.83   18.52 2085.54   19.72 2418.37   19.84
 3676.08    18.3 3758.02   20.33 3766.64   19.81 3800.45   11.51 3807.54   11.75
 3842.88   19.71 3895.92   18.94 3927.75   12.46 3959.57   19.57 3970.18    20.5
 4065.76   18.46 4487.11   18.25 4641.72   16.27 4810.26   16.75 4946.39    14.5
 4976.75    5.89  4981.5    -.58  4997.3    1.24 5045.21   14.55 5061.61   14.52
 5216.09   16.93 5345.83   16.57 5619.16   19.06 6571.61   19.02 7171.61      21
#Mann= 5 ,-1 , 0
  1124.1     .07       0 4065.76     .12       0 4946.39    .042       0
 5061.61     .12       0 5619.16     .07       0
#Block Obstruct= 1 ,-1
 1058.54 3858.54   23.39
Bank Sta=4946.39,5061.61
XS Rating Curve= 0
Exp/Cntr=.3,.1

Type RM Length L Ch R = 1 ,50230.66,529.97,800.15,778.98
XS GIS Cut Line= 4
     3204551.606    13799263.362     3202344.464    13799262.711
     3202211.695    13799270.591     3199826.056    13799092.581
#Sta/Elev= 30
 2728.44   16.83 2772.99   14.06 2778.89   14.31 2784.79   16.16 2812.07   19.81
 2848.41   21.32 2905.21   20.14 2950.18   13.15 2962.03    12.2 3060.38   15.87
 3098.02   18.21 4290.14   15.86 4603.98      16 4808.46    14.3  4945.5    14.6
  4977.5     4.3  4982.5     1.2  4992.5    -1.7  5013.5    1.15  5015.5     3.1
  5078.5    13.9 5350.06   16.89 5414.49   18.24 5649.38   19.08 6802.59   18.54
 7033.21   18.81 7095.81   19.96 7273.08   20.73    7309   19.83 7460.86   19.88
#Mann= 5 ,-1 , 0
 2728.44     .07       0 4290.14     .12       0  4945.5    .042       0
  5078.5     .12       0 5350.06     .07       0
#XS Ineff= 1 ,-1
 5646.13 7088.07   19.02
Permanent Ineff=
       F
#Block Obstruct= 1 ,-1
  2156.1 2848.78   23.55
Bank Sta=4945.5,5078.5
XS Rating Curve= 0
Exp/Cntr=.3,.1

Type RM Length L Ch R = 1 ,49430.51,52.72,53.53,60.06
XS GIS Cut Line= 6
     3204880.541    13799245.406     3204080.645    13799059.384
      3203063.91    13798867.547     3202518.729    13798622.968
     3202210.904     13798525.46     3199511.291    13798387.422
#Sta/Elev= 30
 2627.38   19.28 2818.24   18.76 2881.13   16.52 2918.62   13.14  2956.1   19.66
 2991.42   20.78 3036.33   19.16 3068.55   12.55  3089.2   12.71 3131.03   17.16
 3236.33   18.71 4326.02   15.38 4563.56    15.5 4829.43   12.74 4862.35   12.67
 4971.87    5.18 4974.47     .83 4983.01   -1.09  5000.4    4.03 5024.28    7.11
 5096.03   13.02 5346.28   16.81 5599.92   17.47 6389.04   19.11 7228.75   17.18
 7460.99   19.91 7638.47   19.96  7692.6   21.65 7791.57   20.41 8106.87   20.82
#Mann= 5 ,-1 , 0
 2627.38     .07       0 4326.02     .12       0 4829.43    .032       0
 5096.03     .12       0 5599.92     .07       0
#XS Ineff= 1 ,-1
 6404.88 7508.94   19.03
Permanent Ineff=
       F
#Block Obstruct= 1 ,-1
 2045.53 2978.86   23.55
Bank Sta=4829.43,5096.03
XS Rating Curve= 0
Exp/Cntr=.5,.3

Type RM Length L Ch R = 1 ,49376.99,231.55,114.4,174.44
XS GIS Cut Line= 6
     3204911.918    13799201.369     3204090.947    13799010.446
     3203079.054    13798819.522     3202536.462    13798576.136
     3202219.899     13798475.86     3199483.647    13798322.162
#Sta/Elev= 30
  2648.3   18.59 2822.66    18.7 2891.51   16.56 2928.99   12.86 2966.48   19.71
 3025.78   20.68 3053.94   17.78 3078.93   12.25 3128.91   17.31 3217.66   18.58
 4310.28   15.59 4788.81   13.97 4869.78   12.61 4946.81    8.54 4989.87    5.18
 4992.47     .83 5001.01   -1.09  5018.4    4.03 5042.28    7.11 5114.03   13.02
 5219.81   14.52  5248.5   12.62 5305.22   15.76 5638.61   18.78  6323.4   17.91
 6558.16   19.41 7234.71   18.61 7324.37   17.02 7752.33   20.88 8188.24   20.75
#Mann= 5 ,-1 , 0
  2648.3     .07       0 4310.28     .12       0 4788.81    .032       0
 5114.03     .12       0 5638.61     .07       0
#XS Ineff= 3 ,-1
  2648.3 4942.95   13.97 5079.93 5312.82      13 5687.05  7716.1   18.98
Permanent Ineff=
       F       F       F
#Block Obstruct= 1 ,-1
 2102.44 3024.39   23.55
Bank Sta=4788.81,5114.03
XS Rating Curve= 0
Exp/Cntr=.5,.3

Type RM Length L Ch R = 3 ,49319.8 ,,,
BEGIN DESCRIPTION:
Red Bluff
END DESCRIPTION:
Bridge Culvert--1,0,-1,-1, 0
Deck Dist Width WeirC Skew NumUp NumDn MinLoCord MaxHiCord MaxSubmerge Is_Ogee
41,35,2.6,0, 14, 14, , , .95, 0, 0,0,,
    2950    3737 4925.16  4951.3 4951.31 4980.49  4980.5  5022.8 5022.81 5051.52
 5051.52  5083.6    6321    8066
    18.4   17.51   16.89   16.89    16.6    16.6    16.6    16.6    16.6    16.6
   17.02   17.02   18.94   19.72
                                   14.73   14.73   13.93   13.86   14.72   14.72
                                
    2950    3737 4925.16  4951.3 4951.31 4980.49  4980.5  5022.8 5022.81 5051.52
 5051.52  5083.6    6321    8066
    18.4   17.51   16.89   16.89    16.6    16.6    16.6    16.6    16.6    16.6
   17.02   17.02   18.94   19.72
                                   14.73   14.73   13.93   13.86   14.72   14.72
                                
Pier Skew, UpSta & Num, DnSta & Num=  ,4981.566, 4 ,4981.566, 4 , 3 , 3 , 0 ,,
       2       2     2.2     2.2
       0   11.94   11.94   13.94
       2       2     2.2     2.2
       0   11.94   11.94   13.94
Pier Skew, UpSta & Num, DnSta & Num=  ,5021.731, 4 ,5021.731, 4 , 3 , 3 , 0 ,,
       2       2     2.2     2.2
       0   11.86   11.86   13.86
       2       2     2.2     2.2
       0   11.86   11.86   13.86
BR Coef=-1 , 1 , 0 ,, 0 ,,,.8,0,1.2,0,
WSPro=,,,, 1 ,,,, 0 ,,,, 0 ,,,,-1 ,-1 ,-1 , 0 , 0 , 0 , 0 , 0
BC Design=,, 0 ,, 0 ,,,,,,
BC HTab HWMax=21.18

Type RM Length L Ch R = 1 ,49262.58,210.18,209.27,235.99
BEGIN DESCRIPTION:
Modified with survey data (DEC - 06/2009)
END DESCRIPTION:
XS GIS Cut Line= 5
     3205111.988    13798985.578     3202756.607     13798550.73
     3202631.633    13798491.966     3202207.494    13798343.152
     3199874.809    13798213.559
#Sta/Elev= 30
 2537.28   22.23 2645.66   21.01 2813.05   12.93 2852.45   19.06 2928.94   18.41
 2967.57   12.41 3006.77   17.33 3771.99   17.25 3807.84   16.51 3853.34    8.55
 3959.49    8.17 4313.09    8.61 4314.52   14.32 4345.76   15.74 4676.65   15.07
 4828.42   10.86 4942.95   13.78 4962.55   12.72 4997.18     .19 5016.18   -3.72
 5025.98   -2.72 5039.73    7.45 5081.05   15.47 5250.28   13.74 5346.61   16.31
 5439.21   14.57 5518.58   17.77 6007.95   17.63 7270.15   16.81 7856.33   19.34
#Mann= 6 ,-1 , 0
 2537.28    .045       0 3006.77     .99       0 4345.76     .04       0
 4942.95    .032       0 5081.05     .08       0 6007.95    .045       0
#XS Ineff= 2 , 0
       0 4942.95   13.78 5081.05       0   15.47
Permanent Ineff=
       F       F
#Block Obstruct= 2 ,-1
  2156.1 2878.05   24.52 5519.33 7899.82   21.46
Bank Sta=4942.95,5081.05
XS Rating Curve= 0
Exp/Cntr=.5,.3

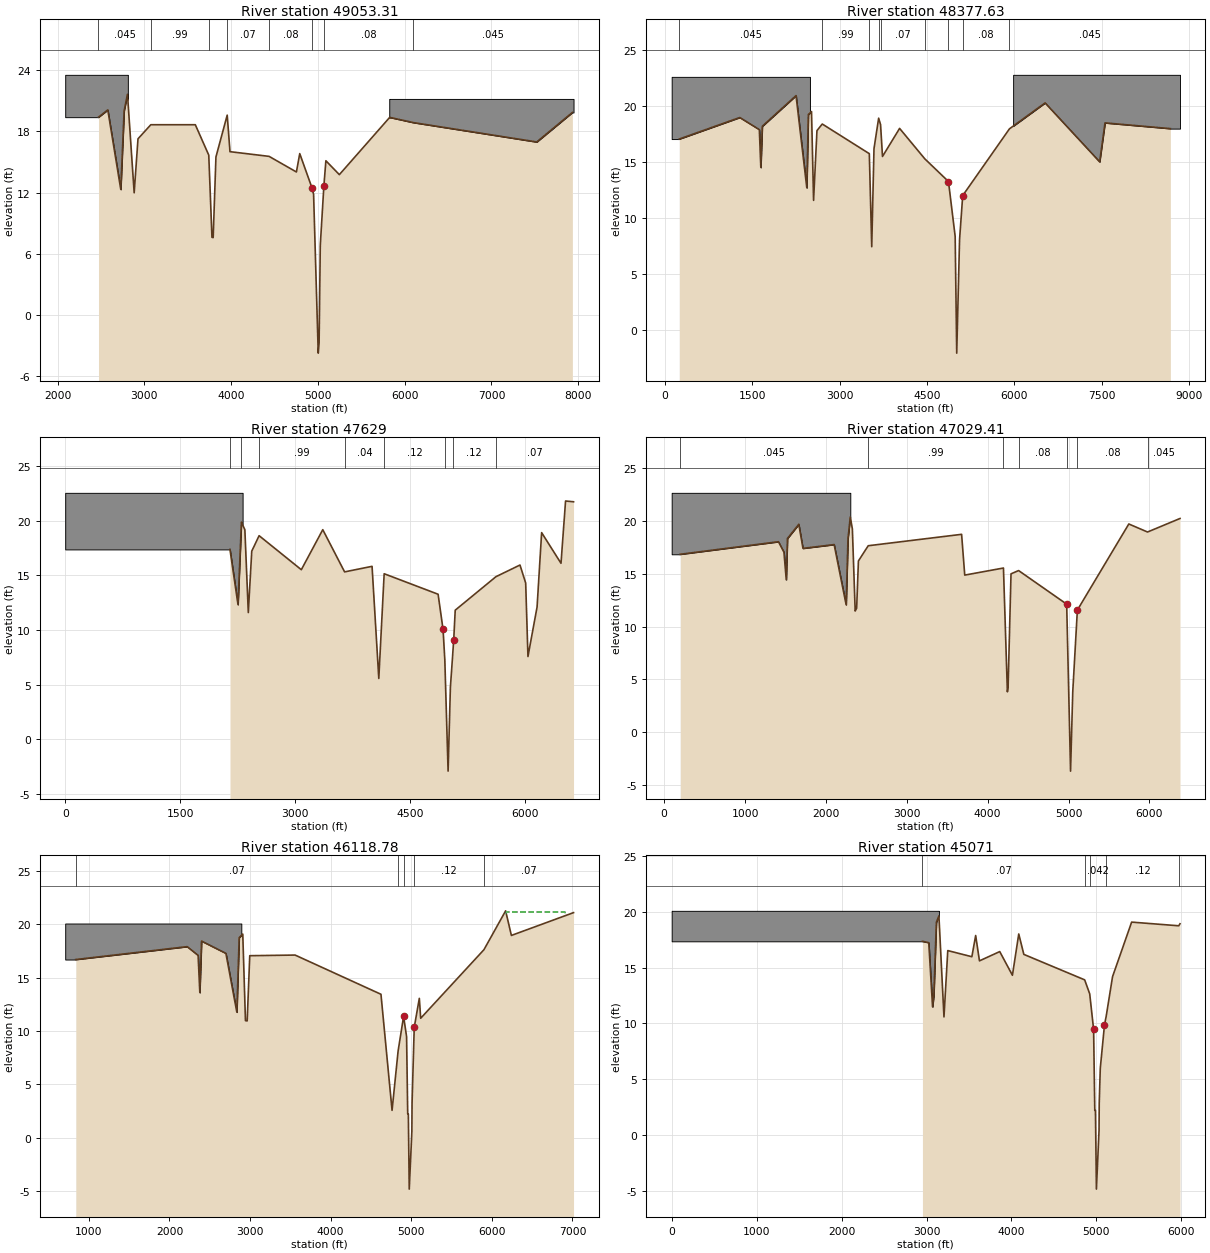
Type RM Length L Ch R = 1 ,49053.31,515.92,675.68,545.27
BEGIN DESCRIPTION:
Modified with survey data (DEC - 06/2009)
END DESCRIPTION:
XS GIS Cut Line= 5
     3205261.792    13798814.374      3202818.27    13798358.718
     3202700.372    13798303.282     3202228.941     13798178.23
     3199874.809    13798044.524
#Sta/Elev= 30
 2471.29    19.4 2578.59   20.11 2728.38   12.32 2766.96   20.02 2805.54   21.65
  2882.7   11.99 2926.79   17.28 3074.53   18.66 3587.45   18.66 3742.45   15.68
 3779.29    7.63 3793.16     7.6  3825.1    15.5 3954.94    19.6    3987   16.02
 4437.46   15.56 4752.62   14.03  4790.9   15.83 4930.95    12.5 4950.55   11.85
 5004.18   -3.72 5013.98   -2.72 5027.73    6.85 5069.05   12.66 5092.21   15.13
 5247.53   13.77 5827.72   19.38 6099.82   18.87 7522.49   16.97 7932.87   19.86
#Mann= 8 ,-1 , 0
 2471.29    .045       0 3074.53     .99       0 3742.45     .04       0
 3954.94     .07       0 4437.46     .08       0 4930.95    .032       0
 5069.05     .08       0 6099.82    .045       0
#Block Obstruct= 2 ,-1
  2087.8 2809.76   23.55 5822.44 7946.46   21.19
Bank Sta=4930.95,5069.05
XS Rating Curve= 0
Exp/Cntr=.3,.1

Type RM Length L Ch R = 1 ,48377.63,698.03,748.22,1109.55
BEGIN DESCRIPTION:
Modified with survey data (DEC - 06/2009)
END DESCRIPTION:
XS GIS Cut Line= 4
      3207149.08    13799442.346     3202751.252    13797755.404
     3202671.133    13797716.114     3199066.238    13797255.097
#Sta/Elev= 30
  243.36   17.04 1283.09   18.96 1619.04   17.88 1644.59   14.51 1669.93   18.18
 2249.29   20.91 2434.18    12.7 2460.46   19.22 2514.94   19.49 2550.29   11.58
 2608.35   17.79 2699.45   18.38  3507.3   15.74 3548.82    7.46 3587.56   16.18
 3667.58    18.9 3700.37   18.33  3733.6   15.49 4027.28   17.99 4460.24   15.28
 4866.48   13.26 4981.31    8.38 5008.04   -2.02  5056.7    8.09 5110.93   12.01
 5913.51   17.95 6525.57   20.26 7462.39   15.01 7554.54   18.48 8677.12   17.97
#Mann= 9 ,-1 , 0
  243.36    .045       0 2699.45     .99       0  3507.3     .04       0
 3667.58     .07       0 3700.37     .07       0 4460.24     .08       0
 4866.48    .042       0 5110.93     .08       0 5913.51    .045       0
#Block Obstruct= 2 ,-1
  113.82  2487.8   22.58 5976.68 8841.64   22.76
Bank Sta=4866.48,5110.93
XS Rating Curve= 0
Exp/Cntr=.3,.1

Type RM Length L Ch R = 1 ,47629   ,559.75,600,889.75
BEGIN DESCRIPTION:
Added from LiDAR and Modified with survey data (DEC - 06/2009)
END DESCRIPTION:
XS GIS Cut Line= 5
 3205294.340611413798617.6341681 3203543.020786413797466.3035424
 3202893.087644613797063.7140141 3201998.4539963 13796887.259912
  3201451.16655113796428.4843868
#Sta/Elev= 30
 2151.55   17.39 2256.34   12.33 2301.26    19.9 2346.17   19.19 2391.08    11.6
 2435.99   17.23 2532.11   18.65 3083.34   15.53 3363.53    19.2 3648.51   15.33
 4007.03   15.84 4095.05    5.56 4165.09   15.16 4869.54   13.28 4934.17   10.05
 4957.14    7.28    5000   -2.94 5029.98    4.76 5058.87    7.63 5073.36     9.1
 5093.06   11.82 5624.84   14.89 5938.69   15.96 6013.08   14.31 6042.84    7.57
 6161.86   12.11 6221.37   18.93  6474.3   16.12 6533.81   21.83 6637.95   21.76
#Mann= 8 ,-1 , 0
 2151.55    .045       0 2301.26     .07       0 2532.11     .99       0
 3648.51     .04       0 4165.09     .12       0 4957.14    .042       0
 5058.87     .12       0 5624.84     .07       0
#Block Obstruct= 2 , 0
       0 2316.55   22.58 5501.55       0    22.5
Bank Sta=4934.17,5073.36
XS Rating Curve= 0
Exp/Cntr=.3,.1

Type RM Length L Ch R = 1 ,47029.41,583.22,910.62,441.33
BEGIN DESCRIPTION:
Modified with survey data (DEC - 06/2009)
END DESCRIPTION:
XS GIS Cut Line= 4
     3207181.544    13799377.418      3203186.31    13796748.213
     3203191.835    13796682.445     3202971.935    13795368.888
#Sta/Elev= 30
  197.69   16.85 1413.06   18.04 1481.13   17.05 1509.62   14.44 1524.45   18.35
 1664.61   19.69 1716.11   17.41 2101.73   17.77 2250.04   12.07 2272.99   18.35
 2301.62   20.39 2327.04   19.25 2361.94   11.48    2380   11.75 2401.86   16.22
 2522.95   17.66 3677.74   18.74 3716.51   14.88 4195.32   15.55  4243.9    3.83
 4252.55    4.25 4288.79      15 4382.46   15.31    4977   12.13    5025   -3.68
  5052.3    3.85 5109.29   11.57 5745.37   19.72 5976.95   18.96 6378.27   20.24
#Mann= 7 ,-1 , 0
  197.69    .045       0 2522.95     .99       0 4195.32     .04       0
 4382.46     .08       0    4977    .042       0 5109.29     .08       0
 5976.95    .045       0
#Block Obstruct= 1 ,-1
   92.67 2301.52   22.67
Bank Sta=4977,5109.29
XS Rating Curve= 0
Exp/Cntr=.3,.1

Type RM Length L Ch R = 1 ,46118.78,662.88,1047.28,1001.72
BEGIN DESCRIPTION:
Modified with survey data (DEC - 06/2009)
END DESCRIPTION:
XS GIS Cut Line= 4
     3207181.544     13799312.49     3203949.915    13796772.754
     3203886.152    13796683.786     3202843.531    13795026.479
#Sta/Elev= 30
  836.27    16.7  2219.5   17.91 2355.13   17.09  2376.5    13.6 2397.86   18.43
 2700.04   17.28 2835.85   11.76 2864.89   18.76 2909.32   19.09 2942.67   10.97
 2964.04   10.94 2996.08   17.06 3558.55   17.12 4624.35   13.44 4761.97    2.55
 4837.21    8.13 4905.08   11.36  4942.2    9.47 4956.13    2.22 4963.99     2.2
 4975.23   -4.84 5007.67     .56 5010.25    3.27 5037.02   10.33 5100.36   13.06
  5117.2   11.19 5901.93   17.62 6171.36   21.27 6242.64   18.96 7013.91    21.1
#Mann= 5 ,-1 , 0
  836.27     .07       0 4837.21     .12       0 4905.08    .042       0
 5037.02     .12       0 5901.93     .07       0
#XS Ineff= 1 ,-1
 6179.75 6912.65   21.18
Permanent Ineff=
       F
#Block Obstruct= 1 ,-1
  705.91 2891.27   20.08
Bank Sta=4905.08,5037.02
XS Rating Curve= 0
Exp/Cntr=.3,.1

Type RM Length L Ch R = 1 ,45071   ,63.29,100,95.65
BEGIN DESCRIPTION:
Added from LiDAR (DEC - 06/2009)
END DESCRIPTION:
XS GIS Cut Line= 4
  3205892.36926513797933.5226202 3204684.242747613796454.3184539
 3204617.170000113796305.1499996 3204231.702506213795427.4063366
#Sta/Elev= 30
 2951.91   17.35 3026.51   17.23 3071.28   11.48  3086.2    12.5 3116.04   19.04
 3145.88   19.63 3205.56   10.58 3250.33   16.52 3533.82   15.97 3578.59   17.87
 3623.35    15.6 3862.08   16.43 4011.29   14.31  4085.9   18.01 4145.58   16.18
 4861.7813.89949 4921.2612.64249 4966.97    9.47  4980.9    2.22 4988.76     2.2
    5000   -4.84 5030.83      .4 5033.28    2.89 5045.57    5.98  5095.2    9.87
 5115.2110.63922 5190.11   14.19 5414.79   19.07 5969.02   18.74 5983.99   18.92
#Mann= 5 ,-1 , 0
 2951.91     .07       0 4861.78    .074       0 4921.26    .042       0
 5115.21     .12       0 5969.02    .116       0
#Block Obstruct= 2 , 0
       0 3145.91   20.08               0
Bank Sta=4966.97,5095.2
XS Rating Curve= 0
Exp/Cntr=.3,.1