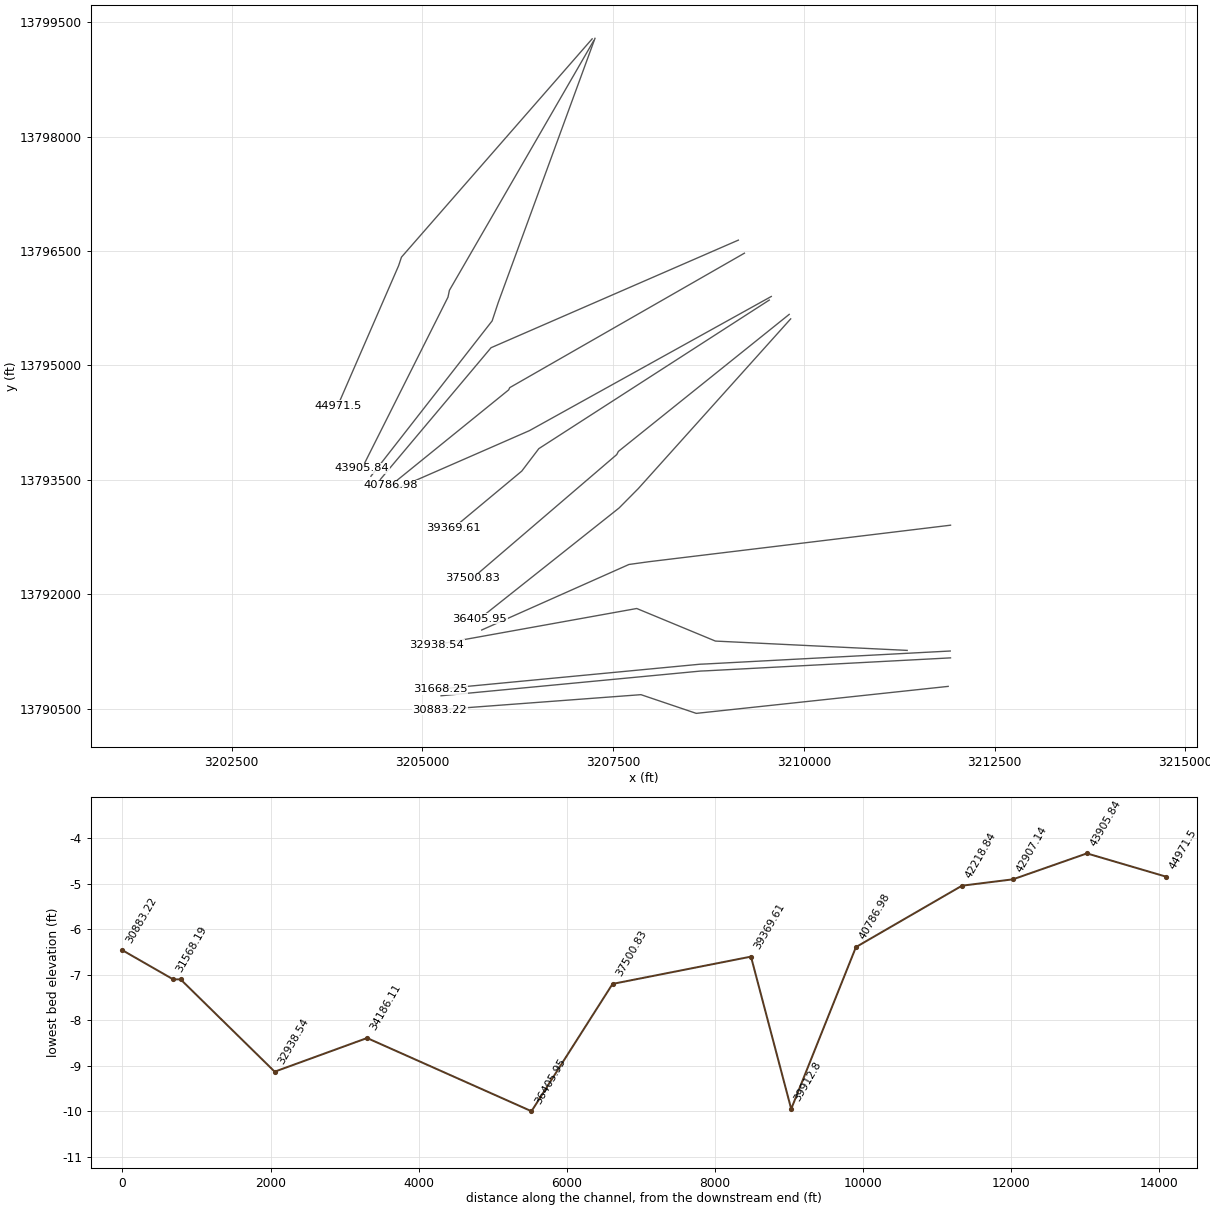
HEC-RAS study B100-00-00.prj: B100-00-00

--- B100-00-00.g01 (geometry) --- (continued)

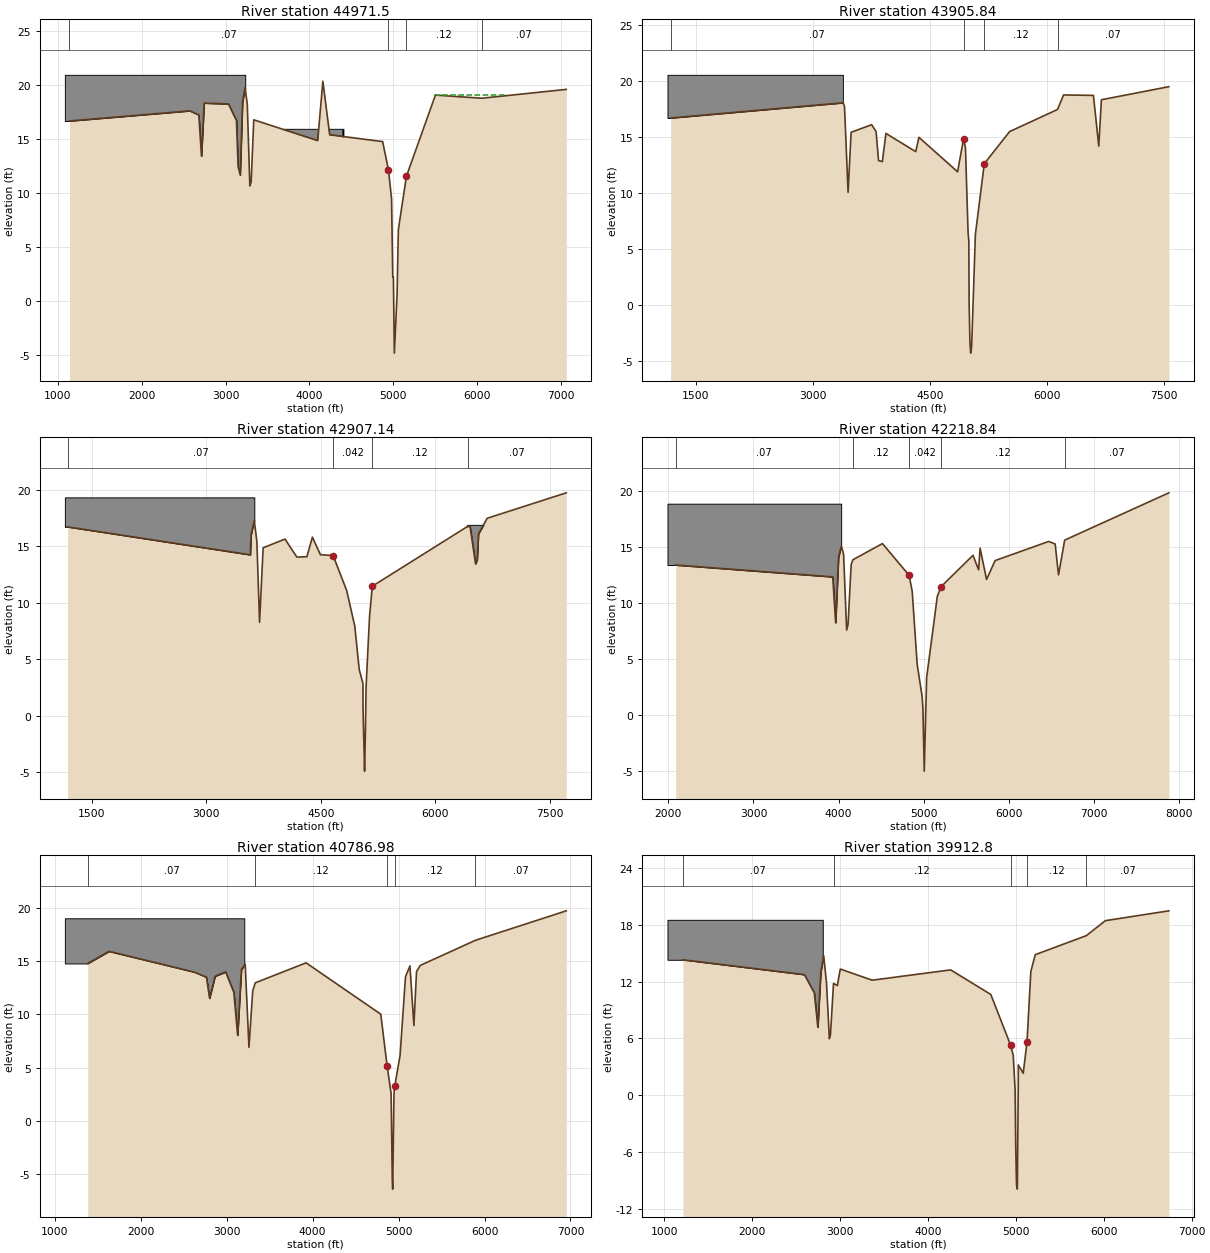
Type RM Length L Ch R = 1 ,44971.5 ,876.16,1065.66,948.43
XS GIS Cut Line= 4
      3207224.83    13799280.026     3204725.082     13796418.51
     3204687.773    13796306.724     3203890.085    13794472.265
#Sta/Elev= 30
 1141.57   16.68 2574.63   17.62 2682.17   17.24 2713.89   13.42 2745.78   18.34
 3034.74   18.26 3130.35   16.73 3149.75   12.47 3175.12   11.67  3202.9    18.4
 3233.12   19.79 3259.66   18.21 3289.84   10.66 3305.63   11.01 3336.59   16.79
 4098.09   14.86 4159.67   20.36 4241.42    15.4 4871.67   14.77 4941.08   12.17
  4978.2    9.47 4992.13    2.22 4999.99     2.2 5011.23   -4.84 5043.67     .56
 5059.18    6.61  5154.9   11.55 5500.45   19.08 6053.38   18.79 7059.41   19.61
#Mann= 4 ,-1 , 0
 1141.57     .07       0 4941.08    .042       0  5154.9     .12       0
 6053.38     .07       0
#XS Ineff= 1 ,-1
 5496.82 6322.83   19.05
Permanent Ineff=
       F
#Block Obstruct= 3 ,-1
 1086.34 3234.87   20.96 3380.57 4410.26   15.91 4391.36 4400.81   15.85
Bank Sta=4941.08,5154.9
XS Rating Curve= 0
Exp/Cntr=.3,.1

Type RM Length L Ch R = 1 ,43905.84,597.34,998.7,669.38
XS GIS Cut Line= 5
 3207244.597506213799255.1368152     3206150.639    13797362.559
     3205353.811    13795984.025     3205334.886    13795894.084
     3204207.437    13793649.164
#Sta/Elev= 30
 1177.44    16.7 3386.22   18.06 3404.66   17.74 3450.49   10.05 3489.25   15.42
 3753.16    16.1 3808.82   15.49 3840.96   12.89 3889.34    12.8 3935.41   15.32
 4316.93   13.69 4357.76   14.97 4853.38   11.89 4929.19   14.82 4954.04   14.04
 4987.88    6.38 4997.22    5.75 5000.96     .17 5010.96   -3.33 5020.96   -4.33
    5033   -3.79    5081    6.28  5195.1   12.61 5518.74   15.48    6133   17.46
 6210.69   18.76 6593.01   18.72  6661.6   14.19 6695.17   18.33 7559.74    19.5
#Mann= 4 ,-1 , 0
 1177.44     .07       0 4929.19    .042       0  5195.1     .12       0
    6133     .07       0
#XS Ineff= 1 ,-1
 6576.88 6745.67   18.32
Permanent Ineff=
       F
#Block Obstruct= 2 ,-1
 1137.14 3383.58   20.56 3363.44  3385.4   18.05
Bank Sta=4929.19,5195.1
XS Rating Curve= 0
Exp/Cntr=.3,.1

Type RM Length L Ch R = 1 ,42907.14,1049.35,688.3,370.46
XS GIS Cut Line= 5
 3207261.964927913799286.9521276     3206439.714    13797041.783
     3205994.033    13795824.844     3205913.746    13795582.589
      3204324.36    13793545.997
#Sta/Elev= 30
 1186.71    16.7 3577.71   14.23 3587.65   15.99 3629.62   17.26  3663.6   15.41
 3698.68    8.26 3745.45   14.85 4031.42   15.62 4186.38   14.03  4317.8   14.06
 4390.02   15.79    4495   14.24 4661.25   14.16 4838.83   11.07 4944.63    7.92
 5002.75    4.09 5051.66    2.85 5052.66     .61 5072.64    -4.9 5082.63    -1.9
 5092.62    2.55    5138     8.8 5173.88   11.45 6430.57   16.78 6453.25   16.72
 6525.27   13.43 6547.07   13.83 6563.32   16.08 6677.48   17.46 7712.29   19.71
#Mann= 4 ,-1 , 0
 1186.71     .07       0 4661.25    .042       0 5173.88     .12       0
 6430.57     .07       0
#Block Obstruct= 2 ,-1
 1150.93 3630.07   19.31 6414.31  6724.7   16.88
Bank Sta=4661.25,5173.88
XS Rating Curve= 0
Exp/Cntr=.3,.1

Type RM Length L Ch R = 1 ,42218.84,535.39,1431.86,535.09
XS GIS Cut Line= 4
 3209141.412082613796641.5532524     3207450.509    13795905.902
     3205899.379    13795231.061     3204448.161     13793504.73
#Sta/Elev= 30
 2086.41    13.4 3930.41   12.34 3964.68    8.24 3998.88   14.14 4031.62    15.1
 4057.62   14.38 4093.72    7.58 4110.55     8.1 4147.07   13.46 4167.22   13.87
 4514.22   15.32 4826.86   12.48 4863.35   11.06 4922.16     4.5 4979.64    1.66
 4989.21     .62 5004.81   -5.04    5033    3.33 5158.41    10.6 5201.92   11.46
 5577.23   14.27 5643.57   12.97 5660.24   14.91 5736.68   12.11 5837.14    13.8
 6465.87   15.51 6542.06   15.28 6581.25   12.52 6653.73   15.63 7877.25   19.86
#Mann= 5 ,-1 , 0
 2086.41     .07       0 4167.22     .12       0 4826.86    .042       0
 5201.92     .12       0 6653.73     .07       0
#Block Obstruct= 1 ,-1
 1990.28 4029.65   18.89
Bank Sta=4826.86,5201.92
XS Rating Curve= 0
Exp/Cntr=.3,.1

Type RM Length L Ch R = 1 ,40786.98,1367.88,874.17,489.65
XS GIS Cut Line= 4
     3209220.895    13796470.424     3206144.748     13794707.99
      3206129.97    13794677.961     3204584.426    13793425.688
#Sta/Elev= 30
 1383.64   14.79  1630.7   15.93 2628.18   13.97 2764.22    13.5 2801.14   11.52
 2864.68   13.59 2987.99      14 3083.53   12.07 3127.49    8.05 3171.45   14.22
 3215.41   14.72 3259.22    6.92 3302.94   12.21 3332.41   12.97 3923.87   14.85
 4792.93   10.03 4867.27    5.15 4913.27    2.59 4926.73   -5.39 4931.73   -6.39
 4946.73    2.62 4956.73    3.32 5017.84    6.18 5080.47   13.54 5132.49   14.56
 5178.69    8.96 5209.05   14.03 5253.47   14.61 5893.66   16.96 6951.56   19.73
#Mann= 5 ,-1 , 0
 1383.64     .07       0 3332.41     .12       0 4867.27    .042       0
 4956.73     .12       0 5893.66     .07       0
#Block Obstruct= 1 ,-1
 1117.07 3204.88   19.03
Bank Sta=4867.27,4956.73
XS Rating Curve= 0
Exp/Cntr=.3,.1

Type RM Length L Ch R = 1 ,39912.8 ,216.49,543.2,569.17
XS GIS Cut Line= 4
     3209573.168    13795902.872     3206403.133    13794144.296
     3205838.684    13793897.143     3204660.175    13793382.403
#Sta/Elev= 30
 1213.76   14.32 2595.76   12.75 2708.81   10.82  2749.1    7.18  2782.2   12.99
  2815.3   14.76 2847.39   11.89 2879.91    5.97 2892.53     6.4 2927.24   11.82
 2971.01   11.59 3004.02   13.34 3366.69   12.16 4259.49   13.25 4715.83   10.65
 4940.52     5.3 4971.02     4.2 4992.05     .56 4999.24   -5.45 5008.06   -9.45
 5017.48   -9.95 5027.91     .72 5028.98    3.19 5084.54    2.31 5127.76    5.63
 5171.16   13.08 5221.39   14.86 5801.46   16.87 6018.96   18.46 6741.11    19.5
#Mann= 5 ,-1 , 0
 1213.76     .07       0 2927.24     .12       0 4940.52    .042       0
 5127.76     .12       0 5801.46     .07       0
#Block Obstruct= 1 ,-1
 1039.02 2804.88   18.55
Bank Sta=4940.52,5127.76
XS Rating Curve= 0
Exp/Cntr=.3,.1

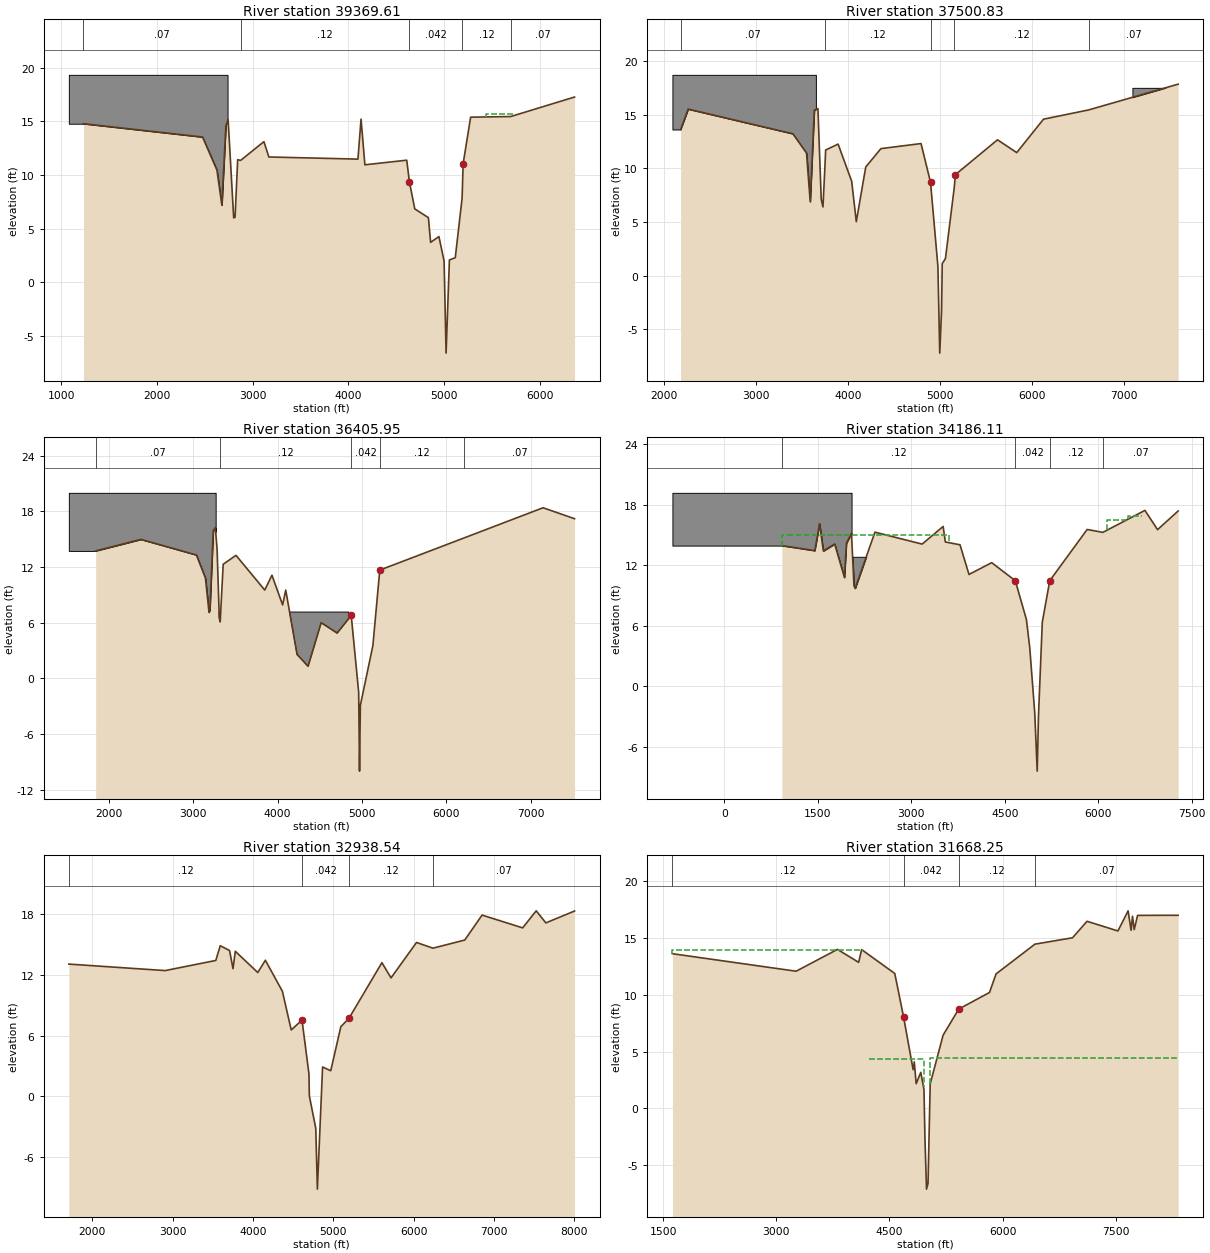
Type RM Length L Ch R = 1 ,39369.61,570.1,1868.78,1213.76
XS GIS Cut Line= 4
     3209546.927    13795855.775     3206526.045    13793908.229
     3206302.429    13793613.826     3205405.533    13792867.002
#Sta/Elev= 30
 1231.23   14.79 2475.22   13.55 2625.62   10.47 2677.39    7.19 2719.17   14.61
 2742.53   15.18 2800.71    6.01 2815.11    6.07 2842.33   11.44 2873.17   11.37
 3116.74   13.12 3168.17   11.69 4098.98   11.49 4131.46   15.22 4171.79   10.96
 4608.91   11.39 4637.17    9.35 4692.83    6.85 4835.36    6.03 4858.29    3.73
 4945.18    4.27 4999.37    1.98  5020.1    -6.6 5054.82    2.09  5116.1     2.3
 5187.29    7.84 5198.39   11.06 5276.57    15.4 5695.26   15.46  6362.3   17.28
#Mann= 5 ,-1 , 0
 1231.23     .07       0 2873.17     .12       0 4637.17    .042       0
 5187.29     .12       0 5695.26     .07       0
#XS Ineff= 1 ,-1
 5441.78 5732.72   15.67
Permanent Ineff=
       F
#Block Obstruct= 1 ,-1
 1078.05 2736.59   19.35
Bank Sta=4637.17,5198.39
XS Rating Curve= 0
Exp/Cntr=.3,.1

Type RM Length L Ch R = 1 ,37500.83,466.68,1094.87,580.85
XS GIS Cut Line= 4
     3209808.017    13795668.023     3207568.759    13793871.516
     3207546.857    13793829.932     3205651.762     13792206.13
#Sta/Elev= 30
 2176.89   13.62 2258.86   15.52 3398.59   13.22 3546.86   11.43 3587.06     6.9
 3631.95   15.42 3671.08   15.57 3707.07    7.11 3725.78    6.41 3746.79   10.09
  3755.1   11.71 3890.64   12.26 4038.26     8.8 4088.57    5.04 4191.32   10.13
 4356.68   11.84 4793.06   12.31 4896.07    8.71  4976.5     .89  4996.5    -7.2
  5016.5    -3.2  5023.5    1.13  5058.5     1.6 5154.33    8.21 5167.19    9.42
 5624.89   12.66 5834.28   11.47 6125.45   14.58 6615.93   15.44 7590.35   17.84
#Mann= 5 ,-1 , 0
 2176.89     .07       0 3746.79     .12       0 4896.07    .042       0
 5154.33     .12       0 6615.93     .07       0
#Block Obstruct= 2 ,-1
  2087.8 3648.78   18.71 7092.84 7643.31    17.5
Bank Sta=4896.07,5167.19
XS Rating Curve= 0
Exp/Cntr=.3,.1

Type RM Length L Ch R = 1 ,36405.95,2147.85,2219.84,793.75
XS GIS Cut Line= 4
     3209827.588    13795609.311     3207829.004    13793383.381
     3207577.544    13793129.703     3205751.866    13791680.587
#Sta/Elev= 30
 1842.15   13.74 2378.99   14.98  3036.6    13.3 3143.87   10.81 3186.36    7.12
 3196.72    7.39 3236.53    15.9 3260.71   16.26 3281.96   13.99 3308.02    6.52
 3318.84    6.09  3354.5    12.3 3506.53   13.26 3847.29    9.52 3932.74   11.12
 4059.32    7.92 4096.38    9.51 4230.64    2.58 4361.31     1.3 4516.81       6
 4706.28    4.88 4873.15    6.78 4961.46    -1.5 4971.46     -10 4981.46    -2.9
 5129.75    3.52 5211.64   11.67 6215.43   15.15 7148.73   18.39 7521.73   17.21
#Mann= 5 ,-1 , 0
 1842.15     .07       0 3318.84     .12       0 4873.15    .042       0
 5211.64     .12       0 6215.43     .07       0
#Block Obstruct= 2 ,-1
 1523.58 3265.04      20 1842.15  4841.4    7.15
Bank Sta=4873.15,5211.64
XS Rating Curve= 0
Exp/Cntr=.3,.1

Type RM Length L Ch R = 1 ,34186.11,1405.08,1247.57,503.74
XS GIS Cut Line= 4
     3211923.195    13792904.429     3207968.431    13792425.572
     3207707.345    13792389.516     3205776.892    13791530.431
#Sta/Elev= 30
  923.12   13.96  1451.8   13.46  1528.9   16.13 1589.85   13.43 1771.17   14.12
  1928.2    10.8 1959.98    14.2 2040.85   15.18 2081.28    9.97 2100.11    9.72
 2417.56   15.29 3174.87   14.11 3512.27   15.86 3547.37   14.32 3782.74   14.04
 3926.94    11.1 4291.22   12.27 4670.32   10.48 4848.32    6.64 4902.57    3.81
    4982   -2.59 5021.78   -8.39 5041.73   -2.99 5103.36    6.37 5223.11   10.48
 5823.48   15.56 6074.88   15.27 6750.59   17.45 6953.04   15.54 7283.31   17.39
#Mann= 4 ,-1 , 0
  923.12     .12       0 4670.32    .042       0 5223.11     .12       0
 6074.88     .07       0
#XS Ineff= 4 ,-1
  891.92  3604.1   15.06 6137.76 6450.72   16.49  6473.9 6702.83   16.93
 6746.29 7351.92   17.38
Permanent Ineff=
       F       F       F       F
#Block Obstruct= 2 ,-1
 -832.52 2042.28   19.19 1993.17 2302.62   12.85
Bank Sta=4670.32,5223.11
XS Rating Curve= 0
Exp/Cntr=.3,.1

Type RM Length L Ch R = 1 ,32938.54,291.81,1270.29,840.46
XS GIS Cut Line= 4
     3211354.645    13791263.144     3208840.771    13791385.277
     3207809.374    13791812.363     3205186.547    13791339.896
#Sta/Elev= 30
 1706.04   13.05 2906.48   12.41 3536.61   13.41 3592.03   14.86 3707.76   14.39
 3750.73    12.6 3779.37   14.31  4059.3   12.22 4153.84   13.43  4365.8   10.37
 4475.84    6.56 4610.29    7.53  4696.7    2.22  4701.5     .06 4781.48   -3.13
 4801.45   -9.13 4866.36    2.91 4968.11    2.54 5093.56    6.88 5193.71    7.69
 5605.15   13.19 5718.89   11.69 6036.08   15.18 6240.75   14.62 6637.16   15.42
 6852.75   17.88 7358.06   16.62 7527.02    18.3  7647.1   17.11 8004.25   18.28
#Mann= 4 ,-1 , 0
 1706.04     .12       0 4610.29    .042       0 5193.71     .12       0
 6240.75     .07       0
#Block Obstruct= 1 ,-1
 6043.92 6221.67   14.54
Bank Sta=4610.29,5193.71
XS Rating Curve= 0
Exp/Cntr=.5,.3

Type RM Length L Ch R = 1 ,31668.25,90.78,100.05,129.33
XS GIS Cut Line= 5
 3211919.169962313791255.0308785     3211339.154    13791224.289
     3208725.355    13791085.753      3208641.05    13791082.131
     3205235.264    13790757.763
#Sta/Elev= 30
    1624    13.6 3263.71   12.06 3812.01   13.98 4092.57   12.84 4132.68   13.96
 4571.78   11.86 4688.04    8.05 4815.14     3.4 4830.16    4.09 4855.28    2.17
 4916.55    3.17 4958.75    1.64 4972.54    -2.9 4992.54    -7.1 5012.38    -6.6
 5041.25    2.15 5212.48    6.44 5419.54    8.73 5827.32   10.19 5914.08   11.82
 6429.73   14.44 6927.78      15  7120.2   16.45 7530.03    15.6 7664.69   17.37
 7704.29   15.66 7722.92   16.89 7745.64   15.72 7790.76   16.97 8327.88   16.98
#Mann= 4 ,-1 , 0
    1624     .12       0 4688.04    .042       0 5419.54     .12       0
 6429.73     .07       0
#XS Ineff= 3 ,-1
 1605.25 4144.37   13.95 4227.29  4953.2    4.35 5041.25 8327.88     4.4
Permanent Ineff=
       F       F       F
#Block Obstruct= 1 ,-1
 6442.55 6679.18   14.37
Bank Sta=4688.04,5419.54
XS Rating Curve= 0
Exp/Cntr=.5,.3

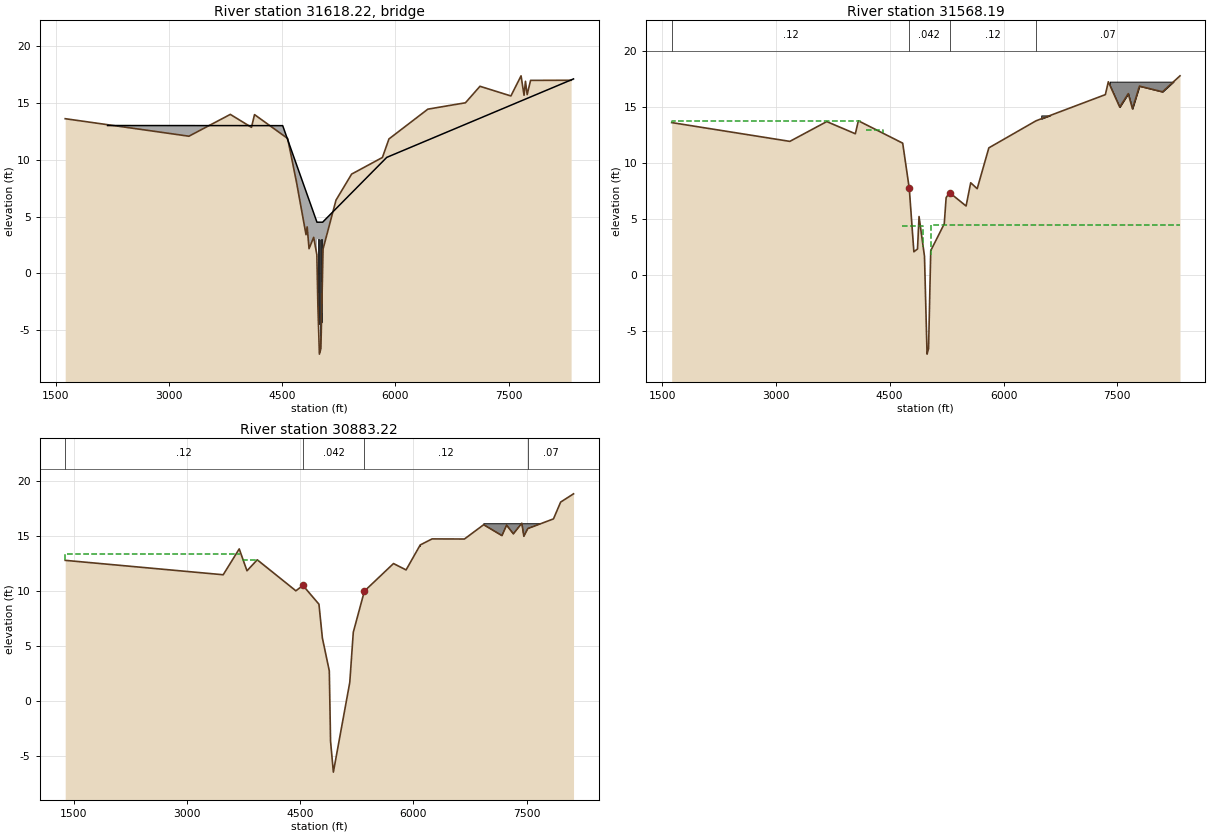
Type RM Length L Ch R = 3 ,31618.22,,,
BEGIN DESCRIPTION:
Bridge at Red Bluff Road
END DESCRIPTION:
Bridge Culvert--1,0,-1,-1, 0
Deck Dist Width WeirC Skew NumUp NumDn MinLoCord MaxHiCord MaxSubmerge Is_Ogee
47,16,2.6,0, 8, 8, , , .95, 0, 0,0,,
    2185    4506    4960    4960    5035    5035    5885    8360
      13   12.99     4.5     4.5     4.5     4.5    10.2    17.1
                               3       3
    2185    4506    4960    4960    5035    5035    5885    8360
      13   12.99     4.5     4.5     4.5     4.5    10.2    17.1
                               3       3
Pier Skew, UpSta & Num, DnSta & Num=  ,4980, 2 ,4980, 2 , 0 , 0 , 0 ,,
       1       1
     -10       3
       1       1
     -10       3
Pier Skew, UpSta & Num, DnSta & Num=  ,5000, 2 ,5000, 2 , 0 , 0 , 0 ,,
       1       1
     -10       3
       1       1
     -10       3
Pier Skew, UpSta & Num, DnSta & Num=  ,5020, 2 ,5020, 2 , 0 , 0 , 0 ,,
       1       1
     -10       3
       1       1
     -10       3
BR Coef=-1 , 1 , 0 ,, 0 ,,,.8,0,1.2,0,
WSPro=,,,, 1 ,,,, 0 ,,,, 0 ,,,,-1 ,-1 ,-1 , 0 , 0 , 0 , 0 , 0
BC Design=,, 0 ,, 0 ,,,,,,
BC HTab HWMax=17.37

Type RM Length L Ch R = 1 ,31568.19,622.03,684.97,299.17
XS GIS Cut Line= 5
 3211922.665721213791165.0896925     3211343.918    13791134.415
     3208729.669    13790995.855     3208647.252    13790992.315
     3205243.797    13790668.169
#Sta/Elev= 30
    1627    13.6  3184.5   11.92 3670.67   13.69 4047.66    12.6 4087.29   13.76
 4671.43   11.76  4758.3    7.71  4818.8    2.05 4866.69     2.3 4886.93     5.2
 4958.75    1.64 4992.54    -7.1 5012.38    -6.6 5041.25    2.15 5219.17    4.55
 5243.95    6.89  5289.3    7.34 5506.85    6.14 5567.67    8.22 5653.14    7.69
 5806.77   11.34 6428.85   13.76 7342.52    16.1 7381.24   17.25 7531.74   14.98
 7644.28   16.19  7699.3   14.83  7791.6   16.86 8095.26   16.35 8325.83   17.78
#Mann= 4 ,-1 , 0
    1627     .12       0  4758.3    .042       0  5289.3     .12       0
 6428.85     .07       0
#XS Ineff= 4 ,-1
 1259.33 4106.66   13.72 4182.61 4406.18   12.97 4667.85 4941.89    4.38
    5040 8325.83     4.4
Permanent Ineff=
       F       F       F       F
#Block Obstruct= 2 ,-1
 6497.16 6624.57   14.24    7400  8362.6   17.26
Bank Sta=4758.3,5289.3
XS Rating Curve= 0
Exp/Cntr=.5,.3

Type RM Length L Ch R = 1 ,30883.22,549.41,849.62,939.92
XS GIS Cut Line= 4
     3211892.105    13790791.265     3208589.873     13790437.45
     3207864.853    13790682.678      3205226.43    13790485.482
#Sta/Elev= 30
 1388.13    12.8  3480.6   11.49 3692.81   13.84 3795.73   11.85 3931.53   12.85
 4443.06   10.03 4536.65   10.52 4748.72    8.81 4794.09    5.74 4885.83    2.75
 4902.42   -3.66 4939.69   -6.46    5157     1.7 5203.53    6.26 5350.44      10
 5736.03   12.51 5902.63   11.93    6090    14.2 6246.68   14.75 6675.41   14.74
 6930.09   16.04 7172.62   15.05 7233.91      16 7323.58   15.21 7435.45   16.18
 7462.51   14.99 7514.51   15.69 7854.61   16.57 7949.84    18.1 8120.41   18.85
#Mann= 4 ,-1 , 0
 1388.13     .12       0 4536.65    .042       0 5350.44     .12       0
 7514.51     .07       0
#XS Ineff= 2 ,-1
 1335.93 3697.43   13.39 3732.76 3947.45   12.87
Permanent Ineff=
       F       F
#Block Obstruct= 2 ,-1
 6083.19 6220.08   14.17 6931.71 7842.28   16.13
Bank Sta=4536.65,5350.44
XS Rating Curve= 0
Exp/Cntr=.3,.1