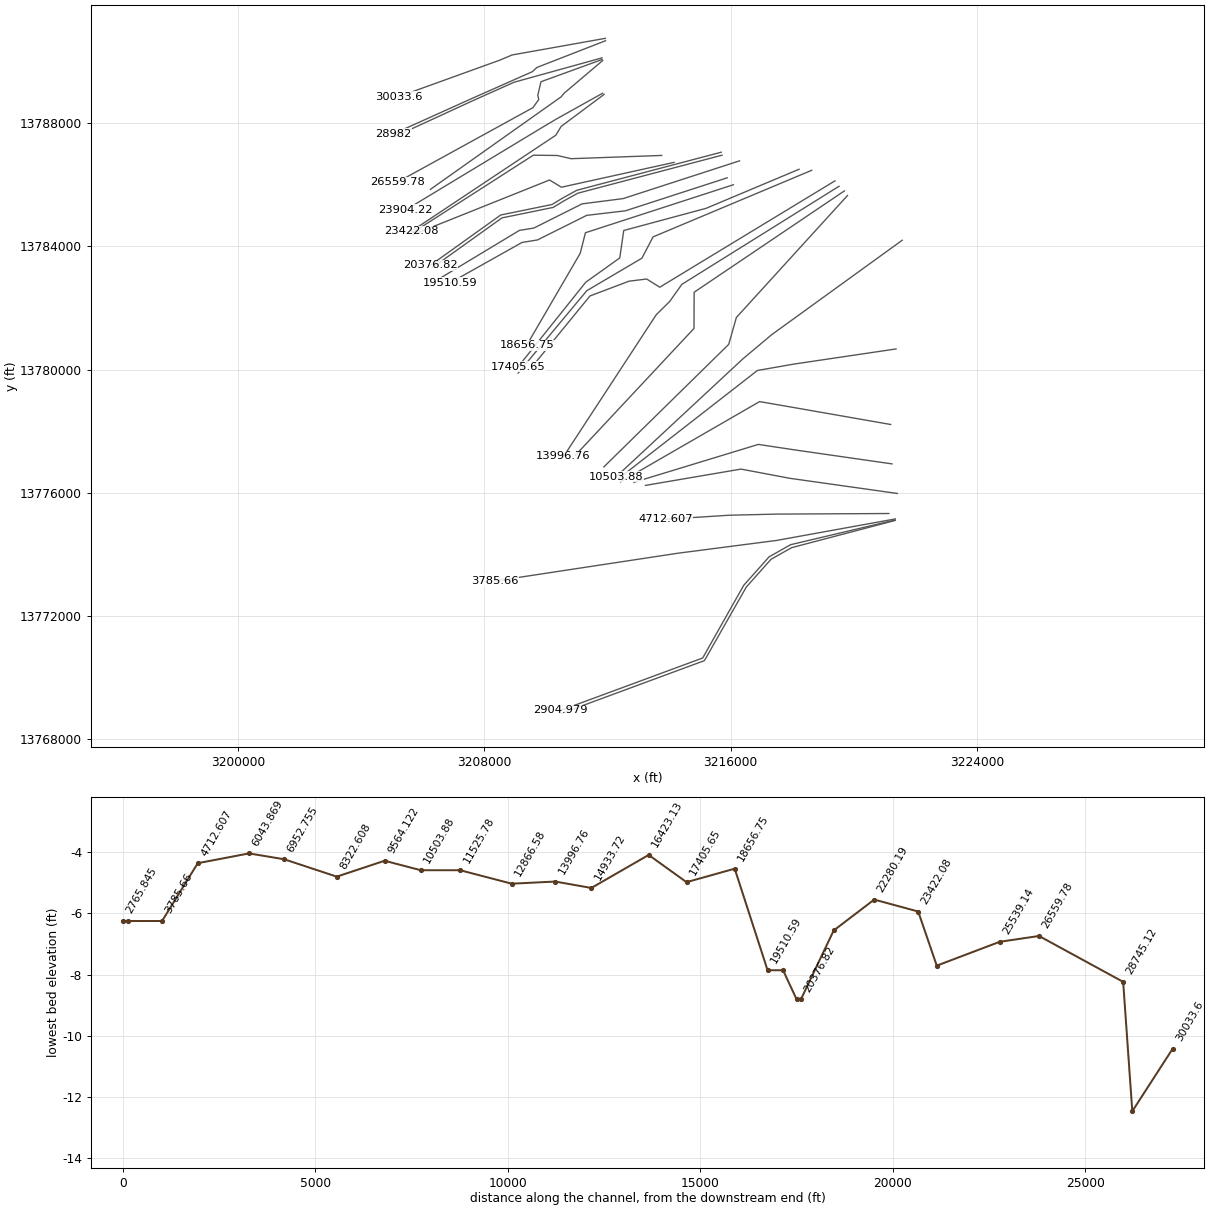
HEC-RAS study B100-00-00.prj: B100-00-00

--- B100-00-00.g01 (geometry) --- (continued)

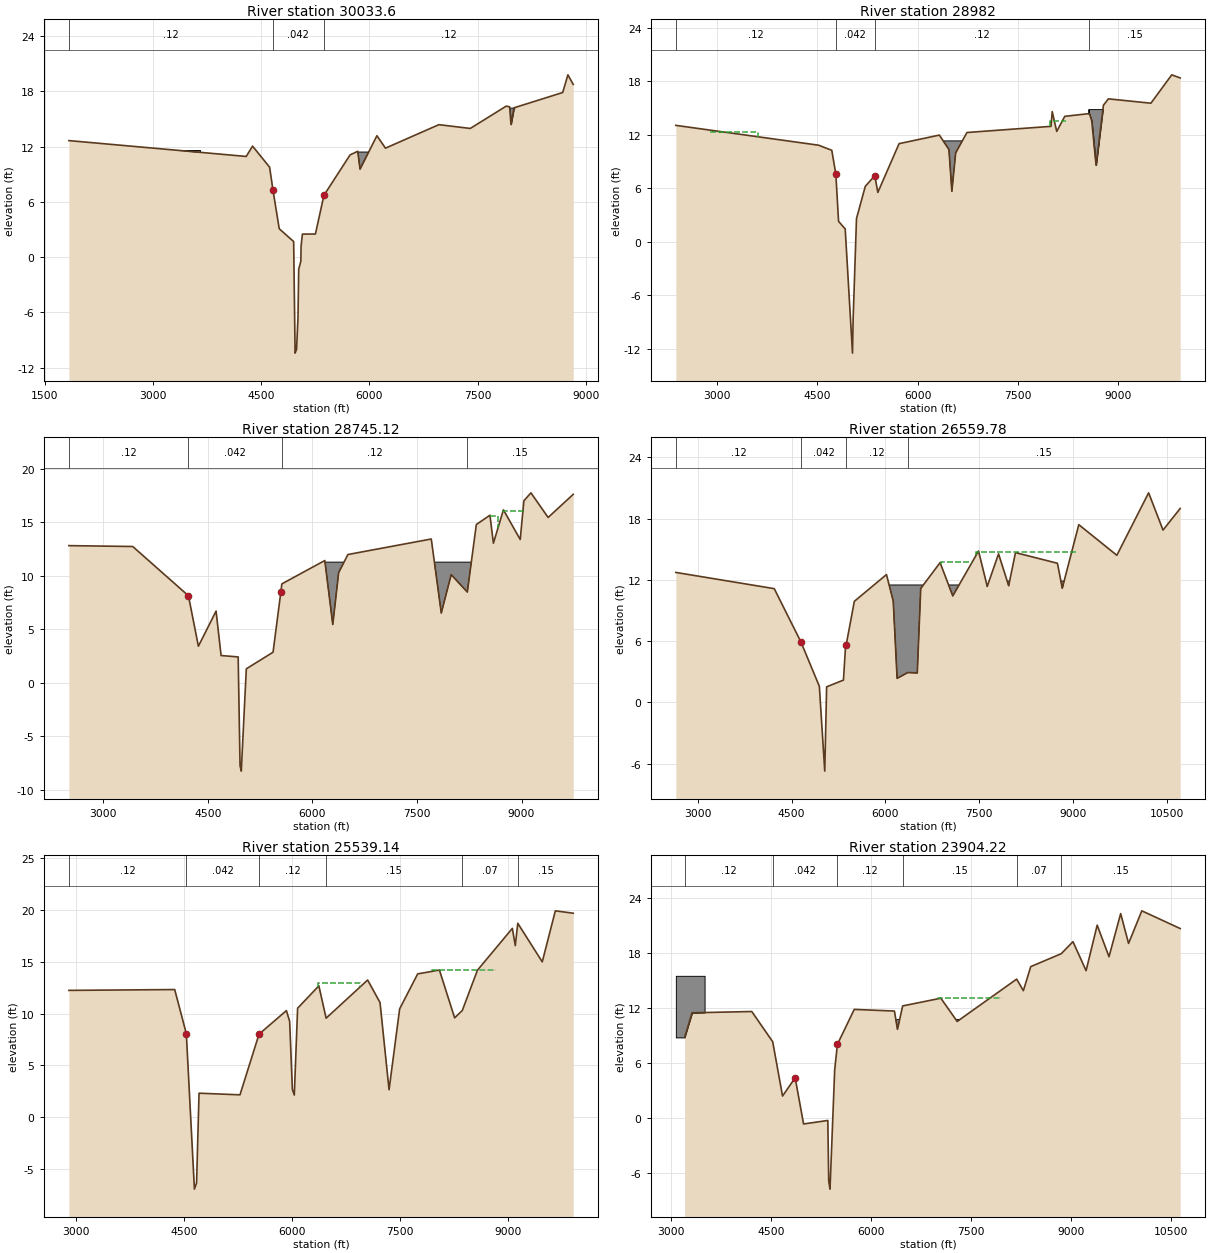
Type RM Length L Ch R = 1 ,30033.6 ,650.57,1051.59,1236.44
XS GIS Cut Line= 4
     3211930.805    13790752.565     3208901.377    13790212.101
      3208515.84    13790048.247      3205226.43    13788861.003
#Sta/Elev= 30
 1832.04   12.65 4290.95   10.93 4379.02   12.05 4615.51    9.76 4661.11    7.32
 4748.67    3.08 4948.77    1.69  4968.7  -10.42 4988.67  -10.02 5008.68   -6.62
 5018.68   -1.32 5048.71    -.42 5051.23    1.15 5069.68     2.5 5250.44    2.51
 5368.42    6.71 5731.38    11.1 5837.43   11.49 5869.32    9.55 6103.01   13.18
 6221.68   11.83 6962.33   14.38 7397.68   13.97 7895.55   16.39  7943.1   16.32
 7962.06   14.41 8004.13   16.21    8679   17.87 8751.33   19.79 8825.32   18.75
#Mann= 3 , 0 , 0
 1832.04     .12       0 4661.11    .042       0 5368.42     .12       0
#Block Obstruct= 3 ,-1
 3111.49 3648.46   11.58 5815.11 8825.32   11.41 7942.34 8019.53   16.23
Bank Sta=4661.11,5368.42
XS Rating Curve= 0
Exp/Cntr=.3,.1

Type RM Length L Ch R = 1 ,28982   ,312.15,236.88,82.58
XS GIS Cut Line= 5
     3211938.545    13790675.166     3209706.659    13789806.032
     3209564.611    13789671.274     3207596.523    13788798.694
     3205049.214    13787650.028
#Sta/Elev= 30
 2384.28   13.04 4516.77   10.82 4714.94   10.25 4775.82    7.57 4816.41    2.29
 4915.71    1.44 5024.56  -12.47 5034.54   -8.57 5084.34     2.6 5215.83    6.21
 5357.99    7.41 5403.36    5.53 5720.85   10.99 6322.68   11.95 6466.13   10.34
 6509.74    5.66 6566.76    9.96 6735.29   12.24  7991.6   12.93 8009.68   14.58
 8077.07   12.36 8197.15   14.05 8565.53   14.36 8599.77   13.56 8665.32    8.58
 8774.79   15.29 8849.26   16.01  9484.3   15.52 9796.51    18.7 9922.39   18.35
#Mann= 4 ,-1 , 0
 2384.28     .12       0 4775.82    .042       0 5357.99     .12       0
 8565.53     .15       0
#XS Ineff= 3 ,-1
 2887.51 3612.06   12.29 6956.67 7458.99   12.25 7976.53 8218.31   13.57
Permanent Ineff=
       F       F       F
#Block Obstruct= 3 ,-1
 6318.45 9922.37    11.3 8548.63  8783.6   14.86 8552.04 8558.85   14.78
Bank Sta=4775.82,5357.99
XS Rating Curve= 0
Exp/Cntr=.3,.1

Type RM Length L Ch R = 1 ,28745.12,299.32,2185.34,1318.95
XS GIS Cut Line= 4
     3211822.446    13790117.889     3208966.475    13789327.104
     3207655.236    13788739.982      3205080.94    13787555.962
#Sta/Elev= 30
 2508.01   12.81 3423.68   12.73 4222.94    8.13 4365.49    3.42 4619.03     6.7
 4690.94    2.55    4936    2.42 4962.91   -7.74 4980.61   -8.24 5052.71    1.31
 5436.22    2.86 5548.32    8.49 5562.41    9.24 6178.67   11.42 6292.86    5.45
 6377.01   10.29 6509.93   11.98 7705.53   13.43 7849.12    6.52 7991.21    10.1
 8222.59    8.48 8351.68   14.78 8547.02   15.65 8596.84   13.04 8740.48   16.15
 8981.15   13.38 9033.73   16.99 9134.65   17.74 9381.74   15.44 9741.65    17.6
#Mann= 4 ,-1 , 0
 2508.01     .12       0 4222.94    .042       0 5562.41     .12       0
 8222.59     .15       0
#XS Ineff= 3 ,-1
 7684.55 8386.99   13.23 8540.93 8660.99   15.62 8730.79 9015.57   16.02
Permanent Ineff=
       F       F       F
#Block Obstruct= 1 ,-1
 6150.17 8379.98   11.27
Bank Sta=4222.94,5548.32
XS Rating Curve= 0
Exp/Cntr=.3,.1

Type RM Length L Ch R = 1 ,26559.78,559.14,1020.64,448.63
XS GIS Cut Line= 6
     3211822.446    13790063.709     3209841.016    13789343.893
     3209737.435    13788900.269     3209770.468     13788769.08
     3209580.824    13788502.301     3205169.752    13786078.361
#Sta/Elev= 30
 2650.66   12.73 4223.22   11.14 4649.41    5.92    4944    1.57 5030.29   -6.74
  5060.3    1.52 5328.94    2.18 5364.47    5.66 5369.18    5.51 5503.15     9.9
  6016.7   12.52 6124.47    9.93 6186.77    2.35 6358.02    2.92 6508.74    2.88
  6563.9   11.16 6873.44   13.69 7076.18   10.43 7487.74   14.83 7626.69   11.36
 7807.47   14.55 7969.24   11.43 8078.12   14.67 8748.15   13.63 8825.93   11.19
 9089.63   17.41  9697.9   14.4110205.65   20.5310435.85   16.8810710.14      19
#Mann= 4 ,-1 , 0
 2650.66     .12       0 4649.41    .042       0 5369.18     .12       0
 6358.02     .15       0
#XS Ineff= 2 ,-1
 6881.43 7384.63   13.74 7449.14 9074.84   14.74
Permanent Ineff=
       F       F
#Block Obstruct= 2 ,-1
 6023.4310710.14    11.5 7857.57 9018.79   11.88
Bank Sta=4649.41,5364.47
XS Rating Curve= 0
Exp/Cntr=.3,.1

Type RM Length L Ch R = 1 ,25539.14,718.73,1634.92,461.66
XS GIS Cut Line= 4
     3211845.666    13790032.749     3210598.487    13788976.063
     3210495.386    13788853.265     3206252.383    13785849.558
#Sta/Elev= 30
 2905.43   12.23 4372.71   12.31    4534    8.06  4646.1   -6.93 4676.09   -6.33
 4710.17    2.32  5277.9    2.16 5542.28    8.01 5921.58   10.28 5966.57    9.25
 6004.56    2.67 6031.14    2.14 6076.96   10.51 6371.81   12.67 6472.15    9.55
 7048.35   13.23 7219.86   11.06 7345.05    2.65 7492.08   10.45 7741.92   13.82
  8043.4   14.19 8254.36    9.58 8360.41   10.29  8570.4   14.17 9054.63   18.21
 9095.35   16.55 9129.71    18.7 9469.35   14.98 9650.85    19.9    9899   19.67
#Mann= 6 ,-1 , 0
 2905.43     .12       0    4534    .042       0 5542.28     .12       0
 6472.15     .15       0 8360.41     .07       0 9129.71     .15       0
#XS Ineff= 4 ,-1
 5897.24 6077.62   10.04 6355.12 6937.89   12.95 7048.89 7749.59   13.09
 7936.91 8831.87    14.2
Permanent Ineff=
       F       F       F       F
#Block Obstruct= 2 , 0
                         8009.76           13.15
Bank Sta=4534,5542.28
XS Rating Curve= 0
Exp/Cntr=.3,.1

Type RM Length L Ch R = 1 ,23904.22,236.93,482.13,546.11
BEGIN DESCRIPTION:
Xsec blocked at basin boundary on left
END DESCRIPTION:
XS GIS Cut Line= 4
     3211845.666    13788972.374     3210367.532    13788147.782
     3209864.777    13787849.488     3205443.742    13785178.107
#Sta/Elev= 30
 3202.61    8.82 3314.94    11.5  4211.5   11.64 4525.46    8.35 4673.32    2.43
 4862.83    4.42  4989.2    -.61 5353.37    -.23  5366.8   -6.81 5386.16   -7.71
 5456.49    5.28 5497.29    8.06 5750.27   11.87 6353.62   11.69 6399.56     9.7
 6477.36   12.25 7050.62   13.09    7296   10.56 8189.16   15.17 8290.11   13.91
 8400.71   16.53    8859   17.94 9035.05   19.25 9232.03   16.09 9398.51   21.05
 9576.24   17.61 9751.36   22.31 9869.74   19.0610069.06   22.6110645.22   20.68
#Mann= 6 ,-1 , 0
 3202.61     .12       0 4525.46    .042       0 5497.29     .12       0
 6477.36     .15       0 8189.16     .07       0    8859     .15       0
#XS Ineff= 1 ,-1
 7005.11  7966.4   13.11
Permanent Ineff=
       F
#Block Obstruct= 2 ,-1
 3070.88 3502.62   15.53 6205.46 7672.67   10.78
Bank Sta=4862.83,5497.29
XS Rating Curve= 0
Exp/Cntr=.3,.1

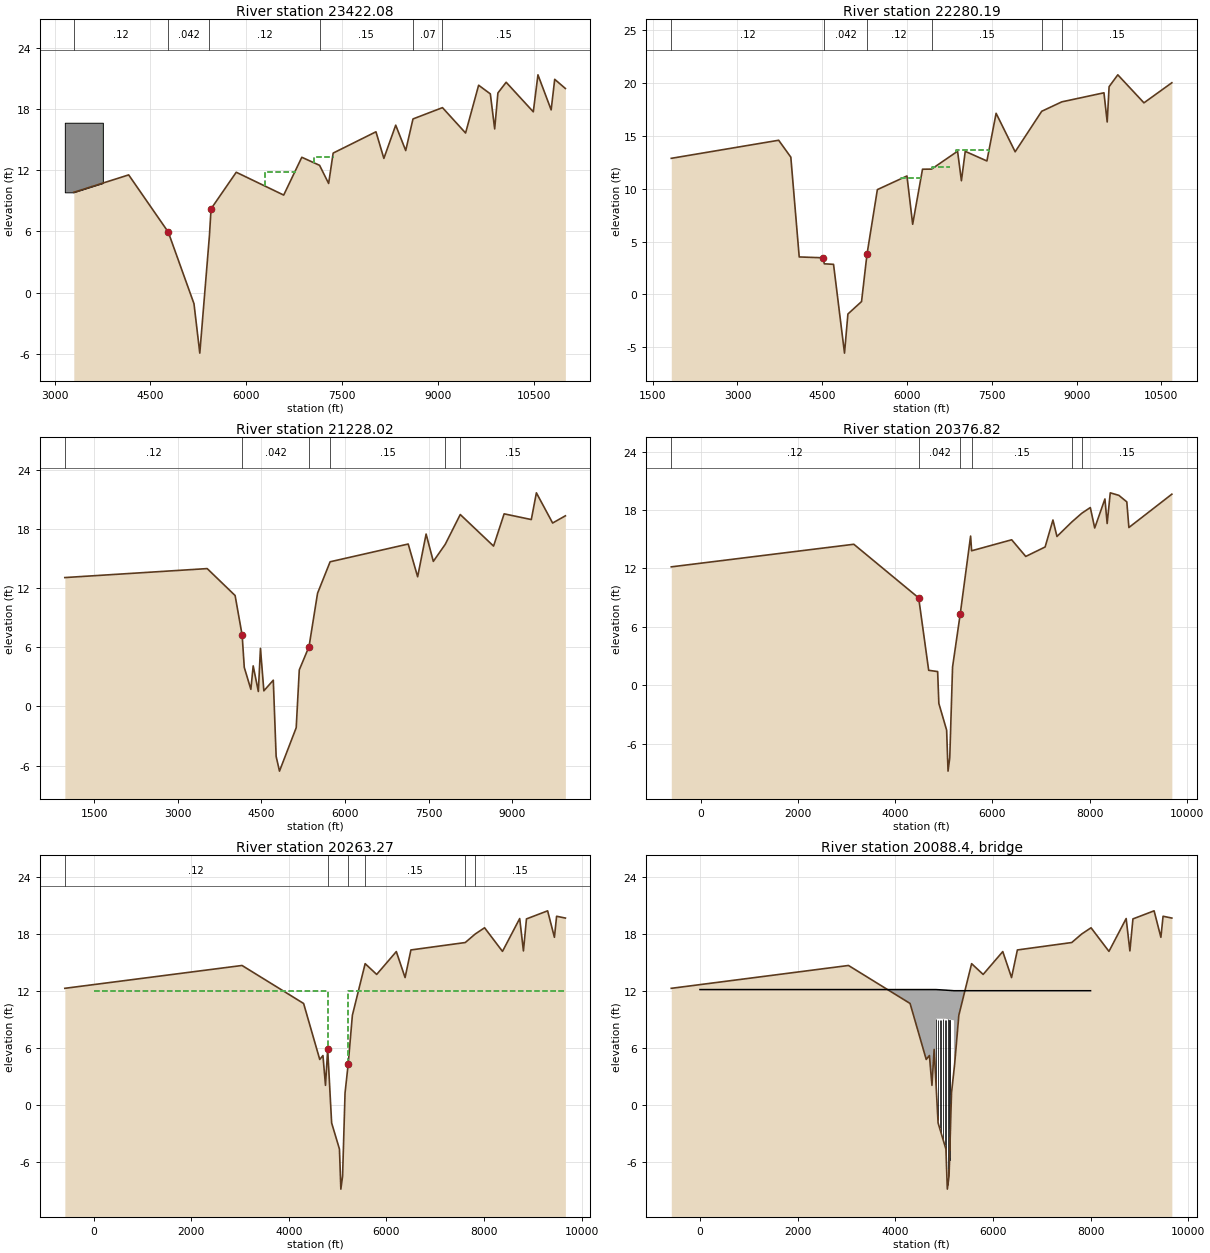
Type RM Length L Ch R = 1 ,23422.08,1672.9,1141.9,628.76
BEGIN DESCRIPTION:
Xsec blocked at basin boundary on left
END DESCRIPTION:
XS GIS Cut Line= 4
     3211892.105    13788933.675     3210495.745    13787893.105
     3210324.934     13787608.69      3205639.45    13784493.132
#Sta/Elev= 30
 3298.31    9.84 4158.28   11.55 4778.19    5.94 5181.21   -1.09 5272.24   -5.94
 5423.43    5.61 5448.53    8.22 5843.11   11.81 6586.33    9.57 6869.92   13.28
 7148.29   12.49 7290.11   10.71 7360.95   13.69  8031.6   15.78 8155.26   13.17
 8340.96   16.43 8497.51   13.94 8611.29   17.04 9073.29   18.15 9435.15   15.66
 9639.57   20.35 9822.97    19.5 9890.98   16.06 9941.54   19.5910070.66   20.64
10495.71   17.7410568.77   21.3710775.53   17.9310831.22   20.9310998.28   20.03
#Mann= 6 ,-1 , 0
 3298.31     .12       0 4778.19    .042       0 5423.43     .12       0
 7148.29     .15       0 8611.29     .07       0 9073.29     .15       0
#XS Ineff= 2 ,-1
 6289.96 6781.52   11.81 7059.87 7367.84   13.34
Permanent Ineff=
       F       F
#Block Obstruct= 1 ,-1
 3158.07  3753.8   16.67
Bank Sta=4778.19,5448.53
XS Rating Curve= 0
Exp/Cntr=.3,.1

Type RM Length L Ch R = 1 ,22280.19,862.18,1052.17,1295.83
XS GIS Cut Line= 5
     3213760.145    13786950.697     3210818.213    13786845.215
     3210376.066    13786949.199     3209592.739    13786959.045
      3205659.02    13784434.419
#Sta/Elev= 30
  1829.7   12.88 3729.53   14.59 3944.51   12.99 4093.02    3.55  4512.3    3.47
 4537.41     2.9 4700.11    2.85 4894.34   -5.55 4954.34   -1.85 5195.73    -.67
 5291.87    3.79  5475.6    9.92 5999.22   11.21 6100.24    6.64 6274.03   11.85
 6434.61   11.86  6894.5   13.55 6962.67   10.76 7030.28   13.54 7413.47   12.63
 7576.28   17.14 7913.33    13.5 8382.84   17.33 8737.06   18.22  9484.3   19.08
 9541.63   16.32 9575.26   19.66 9729.29   20.7810191.81   18.1310685.29   20.03
#Mann= 6 ,-1 , 0
  1829.7     .12       0 4537.41    .042       0 5291.87     .12       0
 6434.61     .15       0 8382.84     .07       0 8737.06     .15       0
#XS Ineff= 3 ,-1
 5889.73 6253.58   11.05 6447.11 6764.51   12.06 6872.89 7445.76    13.7
Permanent Ineff=
       F       F       F
Bank Sta=4512.3,5291.87
XS Rating Curve= 0
Exp/Cntr=.3,.1

Type RM Length L Ch R = 1 ,21228.02,452.9,851.2,713.4
XS GIS Cut Line= 4
     3214160.559    13786725.464     3210504.965    13785919.295
     3210118.671    13786153.299     3205678.591    13784375.707
#Sta/Elev= 30
  973.47   13.06 3527.08   13.97 4027.73   11.24 4153.97    7.22 4192.16    3.95
  4310.5    1.73 4351.99    4.11  4444.4    1.51 4482.18    5.88  4543.4    1.58
  4712.5    2.66 4763.61   -5.06  4823.6   -6.56 5123.59   -2.16 5178.81     3.7
 5353.78    6.07 5506.39   11.47 5731.69   14.66 7132.43   16.46 7301.58   13.14
 7453.26   17.47 7582.77    14.7 7796.57   16.43 8065.91   19.45 8663.27   16.25
 8852.86   19.52 9340.14   18.94 9431.43   21.65 9722.72   18.59 9951.24   19.32
#Mann= 6 ,-1 , 0
  973.47     .12       0 4153.97    .042       0 5353.78     .12       0
 5731.69     .15       0 7796.57     .07       0 8065.91     .15       0
Bank Sta=4153.97,5353.78
XS Rating Curve= 0
Exp/Cntr=.3,.1

Type RM Length L Ch R = 1 ,20376.82,100.01,113.55,119.84
XS GIS Cut Line= 6
     3215692.891    13787055.742     3211003.523    13785819.632
     3210514.682    13785550.103     3210201.739    13785358.344
     3208534.178    13785017.398     3206246.665    13783380.642
#Sta/Elev= 30
  -602.7   12.16 3149.66   14.48 4481.43    8.98 4483.42    8.95 4688.38    1.54
 4872.76    1.41  4897.4   -1.86 5057.42    -4.6 5086.34   -8.81 5121.67   -7.44
 5179.26    1.88  5337.5    7.34 5550.05   15.32 5571.08   13.81 6394.51   14.94
 6683.86   13.23 7081.73    14.2 7242.72   16.97 7325.34   15.28    7629   16.76
 7834.79   17.66 8010.82   18.25 8101.58   16.15 8311.28   19.13  8357.3   16.61
  8421.1   19.76 8597.88    19.5 8761.07   18.83 8804.02    16.2 9686.92   19.62
#Mann= 6 ,-1 , 0
  -602.7     .12       0 4483.42    .042       0  5337.5     .12       0
 5571.08     .15       0    7629     .07       0 7834.79     .15       0
#Block Obstruct= 2 , 0
         2502.02   14.33
Bank Sta=4481.43,5337.5
XS Rating Curve= 0
Exp/Cntr=.5,.3

Type RM Length L Ch R = 1 ,20263.27,365.66,349.66,481.59
XS GIS Cut Line= 6
      3215718.38    13786959.045     3211040.974    13785726.088
     3210564.974     13785463.64     3210238.996    13785263.893
      3208575.06    13784923.688     3206304.855    13783299.317
#Sta/Elev= 30
 -587.83   12.28 3041.97   14.68 4303.24   10.69 4633.93    4.81 4699.39    5.22
 4751.48    2.09 4796.52    5.87  4877.4   -1.86 5037.42    -4.6 5066.34   -8.81
 5101.67   -7.44 5152.13     1.3 5216.15    4.31 5302.22    9.45 5563.91   14.87
 5800.01   13.74 6202.17   16.14  6381.8   13.41 6501.05   16.31 7614.49   17.09
 7819.55   17.99 8009.97   18.64    8377   16.16 8729.45   19.61 8805.84   16.21
 8867.96   19.57 9301.53   20.42 9440.76   17.64 9485.25   19.85 9665.07   19.66
#Mann= 6 ,-1 , 0
 -587.83     .12       0 4796.52    .042       0 5216.15     .12       0
 5563.91     .15       0 7614.49     .07       0 7819.55     .15       0
#XS Ineff= 2 , 0
       0 4796.52      12 5216.15       0      12
Permanent Ineff=
       F       F
#Block Obstruct= 2 , 0
         2599.19   14.33
Bank Sta=4796.52,5216.15
XS Rating Curve= 0
Exp/Cntr=.5,.3

Type RM Length L Ch R = 3 ,20088.4 ,,,
BEGIN DESCRIPTION:
Bay Area Blvd.
END DESCRIPTION:
Bridge Culvert--1,0,-1,-1, 0
Deck Dist Width WeirC Skew NumUp NumDn MinLoCord MaxHiCord MaxSubmerge Is_Ogee
60,192,2.6,0, 7, 7, , , .95, 0, 0,0,,
       0 4832.51 4832.52 5031.33  5201.7 5201.71    8000
   12.15   12.15   12.15   12.09   12.03   12.03   12.03
               0    9.09    9.08    8.92       0
       0 4832.51 4832.52 5031.33  5201.7 5201.71    8000
   12.15   12.15   12.15   12.09   12.03   12.03   12.03
               0    9.09    9.08    8.92       0
Pier Skew, UpSta & Num, DnSta & Num=  ,4840, 4 ,4840, 4 , 3 , 3 , 0 ,,
    1.35    1.35     2.3     2.3
       0     6.8     6.8     9.1
    1.35    1.35     2.3     2.3
       0     6.8     6.8     9.1
Pier Skew, UpSta & Num, DnSta & Num=  ,4873.773, 4 ,4873.773, 4 , 3 , 3 , 0 ,,
    1.35    1.35     2.3     2.3
       0     6.7     6.7       9
    1.35    1.35     2.3     2.3
       0     6.7     6.7       9
Pier Skew, UpSta & Num, DnSta & Num=  ,4908.039, 4 ,4908.039, 4 , 3 , 3 , 0 ,,
    1.35    1.35     2.3     2.3
       0     6.7     6.7       9
    1.35    1.35     2.3     2.3
       0     6.7     6.7       9
Pier Skew, UpSta & Num, DnSta & Num=  ,4941.941, 4 ,4941.941, 4 , 3 , 3 , 0 ,,
    1.35    1.35     2.3     2.3
       0     6.7     6.7       9
    1.35    1.35     2.3     2.3
       0     6.7     6.7       9
Pier Skew, UpSta & Num, DnSta & Num=  ,4975.716, 4 ,4975.716, 4 , 3 , 3 , 0 ,,
    1.35    1.35     2.3     2.3
       0     6.8     6.8     9.1
    1.35    1.35     2.3     2.3
       0     6.8     6.8     9.1
Pier Skew, UpSta & Num, DnSta & Num=  ,5009.565, 4 ,5009.565, 4 , 3 , 3 , 0 ,,
    1.35    1.35     2.3     2.3
       0     6.7     6.7       9
    1.35    1.35     2.3     2.3
       0     6.7     6.7       9
Pier Skew, UpSta & Num, DnSta & Num=  ,5043.56, 4 ,5043.56, 4 , 3 , 3 , 0 ,,
    1.35    1.35     2.3     2.3
       0     6.7     6.7       9
    1.35    1.35     2.3     2.3
       0     6.7     6.7       9
Pier Skew, UpSta & Num, DnSta & Num=  ,5077.54, 4 ,5077.54, 4 , 3 , 3 , 0 ,,
    1.35    1.35     2.3     2.3
       0     6.8     6.8     9.1
    1.35    1.35     2.3     2.3
       0     6.7     6.7       9
Pier Skew, UpSta & Num, DnSta & Num=  ,5111.621, 4 ,5111.621, 4 , 3 , 3 , 0 ,,
    1.35    1.35     2.3     2.3
       0     6.8     6.8     9.1
    1.35    1.35     2.3     2.3
       0     6.7     6.7       9
BR Coef=-1 , 1 , 1 ,1.25, 0 ,,,.8,0,2,0,
WSPro=,,,, 1 ,,,, 0 ,,,, 0 ,,,,-1 ,-1 ,-1 , 0 , 0 , 0 , 0 , 0
BC Design=,, 0 ,, 0 ,,,,,,
BC HTab HWMax=20.48

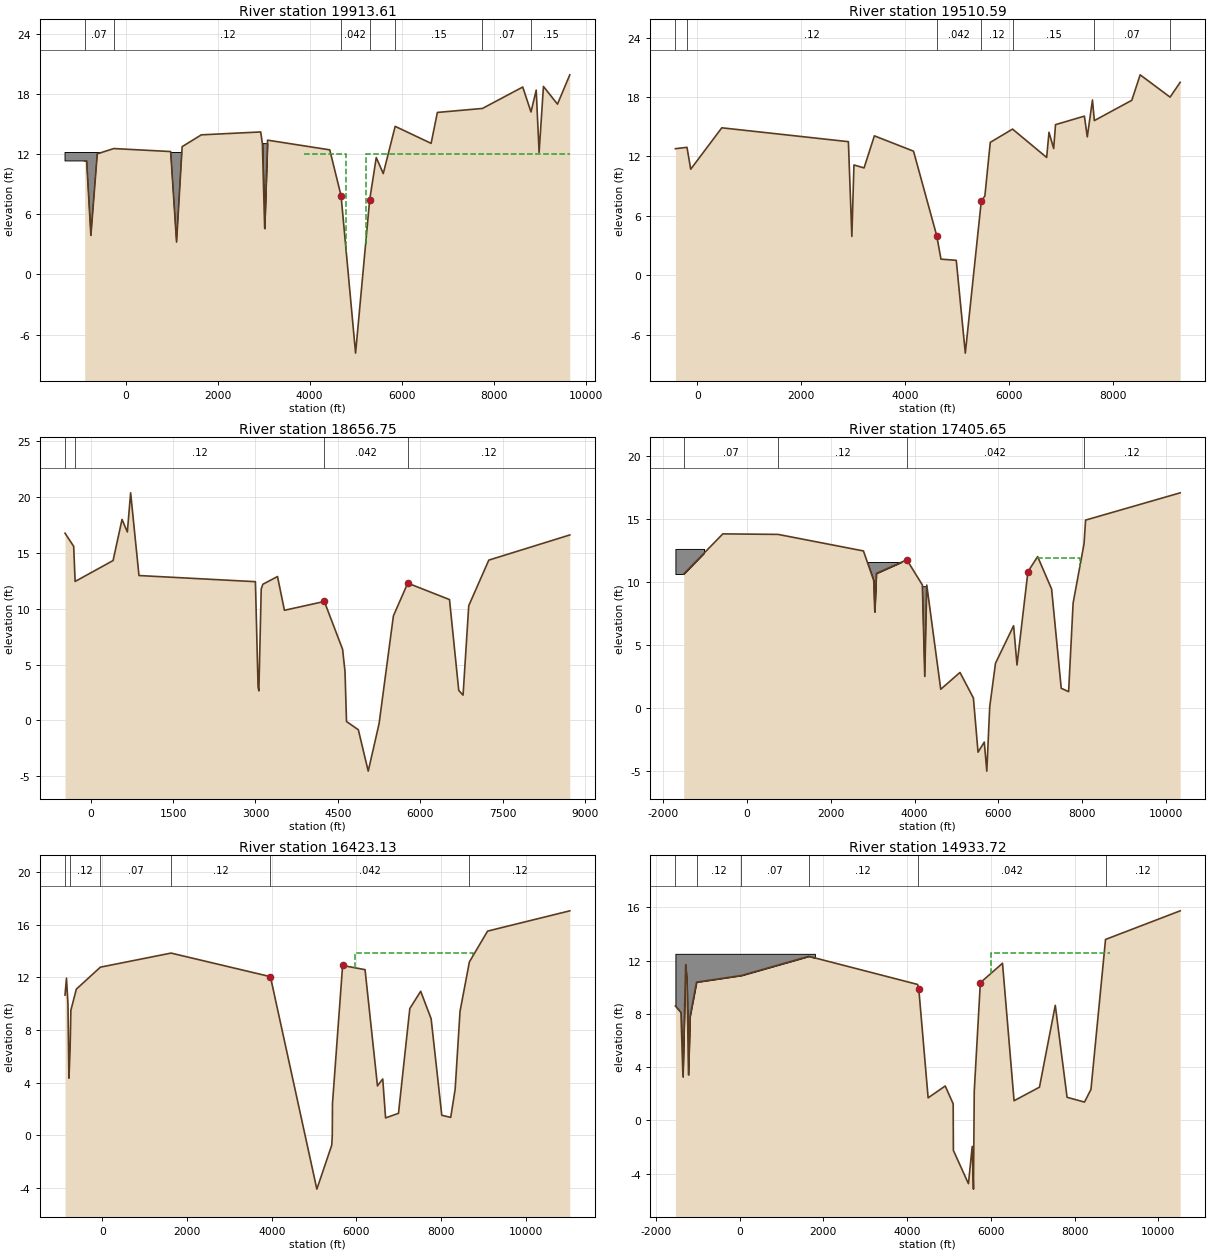
Type RM Length L Ch R = 1 ,19913.61,401.69,403.02,406.57
XS GIS Cut Line= 6
     3216287.758    13786775.516     3212508.779    13785549.951
     3211177.863    13785379.193     3209609.562    13784593.629
     3209140.485    13784517.334      3206577.72    13782971.583
#Sta/Elev= 30
  -888.9   11.35 -847.14   11.36 -754.86     3.9 -616.44   12.06 -256.25   12.59
  978.88   12.29 1107.34    3.25 1228.81   12.78 1645.51   13.96 2936.55   14.25
 2973.06   13.08 3022.71     4.6 3085.85   13.43 4437.64   12.46 4683.35    7.87
 4998.59   -7.86 5305.28    7.47 5448.25   11.69 5600.68   10.09 5859.35   14.81
 6640.73   13.11 6776.74    16.2 7757.29    16.6 8632.13   18.74  8811.7   16.25
 8925.28   18.43 8987.98    12.2 9082.34    18.8 9387.63   17.03 9655.23   19.96
#Mann= 7 ,-1 , 0
  -888.9     .07       0 -256.25     .12       0 4683.35    .042       0
 5305.28     .12       0 5859.35     .15       0 7757.29     .07       0
  8811.7     .15       0
#XS Ineff= 2 ,-1
 3887.04 4796.02   12.05 5216.15 9655.23      12
Permanent Ineff=
       F       F
#Block Obstruct= 2 ,-1
-1317.07 2097.56    12.2 2939.34 3096.51   13.13
Bank Sta=4683.35,5305.28
XS Rating Curve= 0
Exp/Cntr=.5,.3

Type RM Length L Ch R = 1 ,19510.59,823.49,853.84,1238.3
XS GIS Cut Line= 6
     3215887.344    13786224.946     3212585.788    13785153.984
     3211326.656    13785005.717     3209725.901    13784207.295
     3209225.272    13784125.868     3206903.056    13782821.428
#Sta/Elev= 30
 -420.06   12.78 -197.23   12.92  -125.8   10.71   471.9   14.89  2905.7   13.49
 2972.38    3.92  3012.3   11.14 3206.74   10.84 3405.49   14.08 4158.12   12.53
 4604.39    3.99 4685.62    1.63 4979.72    1.51 5153.59   -7.86 5460.28    7.47
 5529.69    8.01  5633.5   13.42  6061.8   14.76 6717.34    11.9 6762.65   14.44
 6852.79    12.8  6887.7   15.21 7443.08   16.07 7498.83   13.98 7598.24    17.7
 7634.82   15.62 8354.85   17.67 8515.17   20.24 9090.52   17.99 9284.61   19.48
#Mann= 7 ,-1 , 0
 -420.06     .07       0 -197.23     .12       0 4604.39    .042       0
 5460.28     .12       0  6061.8     .15       0 7634.82     .07       0
 9090.52     .15       0
#XS Ineff= 1 ,-1
 2876.78 3524.58   12.48
Permanent Ineff=
       F
Bank Sta=4604.39,5460.28
XS Rating Curve= 0
Exp/Cntr=.3,.1

Type RM Length L Ch R = 1 ,18656.75,772.79,1251.1,911.4
XS GIS Cut Line= 4
     3216087.551    13785999.714     3211284.731    13784441.772
     3211115.204    13783774.215     3209380.617    13780794.332
#Sta/Elev= 30
 -465.61   16.75 -307.95   15.57 -281.89   12.43  408.63    14.3  571.82   17.98
  668.43   16.86  728.33   20.36  879.98   12.96 2999.12   12.41 3047.47    2.98
 3061.94    2.64 3104.71   11.76 3134.77   12.18  3401.2   12.87 3527.01    9.85
 4253.53   10.64 4585.63    6.36 4629.85    4.35 4656.75     -.1 4872.18    -.84
 5052.17   -4.54 5249.69    -.29  5510.2    9.35 5771.19   12.28 6531.03   10.81
 6699.58    2.68 6777.89    2.26 6881.13   10.26 7246.45   14.34 8720.29   16.59
#Mann= 4 ,-1 , 0
 -465.61     .07       0 -281.89     .12       0 4253.53    .042       0
 5771.19     .12       0
#Block Obstruct= 2 , 0
         3376.52   12.11 5935.22           12.88
Bank Sta=4253.53,5771.19
XS Rating Curve= 0
Exp/Cntr=.3,.1

Type RM Length L Ch R = 1 ,17405.65,1156.4,982.52,339.27
XS GIS Cut Line= 6
     3218219.678    13786502.927     3215202.667    13785234.411
     3212528.499    13784514.443     3212399.467    13783624.127
     3211294.267    13782834.516     3209100.077    13780091.779
#Sta/Elev= 30
-1506.59   10.62 -573.27    13.8  743.19   13.76 2780.64   12.45 3025.48   10.11
 3051.23    7.62 3088.68   10.67 3815.06   11.75 4185.22    9.76 4242.96    2.52
 4290.74    9.75 4623.85     1.5 5082.77    2.83 5402.88     .81  5513.4   -3.48
 5662.47   -2.68 5722.37   -4.98  5792.3     .12    5930    3.56 6361.87    6.53
 6442.92    3.42 6703.16   10.81 6934.88      12 7268.27    9.43 7497.42    1.58
 7673.67    1.31 7780.91    8.32 8041.29   13.01 8078.33   14.8910334.34   17.05
#Mann= 4 ,-1 , 0
-1506.59     .07       0  743.19     .12       0 3815.06    .042       0
 8041.29     .12       0
#XS Ineff= 1 ,-1
 6919.23 7938.57   11.93
Permanent Ineff=
       F
#Block Obstruct= 3 ,-1
-1704.07-1021.14   12.61 -1506.6 4295.08    9.62 2495.68 3770.49   11.57
Bank Sta=3815.06,6703.16
XS Rating Curve= 0
Exp/Cntr=.3,.1

Type RM Length L Ch R = 1 ,16423.13,1499.9,1489.41,347.48
XS GIS Cut Line= 5
     3218631.089    13786468.643        3213481.    13784307.413
     3213118.531    13783615.349     3211328.551    13782560.242
     3209100.077    13779886.074
#Sta/Elev= 30
  -885.1   10.65 -850.93   11.94 -815.52    9.95  -792.6    4.34 -765.85     6.5
 -746.77     9.5 -617.72    11.1  -50.33   12.77  1619.2   13.84 3967.12   12.05
 5064.38   -4.09    5416    -.75 5428.97     .01 5433.26     2.4 5672.89    12.9
    6203   12.58 6496.46    3.75  6620.8    4.28 6688.11    1.32 6992.97    1.67
 7260.61    9.63 7517.58   10.94 7764.27    8.85 8015.84    1.52 8226.89    1.36
 8331.81     3.5 8446.62    9.41 8668.01   13.17  9098.3   15.5111040.12   17.05
#Mann= 6 ,-1 , 0
  -885.1     .07       0 -765.85     .12       0  -50.33     .07       0
  1619.2     .12       0 3967.12    .042       0 8668.01     .12       0
#XS Ineff= 1 ,-1
  5963.6 8750.85   13.88
Permanent Ineff=
       F
#Block Obstruct= 2 , 0
         2553.31   13.37
Bank Sta=3967.12,5672.89
XS Rating Curve= 0
Exp/Cntr=.3,.1

Type RM Length L Ch R = 1 ,14933.72,291.15,936.96,1666.56
XS GIS Cut Line= 6
     3219385.342    13786125.801     3213696.417    13782672.468
     3213273.774    13782939.571      3212699.92      13782868.8
     3211431.404    13782388.821     3209555.798    13780093.608
#Sta/Elev= 30
-1533.05    8.59-1401.02     8.1-1352.89    3.27-1287.37    11.7-1254.61   10.24
-1220.51    3.42-1182.61    7.82-1027.74   10.38   43.95   10.88 1652.94   12.32
 4249.94   10.21 4277.91     9.9 4501.82    1.69    4910    2.58 5100.01    1.24
 5104.84   -2.26 5464.63   -4.76 5554.63   -1.96 5584.63   -5.17 5603.05    2.17
 5748.67   10.34 6277.79    11.8 6553.87    1.47 7160.35    2.49 7538.18    8.64
 7819.66    1.73 8235.64    1.37 8390.13    2.32 8738.22   13.5910520.55   15.74
#Mann= 6 ,-1 , 0
-1533.05     .07       0-1027.74     .12       0   43.95     .07       0
 1652.94     .12       0 4249.94    .042       0 8738.22     .12       0
#XS Ineff= 1 ,-1
 5995.45 8846.42   12.59
Permanent Ineff=
       F
#Block Obstruct= 1 ,-1
-1533.05 1797.57   12.51
Bank Sta=4277.91,5748.67
XS Rating Curve= 0
Exp/Cntr=.3,.1

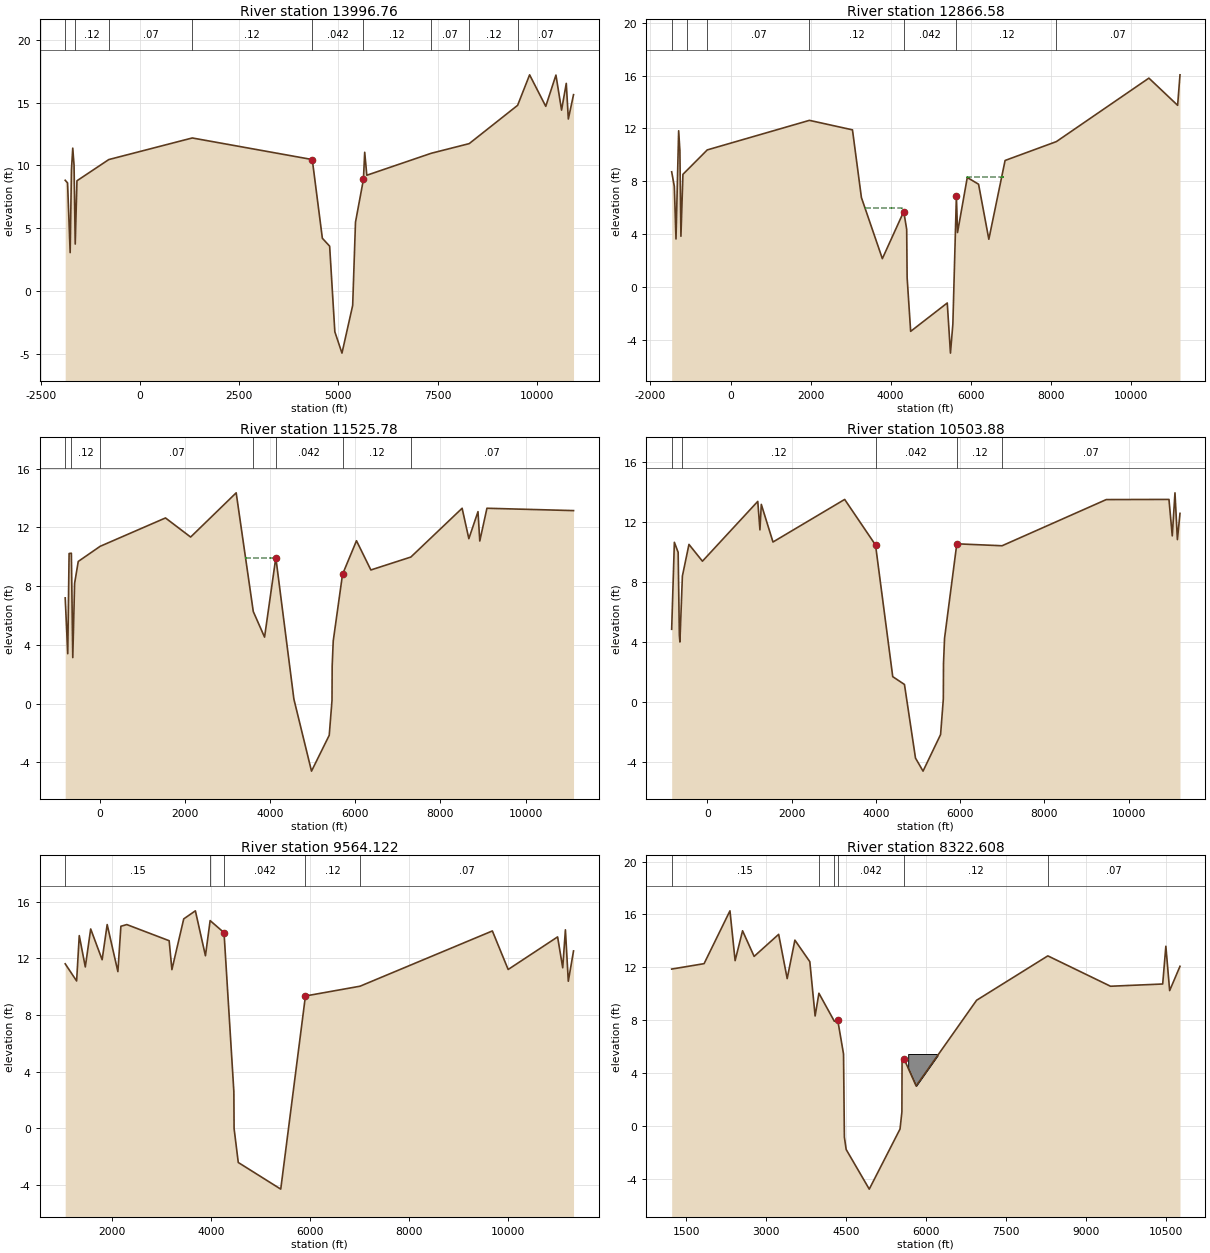
Type RM Length L Ch R = 1 ,13996.76,507.1,1130.19,1355.69
XS GIS Cut Line= 5
     3219516.095    13785949.662      3214414.13    13782765.948
     3214019.181    13782209.548     3213582.693    13781779.018
     3210574.298     13777177.62
#Sta/Elev= 30
-1883.66    8.81-1824.29     8.6-1758.74    3.05-1726.08    9.65-1693.42   11.37
-1660.76      10-1631.15    3.73-1587.41    8.77 -785.37   10.46 1318.04   12.18
 4340.87   10.46 4595.21    4.19  4778.7    3.56 4909.57   -3.26 5089.08   -4.96
 5358.97   -1.16 5429.81    5.47 5630.07    8.88 5661.94   11.04    5715    9.21
 7337.24   10.96 8294.87   11.73  9514.4   14.78 9816.78   17.2110223.38    14.7
10479.86   17.19 10621.7    14.410740.42   16.5310792.24   13.6910923.15   15.63
#Mann= 9 ,-1 , 0
-1883.66     .07       0-1631.15     .12       0 -785.37     .07       0
 1318.04     .12       0 4340.87    .042       0 5630.07     .12       0
 7337.24     .07       0 8294.87     .12       0  9514.4     .07       0
#Block Obstruct= 2 , 0
         1551.96   11.93
Bank Sta=4340.87,5630.07
XS Rating Curve= 0
Exp/Cntr=.3,.1

Type RM Length L Ch R = 1 ,12866.58,1498.97,1340.79,1237.27
XS GIS Cut Line= 4
     3219691.276    13785799.507     3214813.946    13782509.942
     3214808.904    13781334.181     3210957.247    13777215.633
#Sta/Elev= 30
-1469.48    8.71-1403.24    7.61-1361.47    3.62-1295.06   11.82-1264.57   10.33
-1238.16    3.83-1188.08    8.52-1089.04    8.82 -580.64   10.37 1971.75   12.61
 3046.76   11.89 3270.13    6.76 3793.24    2.13 4327.96     5.7 4400.92    4.35
 4412.11     .69 4500.23   -3.38 5414.56   -1.23 5494.54   -5.03 5554.53   -2.83
 5642.71    6.87 5671.17    4.11 5914.34    8.28 6196.63    7.77  6453.1     3.6
 6858.98    9.57 8140.43      1110451.42   15.8111169.03   13.7511228.23   16.06
#Mann= 7 ,-1 , 0
-1469.48     .07       0-1089.04     .12       0 -580.64     .07       0
 1971.75     .12       0 4327.96    .042       0 5642.71     .12       0
 8140.43     .07       0
#XS Ineff= 2 ,-1
 3357.16 4293.41    5.97  5914.8 6826.32    8.28
Permanent Ineff=
       F       F
#Block Obstruct= 2 , 0
         1873.14   14.36
Bank Sta=4327.96,5642.71
XS Rating Curve= 0
Exp/Cntr=.3,.1

Type RM Length L Ch R = 1 ,11525.78,1370.66,1021.9,651.92
XS GIS Cut Line= 4
      3219791.38    13785649.351     3216184.368    13781690.255
     3215935.651    13780817.413     3211883.204    13776840.245
#Sta/Elev= 30
  -815.5     7.2 -755.75     3.4  -723.9   10.22 -670.81   10.24 -637.75    3.14
 -594.58    8.19 -508.83    9.68    5.41   10.71 1540.28   12.64 2131.05   11.34
 3200.99   14.35 3602.85    6.27 3867.73    4.53 4132.43    9.94 4556.88     .31
 4970.61   -4.59 5387.03   -2.15 5451.95     .22 5456.03    2.57 5481.02    4.27
 5699.18     8.8 6027.21   11.09 6365.18     9.1 7304.71    9.98 8508.74    13.3
 8666.73   11.23 8881.68   13.07 8923.66   11.07 9091.55    13.311125.97   13.14
#Mann= 7 ,-1 , 0
  -815.5     .07       0 -670.81     .12       0    5.41     .07       0
 3602.85     .12       0 4132.43    .042       0 5699.18     .12       0
 7304.71     .07       0
#XS Ineff= 1 ,-1
 3424.01 4128.49    9.92
Permanent Ineff=
       F
#Block Obstruct= 2 , 0
         2931.17   14.21
Bank Sta=4132.43,5699.18
XS Rating Curve= 0
Exp/Cntr=.3,.1

Type RM Length L Ch R = 1 ,10503.88,1376.11,939.77,570.39
XS GIS Cut Line= 4
     3221568.217    13784197.851     3217331.273    13781131.832
     3216392.286    13780343.988     3212288.509     13776526.22
#Sta/Elev= 30
 -843.41    4.87  -779.5   10.67 -689.63      10 -661.21    4.49 -648.07    4.02
 -589.08    8.42 -433.11   10.53 -113.41    9.41 1199.41    13.4 1250.82    11.5
 1283.19    13.2 1560.45   10.69  3261.3   13.53 3993.34   10.49 4401.75    1.71
 4679.71    1.19 4941.68   -3.72 5120.61   -4.59 5537.03   -2.15 5601.95     .22
 5606.03    2.57 5631.02    4.27 5921.95   10.57 6996.04   10.44 9468.46   13.52
10955.46   13.5311033.71    11.111098.17   13.9711155.47   10.8511217.28    12.6
#Mann= 5 ,-1 , 0
 -843.41     .07       0 -589.08     .12       0 3993.34    .042       0
 5921.95     .12       0 6996.04     .07       0
#Block Obstruct= 2 , 0
         3252.36   13.2210167.34           13.18
Bank Sta=3993.34,5921.95
XS Rating Curve= 0
Exp/Cntr=.3,.1

Type RM Length L Ch R = 1 ,9564.122,1548.51,1241.51,994.42
XS GIS Cut Line= 4
      3221368.01    13780669.203     3218063.358    13780179.158
     3216867.476    13779969.995     3212357.077    13776457.652
#Sta/Elev= 30
 1055.75   11.62 1286.29   10.41 1339.78   13.61 1461.81    11.4 1570.71   14.08
 1801.86   11.91 1903.86   14.39 2120.31   11.07 2180.97   14.27  2300.2   14.39
 3156.25   13.25 3211.81   11.21 3450.62   14.79 3686.16   15.36  3889.4   12.19
 3984.28   14.67 4264.93   13.82 4463.48    2.61 4468.24       0  4552.8    -2.4
  5411.1   -4.28    5910    9.35 7013.21   10.04 9687.12   13.9410006.24   11.22
 11005.3   13.5211108.91   11.3411163.06   14.0211221.66   10.3911327.24   12.53
#Mann= 5 ,-1 , 0
 1055.75     .15       0 3984.28     .12       0 4264.93    .042       0
    5910     .12       0 7013.21     .07       0
Bank Sta=4264.93,5910
XS Rating Curve= 0
Exp/Cntr=.3,.1

Type RM Length L Ch R = 1 ,8322.608,1356.18,1369.85,1446.19
XS GIS Cut Line= 4
     3221192.829    13778216.668     3218016.165    13778772.524
     3216938.196    13778959.515     3212425.646    13776354.799
#Sta/Elev= 30
 1231.15   11.86 1838.57   12.27 2323.82   16.27 2420.49    12.5  2560.1   14.76
 2777.01   12.82 3236.83   14.49 3396.66   11.14 3541.18   14.05 3820.87   12.42
 3920.41    8.31 3991.23   10.03 4280.54    7.91 4344.87    7.98 4452.97    5.43
 4468.99    -.87 4502.56    -1.8 4935.25    -4.8 5512.03    -.25 5547.03    1.04
 5550.15    4.84 5590.84    5.03 5813.82    3.01 6947.71     9.5 8282.86   12.86
 9458.25   10.5610436.15   10.73 10495.4   13.59 10566.5   10.2310760.49   12.07
#Mann= 6 ,-1 , 0
 1231.15     .15       0 3991.23     .07       0 4280.54     .12       0
 4344.87    .042       0 5590.84     .12       0 8282.86     .07       0
#Block Obstruct= 1 ,-1
 5664.54 6213.84    5.43
Bank Sta=4344.87,5590.84
XS Rating Curve= 0
Exp/Cntr=.3,.1

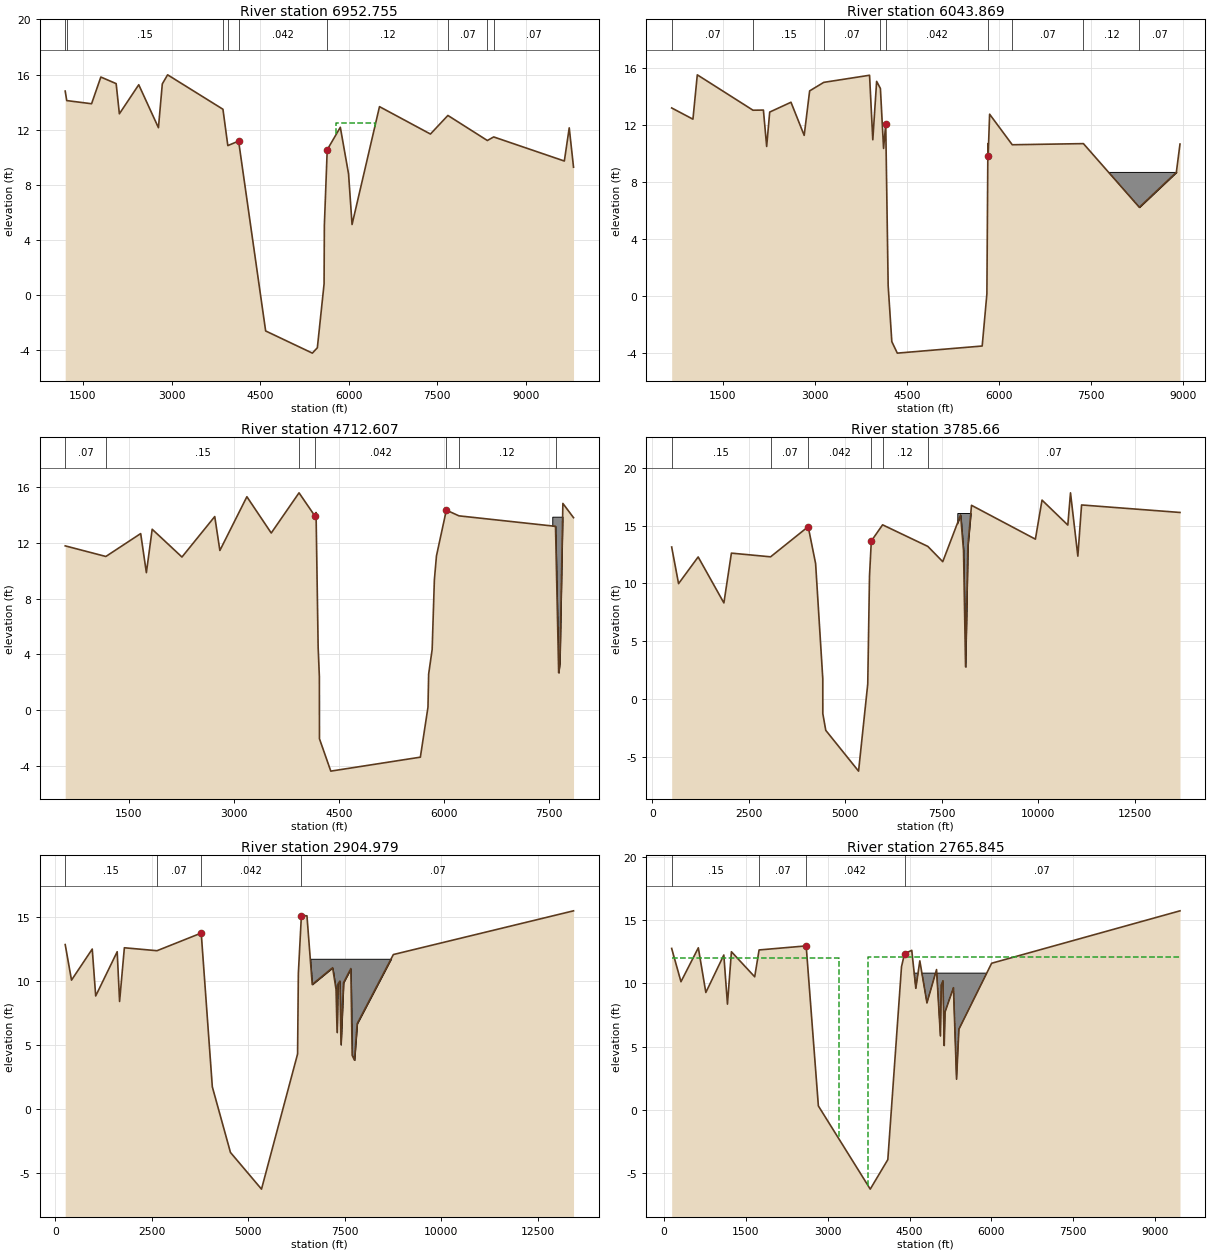
Type RM Length L Ch R = 1 ,6952.755,939.79,908.89,669.3
XS GIS Cut Line= 4
      3221236.69    13776937.631     3218060.351    13777394.077
     3216897.415    13777569.816     3212859.213    13776339.727
#Sta/Elev= 30
 1200.23    14.8 1225.92   14.11 1646.57   13.88 1803.74   15.82 2062.75   15.34
 2117.46   13.15 2445.34   15.26  2778.8   12.14 2844.17   15.32 2934.18   15.98
 3870.97   13.48 3953.54   10.84 4136.05   11.17 4593.94   -2.62 5384.71   -4.23
 5469.36   -3.84 5583.14     .79 5588.07    5.06 5636.46   10.54 5858.31   12.17
 5997.55    8.79 6056.96    5.11 6521.51   13.67 7384.08   11.68 7679.56   13.03
 8347.89   11.21 8454.71   11.47 9651.14    9.72 9733.87   12.13 9806.73    9.27
#Mann= 9 ,-1 , 0
 1200.23     .07       0 1225.92     .15       0 3870.97     .07       0
 3953.54    .012       0 4136.05    .042       0 5636.46     .12       0
 7679.56     .07       0 8347.89     .12       0 8454.71     .07       0
#XS Ineff= 1 ,-1
 5790.67 6439.14   12.51
Permanent Ineff=
       F
Bank Sta=4136.05,5636.46
XS Rating Curve= 0
Exp/Cntr=.3,.1

Type RM Length L Ch R = 1 ,6043.869,1154.14,1331.26,1470.59
XS GIS Cut Line= 4
     3221408.111    13775977.673     3217914.788    13776469.984
     3216334.381     13776768.67     3213234.601    13776239.624
#Sta/Elev= 30
  669.13   13.21 1015.67   12.42 1086.58   15.54 1994.06   13.05  2163.6   13.06
 2216.61    10.5    2266   12.92 2612.84   13.61 2827.89   11.28 2916.71   14.41
 3147.05   15.01 3892.65   15.51 3945.55   10.97 4008.04   15.08 4069.48   14.58
 4121.23   10.36 4156.12   12.08 4195.81     .71 4255.41   -3.23 4344.86   -4.04
  5727.5   -3.54 5804.19     .13 5820.95    10.7 5824.46     9.8 5848.68   12.77
 6217.29   10.62  7376.6    10.7 8287.49    6.22 8890.43    8.68 8949.96   10.67
#Mann= 9 ,-1 , 0
  669.13     .07       0 1994.06     .15       0 3147.05     .07       0
 4069.48     .12       0 4156.12    .042       0 5824.46     .12       0
 6217.29     .07       0  7376.6     .12       0 8287.49     .07       0
#Block Obstruct= 1 ,-1
 7528.46 9219.51    8.71
Bank Sta=4156.12,5824.46
XS Rating Curve= 0
Exp/Cntr=.3,.1

Type RM Length L Ch R = 1 ,4712.607,865.38,927.07,1066.95
XS GIS Cut Line= 4
     3221133.837    13775326.273     3217507.645    13775307.611
     3215948.972    13775270.804     3213885.274    13775138.485
#Sta/Elev= 30
  593.63   11.78 1173.89   11.02 1670.64   12.66 1751.87    9.86 1834.75   12.97
 2259.61   10.98 2727.38   13.88 2800.63   11.45 3186.02    15.3 3533.68    12.7
 3930.14   15.58 4155.18   13.93  4172.9   14.17 4202.96    4.51 4220.45    2.39
 4221.57   -2.04 4383.44   -4.36 5661.32   -3.36 5769.97     .22 5779.55    2.59
 5829.55    4.35 5861.25    9.34 5890.97   11.06 6032.01   14.34 6212.21   13.93
 7589.79   13.18 7634.88    2.69 7652.01    3.38 7695.01   14.82 7846.91    13.8
#Mann= 7 ,-1 , 0
  593.63     .07       0 1173.89     .15       0 3930.14     .07       0
 4155.18    .042       0 6032.01     .07       0 6212.21     .12       0
 7589.79     .07       0
#Block Obstruct= 1 ,-1
  7543.6 7710.27   13.87
Bank Sta=4155.18,6032.01
XS Rating Curve= 0
Exp/Cntr=.3,.1

Type RM Length L Ch R = 1 ,3785.66 ,226.88,880.68,1856.45
XS GIS Cut Line= 4
     3221345.645    13775151.166     3217495.237    13774453.369
     3214285.688    13774037.347     3208334.652    13773133.247
#Sta/Elev= 30
  502.84   13.15  681.38    9.98 1189.18   12.29 1855.74    8.31 2050.33   12.62
 3065.19    12.3 4039.56   14.91 4231.75   11.72 4417.62    1.75 4418.37   -1.27
 4495.05   -2.72 5344.59   -6.25 5582.38    1.29 5627.87   10.62 5674.86   13.67
 5967.08   15.07 7140.19    13.2 7525.75   11.88 7988.24   15.93 8063.98   12.83
 8116.45    2.78 8177.14   13.26 8270.46   16.76 9925.59   13.8310097.22   17.21
10765.46   15.0510834.85   17.8411025.53   12.3611121.66   16.7913671.69   16.14
#Mann= 6 ,-1 , 0
  502.84     .15       0 3065.19     .07       0 4039.56    .042       0
 5674.86     .07       0 5967.08     .12       0 7140.19     .07       0
#Block Obstruct= 1 ,-1
 7902.69 8274.95   16.09
Bank Sta=4039.56,5674.86
XS Rating Curve= 0
Exp/Cntr=.3,.1

Type RM Length L Ch R = 1 ,2904.979,104.73,139.13,279.99
XS GIS Cut Line= 6
     3221333.582    13775114.977     3217945.941    13774314.674
     3217246.362    13773919.751     3216422.664    13772994.501
     3215091.207    13770636.242     3210476.242    13768932.429
#Sta/Elev= 30
  256.36   12.88  419.95    10.1  957.17   12.53 1046.76    8.86 1603.89   12.32
 1665.89    8.43 1789.94   12.63 2636.26    12.4 3782.21   13.78    4070    1.75
 4540.11   -3.38 5344.59   -6.25    6280    4.32    6300   10.62 6378.65   15.15
 6523.16   15.13 6659.73    9.76  7188.5   11.07 7277.17    9.37  7304.1    6.01
  7324.3    9.78 7376.88   10.02 7405.09    5.05 7471.36     9.9 7660.48      11
 7695.16    4.22  7755.2    3.84 7824.87    6.69 8762.85    12.113433.13   15.52
#Mann= 4 ,-1 , 0
  256.36     .15       0 2636.26     .07       0 3782.21    .042       0
 6378.65     .07       0
#Block Obstruct= 1 ,-1
  6487.8 9629.27   11.77
Bank Sta=3782.21,6378.65
XS Rating Curve= 0
Exp/Cntr=.5,.3

Type RM Length L Ch R = 1 ,2765.845,316.31,387.33,817.25
XS GIS Cut Line= 6
     3221345.645    13775102.914     3217977.351    13774217.572
     3217309.998    13773840.841     3216507.716    13772939.647
     3215146.615    13770550.229     3210509.683    13768838.186
#Sta/Elev= 30
 139.852   12.76 310.293   10.13 628.363   12.81 766.221    9.281095.478   12.24
1162.243    8.361234.792    12.51661.503   10.521741.887   12.642604.812   12.96
2828.427     .323779.196   -6.254101.219   -3.924352.044   11.324407.354   12.34
4539.908   12.614614.253    9.614687.778   11.784818.311    8.464994.139   11.09
5065.133    5.85 5081.51    9.885111.406    10.25134.557    5.095150.792    7.75
5304.121    9.665360.803    2.435404.205    6.386003.718   11.599455.842   15.73
#Mann= 4 ,-1 , 0
 139.852     .15       01741.887     .07       02604.812    .042       0
4407.354     .07       0
#XS Ineff= 2 , 0
        3206.312   12.043740.701            12.1
Permanent Ineff=
       F       F
#Block Obstruct= 1 ,-1
4523.1856374.306   10.81
Bank Sta=2604.812,4407.354
XS Rating Curve= 0
Skew Angle= 45
Exp/Cntr=.5,.3