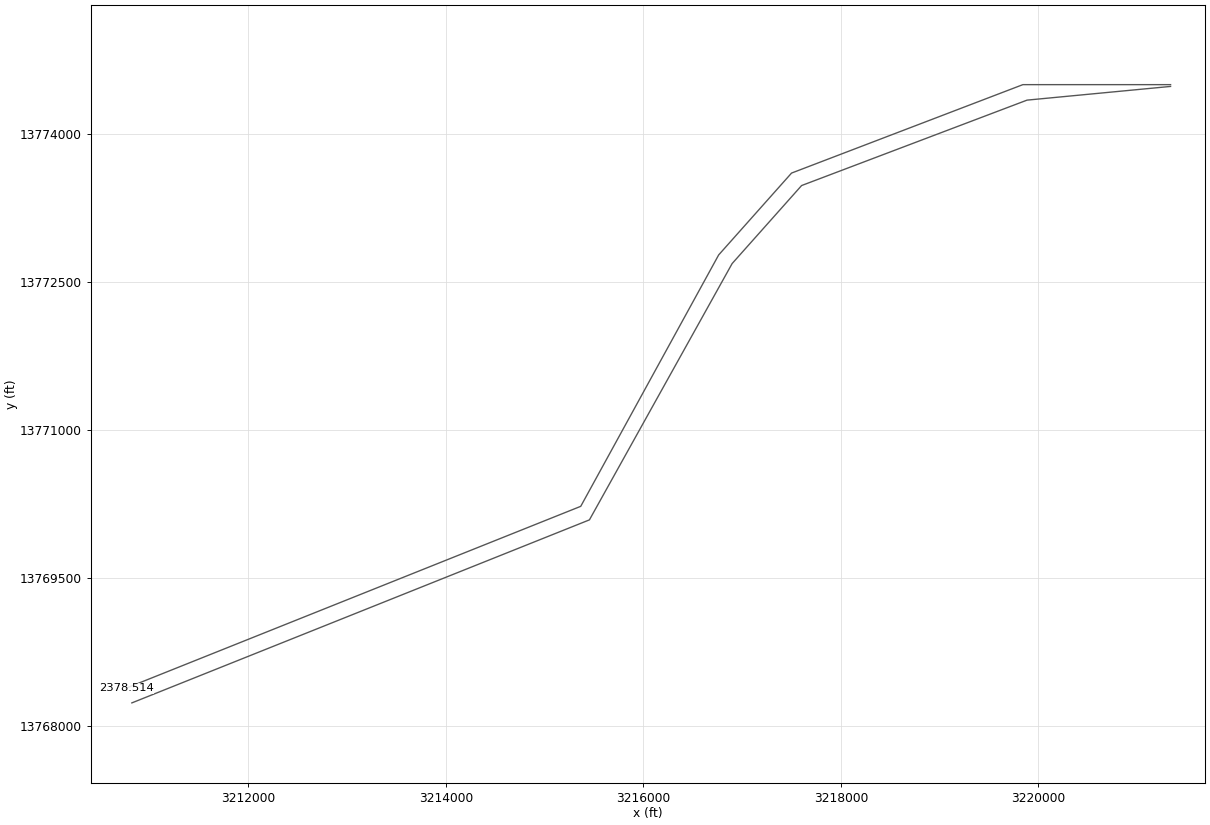
HEC-RAS study B100-00-00.prj: B100-00-00

--- B100-00-00.g01 (geometry) --- (continued)

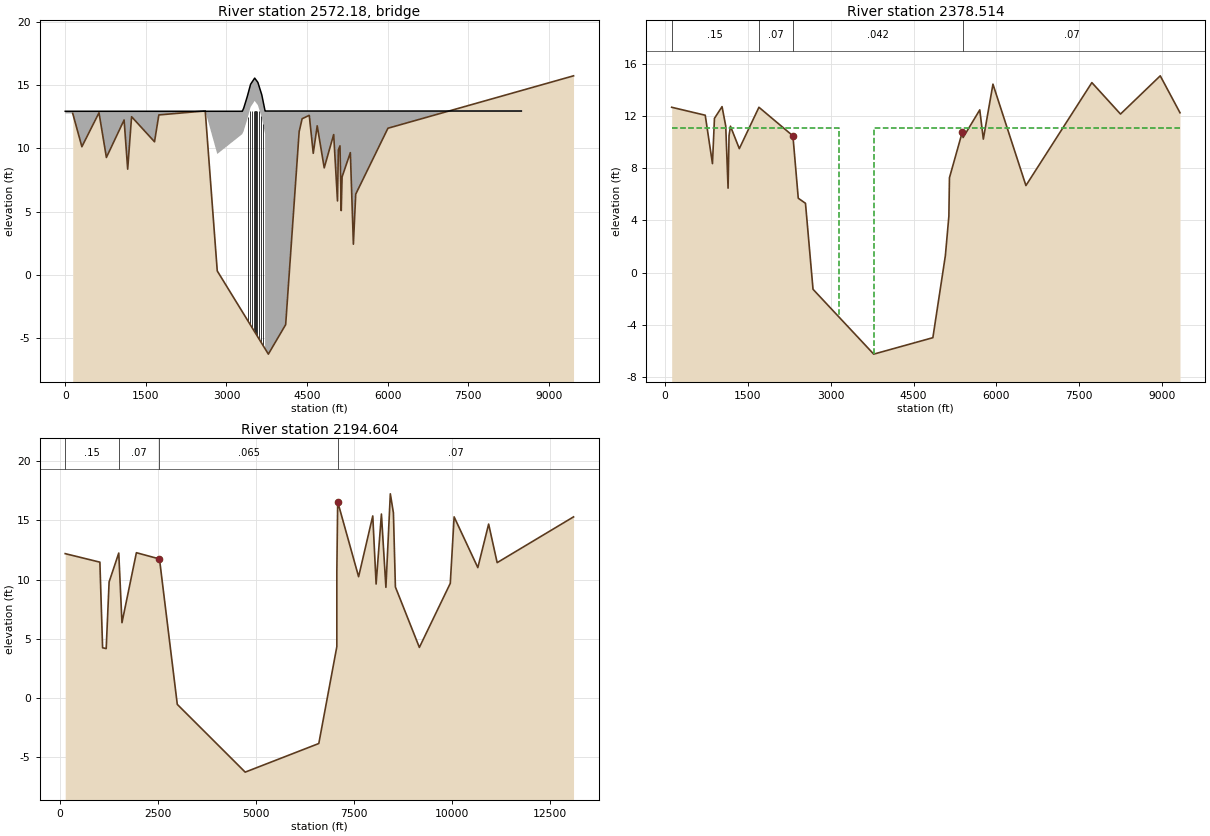
Type RM Length L Ch R = 3 ,2572.18 ,,,
BEGIN DESCRIPTION:
NASA Road
END DESCRIPTION:
Bridge Culvert--1,0,-1,-1, 0
Deck Dist Width WeirC Skew NumUp NumDn MinLoCord MaxHiCord MaxSubmerge Is_Ogee
235,103,2.6,45, 13, 13, , , .95, 0, 0,0,,
       03294.234 3294.243319.8383387.9323448.1493524.3193584.0063657.3473718.088
3718.0883718.0958485.281
   12.93   12.93   12.93   13.17   14.11   15.06   15.55   15.21   14.22   12.95
   12.95   12.95   12.95
       0           11.13   11.37   12.31   13.26   13.75   13.41   12.42   11.15
   11.15
       03294.234 3294.243319.8383387.9323448.1493524.3193584.0063657.3473718.088
3718.0883718.0958485.281
   12.93   12.93   12.93   13.17   14.11   15.06   15.55   15.21   14.22   12.95
   12.95   12.95   12.95
       0           11.13   11.37   12.31   13.26   13.75   13.41   12.42   11.15
   11.15
Pier Skew, UpSta & Num, DnSta & Num=  ,3398.815, 4 ,3398.815, 4 , 3 , 3 , 0 ,,
     1.4     1.4     2.6     2.6
     -10    3.43    3.43   12.93
     1.4     1.4     2.6     2.6
     -10    3.43    3.43   12.93
Pier Skew, UpSta & Num, DnSta & Num=  ,3433.71, 4 ,3433.71, 4 , 3 , 3 , 0 ,,
     1.4     1.4     2.6     2.6
     -10    3.43    3.43   12.93
     1.4     1.4     2.6     2.6
     -10    3.43    3.43   12.93
Pier Skew, UpSta & Num, DnSta & Num=  ,3469.066, 4 ,3469.066, 4 , 3 , 3 , 0 ,,
     1.4     1.4     2.6     2.6
     -10    3.43    3.43   12.93
     1.4     1.4     2.6     2.6
     -10    3.43    3.43   12.93
Pier Skew, UpSta & Num, DnSta & Num=  ,3504.421, 4 ,3504.421, 4 , 3 , 3 , 0 ,,
     1.4     1.4     2.6     2.6
     -10    3.43    3.43   12.93
     1.4     1.4     2.6     2.6
     -10    3.43    3.43   12.93
Pier Skew, UpSta & Num, DnSta & Num=  ,3539.776, 4 ,3539.776, 4 , 3 , 3 , 0 ,,
     1.4     1.4     2.6     2.6
     -10    3.43    3.43   12.93
     1.4     1.4     2.6     2.6
     -10    3.43    3.43   12.93
Pier Skew, UpSta & Num, DnSta & Num=  ,3575.132, 4 ,3575.132, 4 , 3 , 3 , 0 ,,
     1.4     1.4     2.6     2.6
     -10    3.43    3.43   12.93
     1.4     1.4     2.6     2.6
     -10    3.43    3.43   12.93
Pier Skew, UpSta & Num, DnSta & Num=  ,3610.487, 4 ,3610.487, 4 , 3 , 3 , 0 ,,
     1.4     1.4     2.6     2.6
     -10    3.43    3.43   12.93
     1.4     1.4     2.6     2.6
     -10    3.43    3.43   12.93
Pier Skew, UpSta & Num, DnSta & Num=  ,3645.843, 4 ,3645.843, 4 , 3 , 3 , 0 ,,
     1.4     1.4     2.6     2.6
     -10    3.43    3.43   12.93
     1.4     1.4     2.6     2.6
     -10    3.43    3.43   12.93
Pier Skew, UpSta & Num, DnSta & Num=  ,3681.198, 4 ,3681.198, 4 , 3 , 3 , 0 ,,
     1.4     1.4     2.6     2.6
     -10    3.43    3.43   12.93
     1.4     1.4     2.6     2.6
     -10    3.43    3.43   12.93
BR Coef=-1 , 1 , 1 ,1.25, 0 ,,,.8,0,2,0,
WSPro=,,,, 1 ,,,, 0 ,,,, 0 ,,,,-1 ,-1 ,-1 , 0 , 0 , 0 , 0 , 0
BC Design=,, 0 ,, 0 ,,,,,,
BC HTab HWMax=16.08

Type RM Length L Ch R = 1 ,2378.514,169.51,183.91,410.58
XS GIS Cut Line= 6
     3221339.614    13774499.764     3219843.802    13774499.764
     3217500.908    13773604.111     3216762.873    13772775.086
     3215366.034    13770229.101     3210760.691    13768386.963
#Sta/Elev= 30
 119.388   12.67 727.259   12.06   858.3    8.35 894.419   11.82 1031.81   12.72
 1098.49   11.241140.917    6.471158.665   10.491184.234   11.221344.719     9.5
1700.139   12.672315.633   10.482412.436     5.72543.223    5.312679.935   -1.28
3779.196   -6.254850.752   -4.995077.026    1.295140.666    4.32 5151.16    7.27
5385.212   10.795398.435   10.355700.158   12.475764.971   10.235939.202   14.44
6536.438    6.677730.883   14.568249.758   12.158969.706   15.089327.318   12.25
#Mann= 4 ,-1 , 0
 119.388     .15       01700.139     .07       02315.633    .042       0
5398.435     .07       0
#XS Ineff= 2 , 0
        3152.876   11.09 3780.78           11.09
Permanent Ineff=
       F       F
Bank Sta=2315.633,5385.212
XS Rating Curve= 0
Skew Angle= 45
Exp/Cntr=.5,.3

Type RM Length L Ch R = 1 ,2194.604,2109.81,2194.6,306.34
XS GIS Cut Line= 6
     3221339.614     13774481.67     3219886.023    13774342.945
     3217602.726    13773477.855     3216898.957     13772687.32
     3215454.002    13770091.981     3210819.905    13768238.324
#Sta/Elev= 30
   130.6   12.19 1015.18   11.47 1084.56    4.23  1176.4    4.16 1250.59     9.8
 1496.72   12.24 1578.74    6.35 1946.52   12.27 2535.73   11.74    2990    -.56
 4722.53   -6.29    6600   -3.87    7060    4.32    7060   10.62 7081.77   16.58
  7615.5   10.24  7976.7   15.38 8062.03    9.62 8197.36   15.54 8311.89    9.34
 8424.76   17.25  8503.4   15.64 8554.11    9.37 9165.62    4.26 9954.19    9.68
10052.24    15.310656.76   11.01 10932.7   14.6911150.16   11.4313098.37    15.3
#Mann= 4 ,-1 , 0
   130.6     .15       0 1496.72     .07       0 2535.73    .065       0
 7081.77     .07       0
Bank Sta=2535.73,7081.77
XS Rating Curve= 0
Exp/Cntr=.3,.1

Chan Stop Cuts=-1